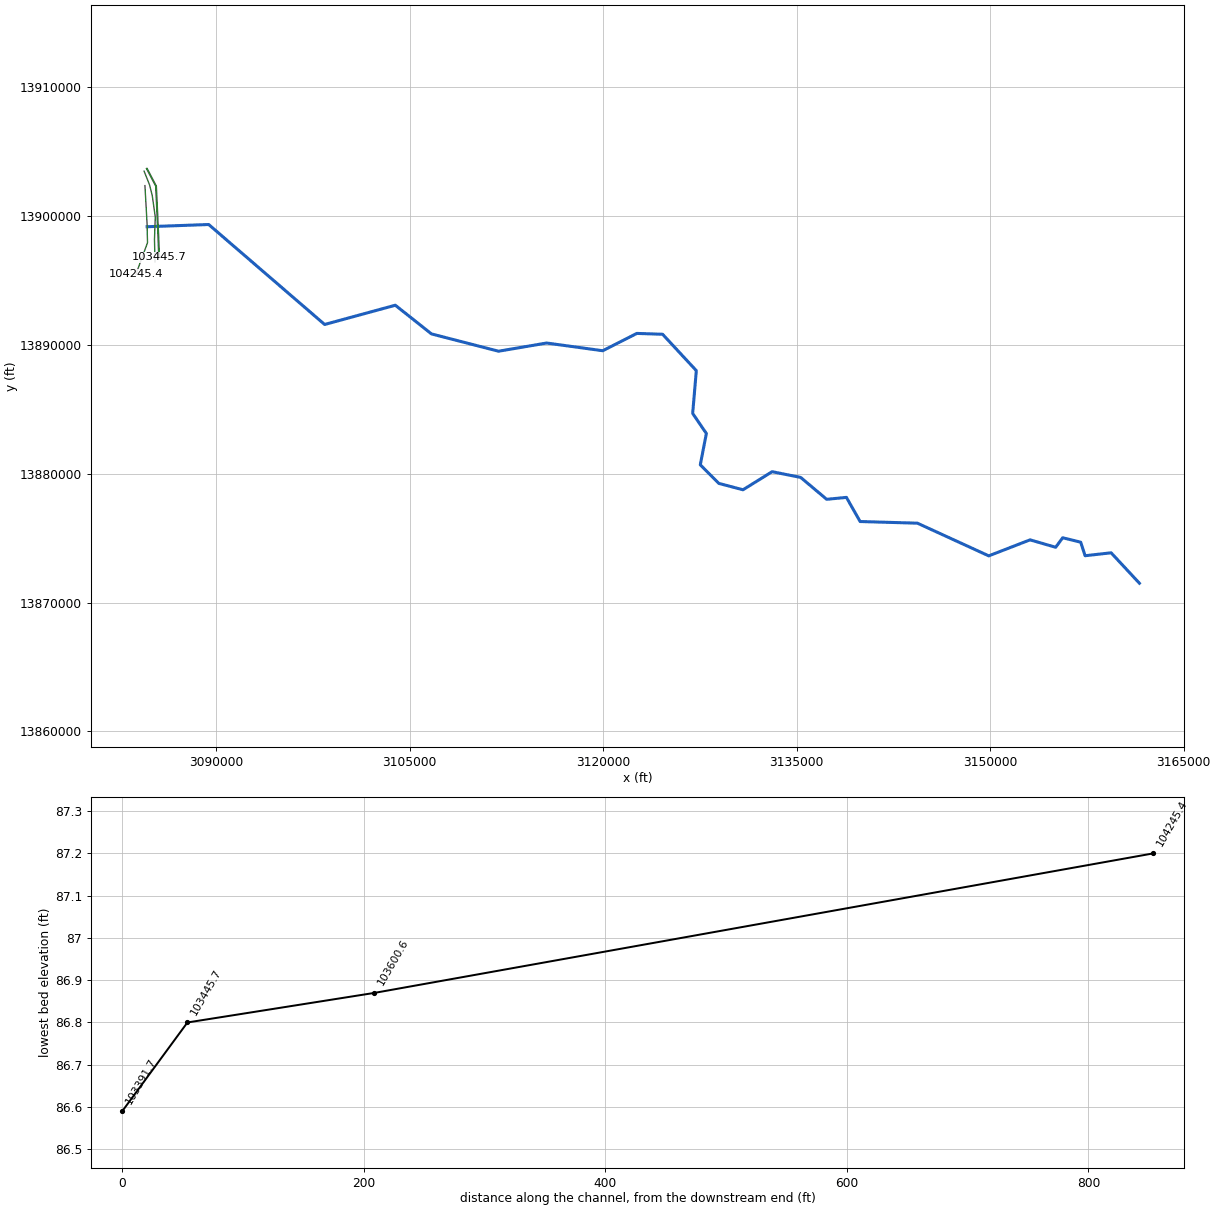
--- P118-00-00.PRJ (project) ---

Proj Title=P118-00-00
Current Plan=p02
Default Exp/Contr=.3,.1
English Units
Geom File=g01
Flow File=f01
Flow File=f02
Plan File=p01
Plan File=p02
Y Axis Title=Elevation
X Axis Title(PF)=Main Channel Distance
X Axis Title(XS)=Station
BEGIN DESCRIPTION:
Greens/Halls Bayou Watershed
Halls Bayou
HCFCD Unit P118-00-00
Flood Hazard Model
10, 2, 1, 0.2% Event
Filename P118-00-00.prj
Prepared by:  Watershed Concepts  Date:
Reviewed by:                      Date:
STATUS FIS
END DESCRIPTION:
DSS Export Rating Curves= 0
DSS Export Rating Curve Sorted= 0
DSS Export Volume Flow Curves= 0
DXF OffsetX= 0
DXF OffsetY= 0
DXF ScaleX= 1
DXF ScaleY= 10

--- P118-00-00.p02 (plan) ---

Plan Title=Floodway
Version=Version 3.0.1  Mar 2001
Short Identifier=Floodway0607
Geom File=g01
Flow File=f02
Subcritical Flow
K Sum by GR= 0
Std Step Tol= 0.01
Critical Tol= 0.01
Num of Std Step Trials= 20
Max Error Tol= 0.3
Flow Tol Ratio= 0.001
Split Flow NTrial= 30
Split Flow Tol= 0.02
Split Flow Ratio= 0.02
Log Output Level= 0
Friction Slope Method= 1
Unsteady Friction Slope Method= 2
Parabolic Critical Depth
Global Vel Dist= 0 , 0 , 0
Global Log Level= 0
CheckData=True
Encroach Param=-1 ,0,0, 2
Encroach River=P118-00-00
Encroach Reach=Reach - 1
Encroach Node=104245.4
       1  4976.7  5036.4
Encroach Node=103600.6
       1    4946  5036.4
Encroach Node=103445.7
       1    4936  5036.4
Encroach Node=103418.7
       1    4936  5036.4
Encroach Node=103391.7
       1    4936  5036.4
Encroach Node=102844.1
       1    4957    5031
Encroach Node=102449.7
       1    4941    5034
Encroach Node=102169.0
       1  4982.9  5030.1
Encroach Node=102142.0
       1  4982.9  5030.1
Encroach Node=102115.0
       1  4982.9  5030.1
Encroach Node=101525.5
       1    4975  5028.7
Encroach Node=100544.6
       1  4953.3  5030.6
Encroach Node=99524.3
       1    4966  5033.6
Encroach Node=98862.7
       1 4965.33 5042.63
Encroach Node=98434.7
       1 4928.23 5073.43
Encroach Node=98405.7
       1 4928.23 5073.43
Encroach Node=98376.7
       1 4928.23 5073.43
Encroach Node=97617.6
       1  4985.8  5011.6
Encroach Node=96497.8
       1  4921.4  5036.7
Encroach Node=95272.1
       1  4939.6  5055.9
Encroach Node=94253.5
       1    4850    5300
Encroach Node=93387.8
       1    4750    5600
Encroach Node=93247.3
       1    4850    5600
Encroach Node=93230.6
       1    4850    5600
Encroach Node=93213.9
       1    4850    5600
Encroach Node=92719.1
       1 4714.97    5800
Encroach Node=91689.3
       1    4800    5800
Encroach Node=91029.5
       1    4800    5800
Encroach Node=90112.3
       1    4800    5800
Encroach Node=89332.1
       1    4450    5750
Encroach Node=88590.5
       1    4300    5700
Encroach Node=87434.8
       1    4370    5500
Encroach Node=86591.9
       1    4550    5250
Encroach Node=86213.8
       1    4600    5058
Encroach Node=86186.8
       1    4600    5058
Encroach Node=86159.8
       1    4600    5058
Encroach Node=86145.4
       1    4600 5044.02
Encroach Node=86118.4
       1    4600 5044.02
Encroach Node=86091.4
       1    4600 5044.02
Encroach Node=85559.7
       1    4550    5120
Encroach Node=84594.2
       1    4600    5350
Encroach Node=83685.6
       1    4500    5450
Encroach Node=83450.7
       1    4500    5500
Encroach Node=83424.7
       1    4500    5500
Encroach Node=83398.7
       1    4500    5500
Encroach Node=83108.1
       1    4220    5500
Encroach Node=82744.1
       1    4200    5690
Encroach Node=81851.2
       1    4200    6000
Encroach Node=81268.8
       1    4200    6300
Encroach Node=81023.3
       1    4500    6300
Encroach Node=80997.3
       1    4500    6275
Encroach Node=80971.3
       1    4500    6275
Encroach Node=80695.0
       1    4600    6180
Encroach Node=80062.3
       1    4940    6070
Encroach Node=80038.3
       1    4940    6070
Encroach Node=80014.3
       1    4940    6070
Encroach Node=79807.3
       1    4902    5690
Encroach Node=79774.3
       1    4902    5690
Encroach Node=79741.3
       1    4902    5690
Encroach Node=79726.8
       1 4926.93    5936
Encroach Node=79635.3
       1 4926.93    5936
Encroach Node=79543.8
       1 4926.93    5936
Encroach Node=79540.3
       1 4943.94    5850
Encroach Node=79507.3
       1 4943.94    5850
Encroach Node=79474.3
       1 4943.94    5850
Encroach Node=79471.6
       1    4900    5800
Encroach Node=79461.1
       1    4900    5800
Encroach Node=79450.6
       1    4900    5800
Encroach Node=79215.1
       1    4760    5725
Encroach Node=78775.2
       1    4150    5600
Encroach Node=78764.7
       1    4300    5600
Encroach Node=78754.2
       1    4300    5600
Encroach Node=78752.3
       1    4015    5550
Encroach Node=78715.3
       1    4015    5550
Encroach Node=78678.3
       1    4015    5550
Encroach Node=77938.5
       1    4350    5490
Encroach Node=77911.5
       1    4350    5490
Encroach Node=77884.5
       1    4350    5490
Encroach Node=77880.4
       1    4350    5490
Encroach Node=77869.4
       1    4350    5490
Encroach Node=77441.3
       1    4195    5305
Encroach Node=76394.4
       1    4400    5330
Encroach Node=75489.4
       1    4400    5485
Encroach Node=74253.7
       1    4500    5250
Encroach Node=73879.2
       1    4500    5155
Encroach Node=73423.3
       1    4700    5275
Encroach Node=73377.8
       1    4700    5275
Encroach Node=73332.3
       1    4700    5275
Encroach Node=72405.2
       1    4750    5400
Encroach Node=71854.2
       1    4800    5400
Encroach Node=70744.2
       1    4800    5800
Encroach Node=69527.2
       1    4680    6320
Encroach Node=68131.0
       1    4000    6290
Encroach Node=67511.6
       1    4000    6400
Encroach Node=65955.8
       1    3650    6190
Encroach Node=65434.6
       1    4209    5610
Encroach Node=64273.7
       1    4875    5245
Encroach Node=64247.2
       1    4875    5245
Encroach Node=64220.7
       1    4875    5245
Encroach Node=64094.0
       1    4920    5113
Encroach Node=64059.0
       1    4920    5113
Encroach Node=64024.0
       1    4920    5113
Encroach Node=64010.4
       1    4935    5088
Encroach Node=63985.4
       1    4935    5088
Encroach Node=63960.4
       1    4935    5088
Encroach Node=63959.7
       1    4925    5100
Encroach Node=63908.2
       1    4925    5100
Encroach Node=63856.7
       1    4925    5100
Encroach Node=62823.2
       1    4450    5625
Encroach Node=61905.2
       1    4550    5500
Encroach Node=60625.3
       1    4650    5300
Encroach Node=59423.1
       1    4650    5200
Encroach Node=58613.7
       1    4650    5100
Encroach Node=58387.5
       1    4600  5095.1
Encroach Node=58359.5
       1    4600  5095.1
Encroach Node=58331.5
       1    4600  5095.1
Encroach Node=57555.5
       1    4500    5600
Encroach Node=56513.3
       1    4680    5520
Encroach Node=55557.7
       1    4800    5130
Encroach Node=54459.2
       1    4476    5310
Encroach Node=53801.7
       1 4920.96 5096.36
Encroach Node=53275.7
       1  4947.4  5057.4
Encroach Node=52844.3
       1    4915  5075.5
Encroach Node=52815.3
       1    4915  5075.5
Encroach Node=52786.3
       1    4915  5075.5
Encroach Node=52465.7
       1    4937  5083.9
Encroach Node=52221.3
       1    4937    5265
Encroach Node=52207.8
       1    4937    5265
Encroach Node=52194.3
       1    4937    5265
Encroach Node=51283.9
       1    4700    5300
Encroach Node=51096.9
       1  4941.3    5290
Encroach Node=51083.9
       1  4941.3    5290
Encroach Node=51070.9
       1  4941.3    5290
Encroach Node=50549.6
       1    4915    5200
Encroach Node=50021.9
       1    4825    5175
Encroach Node=49980.9
       1    4825    5175
Encroach Node=49939.9
       1    4825    5175
Encroach Node=49231.7
       1    4240    5180
Encroach Node=48480.5
       1    4250    5180
Encroach Node=48196.5
       1    4300    5320
Encroach Node=48183.0
       1    4300    5320
Encroach Node=48169.5
       1    4300    5320
Encroach Node=47607.9
       1    4150    5435
Encroach Node=46939.0
       1    4025    5460
Encroach Node=46594.8
       1    3950    5400
Encroach Node=46560.8
       1    3950    5400
Encroach Node=46526.8
       1    3950    5400
Encroach Node=46499.9
       1    3925    5425
Encroach Node=46489.4
       1    3925    5425
Encroach Node=46478.9
       1    3925    5425
Encroach Node=45952.3
       1    3925    5355
Encroach Node=45161.4
       1    3620    5360
Encroach Node=44549.9
       1    3580    5475
Encroach Node=44143.3
       1    3600    5600
Encroach Node=43215.5
       1    3850    5250
Encroach Node=42471.0
       1    4080    5330
Encroach Node=41863.8
       1    3880 5332.97
Encroach Node=41285.4
       1    3870    5400
Encroach Node=41243.9
       1    3870    5400
Encroach Node=41202.4
       1    3870    5400
Encroach Node=41197.2
       1    3870    5400
Encroach Node=41185.7
       1    3870    5400
Encroach Node=40951.8
       1    3850 5652.33
Encroach Node=40919.3
       1    3850 5652.33
Encroach Node=40886.8
       1    3850 5652.33
Encroach Node=40846.9
       1    3790    5866
Encroach Node=40726.2
       1    3790    5866
Encroach Node=40605.5
       1    3790    5866
Encroach Node=40584.6
       1    3730 5682.26
Encroach Node=40550.1
       1    3730 5682.26
Encroach Node=40515.6
       1    3730 5682.26
Encroach Node=39969.8
       1    3747    5350
Encroach Node=39188.6
       1    3580    5410
Encroach Node=38170.2
       1    3650    5200
Encroach Node=37258.6
       1    4000    5240
Encroach Node=36107.2
       1    4000    5450
Encroach Node=35434.7
       1    4730    5275
Encroach Node=35045.7
       1    4935    5075
Encroach Node=35025.9
       1    4935    5075
Encroach Node=35006.1
       1    4935    5075
Encroach Node=34984.3
       1  4925.5  5110.5
Encroach Node=34927.3
       1  4925.5  5110.5
Encroach Node=34870.3
       1  4925.5  5110.5
Encroach Node=33920.1
       1    4825    5175
Encroach Node=32749.8
       1    4825    5175
Encroach Node=31824.3
       1    4900    5100
Encroach Node=30679.1
       1    4850    5250
Encroach Node=30099.1
       1    4865    5125
Encroach Node=29757.8
       1    4850    5150
Encroach Node=29731.3
       1    4850    5150
Encroach Node=29704.8
       1    4850    5150
Encroach Node=28983.7
       1    4900    5070
Encroach Node=28387.3
       1    4880    5120
Encroach Node=27992.0
       1 4863.86  5046.5
Encroach Node=27567.7
       1    4900    5100
Encroach Node=27317.0
       1    4850    5130
Encroach Node=27306.0
       1    4850    5130
Encroach Node=27304.8
       1    4850    5130
Encroach Node=27242.8
       1    4850    5130
Encroach Node=27180.8
       1    4850    5130
Encroach Node=27179.0
       1    4850    5130
Encroach Node=27167.5
       1    4850    5130
Encroach Node=26466.1
       1    4880    5100
Encroach Node=25982.8
       1    4836    5075
Encroach Node=25318.4
       1    4888    5150
Encroach Node=24564.2
       1    4850    5086
Encroach Node=23984.6
       1    4810    5100
Encroach Node=23286.2
       1    4908    5087
Encroach Node=22973.4
       1  4918.6    5077
Encroach Node=22951.4
       1  4918.6    5077
Encroach Node=22929.4
       1  4918.6    5077
Encroach Node=22630.3
       1  4920.3  5065.3
Encroach Node=22609.0
       1  4920.3  5065.3
Encroach Node=22587.7
       1  4920.3  5065.3
Encroach Node=22186.8
       1    4920    5080
Encroach Node=21829.0
       1  4935.6  5095.6
Encroach Node=21589.8
       1    4930    5070
Encroach Node=21362.0
       1    4910    5080
Encroach Node=21333.0
       1    4910    5080
Encroach Node=21304.0
       1    4910    5080
Encroach Node=21010.4
       1    4867    5145
Encroach Node=20948.9
       1    4867    5145
Encroach Node=20887.4
       1    4867    5145
Encroach Node=20880.6
       1    4885    5135
Encroach Node=20869.6
       1    4885    5135
Encroach Node=20858.6
       1    4885    5135
Encroach Node=19860.0
       1 4892.45    5239
Encroach Node=18597.4
       1  4876.5    5092
Encroach Node=18107.1
       1  4893.8  5121.2
Encroach Node=17130.3
       1  4908.6  5063.6
Encroach Node=16004.0
       1  4948.3    5155
Encroach Node=15045.6
       1    4913  5102.3
Encroach Node=13937.2
       1    4850    5075
Encroach Node=13341.9
       1    4800    5080
Encroach Node=12945.5
       1    4890    5110
Encroach Node=12935.0
       1    4890    5110
Encroach Node=12931.7
       1    4890    5111
Encroach Node=12904.8
       1    4890    5111
Encroach Node=12877.9
       1    4890    5111
Encroach Node=12117.3
       1    4910    5110
Encroach Node=10905.1
       1    4910    5085
Encroach Node=9879.2
       1    4870  5083.8
Encroach Node=8777.0
       1  4904.7    5500
Encroach Node=8024.4
       1    4880    5120
Encroach Node=6779.3
       1    4880    5120
Encroach Node=5748.4
       1    4900    5100
Encroach Node=4492.0
       1    4900    5170
Encroach Node=3597.9
       1    4850    5110
Encroach Node=2709.4
       1    4880    5120
Encroach Node=1695.9
       1    4830    5070
Encroach Node=678.7
       1    4930    5150
Encroach Reach=P118-00-00_0007
Encroach Node=104245.4
       1  4976.7  5036.4
Encroach Node=103600.6
       1    4946  5036.4
Encroach Node=103445.7
       1    4936  5036.4
Encroach Node=103418.7
       1    4936  5036.4
Encroach Node=103391.7
       1    4936  5036.4
Encroach Node=102844.1
       1    4957    5031
Encroach Node=102449.7
       1    4941    5034
Encroach Node=102169.0
       1  4982.9  5030.1
Encroach Node=102142.0
       1  4982.9  5030.1
Encroach Node=102115.0
       1  4982.9  5030.1
Encroach Node=101525.5
       1    4975  5028.7
Encroach Node=100544.6
       1  4953.3  5030.6
Encroach Node=99524.3
       1    4966  5033.6
Encroach Node=98862.7
       1 4965.33 5042.63
Encroach Node=98434.7
       1 4928.23 5073.43
Encroach Node=98405.7
       1 4928.23 5073.43
Encroach Node=98376.7
       1 4928.23 5073.43
Encroach Node=97617.6
       1  4985.8  5011.6
Encroach Node=96497.8
       1  4921.4  5036.7
Encroach Node=95272.1
       1  4939.6  5055.9
Encroach Node=94253.5
       1    4850    5300
Encroach Node=93387.8
       1    4750    5600
Encroach Node=93247.3
       1    4850    5600
Encroach Node=93230.6
       1    4850    5600
Encroach Node=93213.9
       1    4850    5600
Encroach Node=92719.1
       1 4714.97    5800
Encroach Node=91689.3
       1    4800    5800
Encroach Node=91029.5
       1    4800    5800
Encroach Node=90112.3
       1    4800    5800
Encroach Node=89332.1
       1    4450    5750
Encroach Node=88590.5
       1    4300    5700
Encroach Node=87434.8
       1    4370    5500
Encroach Node=86591.9
       1    4550    5250
Encroach Node=86213.8
       1    4600    5058
Encroach Node=86186.8
       1    4600    5058
Encroach Node=86159.8
       1    4600    5058
Encroach Node=86145.4
       1    4600 5044.02
Encroach Node=86118.4
       1    4600 5044.02
Encroach Node=86091.4
       1    4600 5044.02
Encroach Node=85559.7
       1    4550    5120
Encroach Node=84594.2
       1    4600    5350
Encroach Node=83685.6
       1    4500    5450
Encroach Node=83450.7
       1    4500    5500
Encroach Node=83424.7
       1    4500    5500
Encroach Node=83398.7
       1    4500    5500
Encroach Node=83108.1
       1    4220    5500
Encroach Node=82744.1
       1    4200    5690
Encroach Node=81851.2
       1    4200    6000
Encroach Node=81268.8
       1    4200    6300
Encroach Node=81023.3
       1    4500    6300
Encroach Node=80997.3
       1    4500    6275
Encroach Node=80971.3
       1    4500    6275
Encroach Node=80695.0
       1    4600    6180
Encroach Node=80062.3
       1    4940    6070
Encroach Node=80038.3
       1    4940    6070
Encroach Node=80014.3
       1    4940    6070
Encroach Node=79807.3
       1    4902    5690
Encroach Node=79774.3
       1    4902    5690
Encroach Node=79741.3
       1    4902    5690
Encroach Node=79726.8
       1 4926.93    5936
Encroach Node=79635.3
       1 4926.93    5936
Encroach Node=79543.8
       1 4926.93    5936
Encroach Node=79540.3
       1 4943.94    5850
Encroach Node=79507.3
       1 4943.94    5850
Encroach Node=79474.3
       1 4943.94    5850
Encroach Node=79471.6
       1    4900    5800
Encroach Node=79461.1
       1    4900    5800
Encroach Node=79450.6
       1    4900    5800
Encroach Node=79215.1
       1    4760    5725
Encroach Node=78775.2
       1    4150    5600
Encroach Node=78764.7
       1    4300    5600
Encroach Node=78754.2
       1    4300    5600
Encroach Node=78752.3
       1    4015    5550
Encroach Node=78715.3
       1    4015    5550
Encroach Node=78678.3
       1    4015    5550
Encroach Node=77938.5
       1    4350    5490
Encroach Node=77911.5
       1    4350    5490
Encroach Node=77884.5
       1    4350    5490
Encroach Node=77880.4
       1    4350    5490
Encroach Node=77869.4
       1    4350    5490
Encroach Node=77441.3
       1    4195    5305
Encroach Node=76394.4
       1    4400    5330
Encroach Node=75489.4
       1    4400    5485
Encroach Node=74253.7
       1    4500    5250
Encroach Node=73879.2
       1    4500    5155
Encroach Node=73423.3
       1    4700    5275
Encroach Node=73377.8
       1    4700    5275
Encroach Node=73332.3
       1    4700    5275
Encroach Node=72405.2
       1    4750    5400
Encroach Node=71854.2
       1    4800    5400
Encroach Node=70744.2
       1    4800    5800
Encroach Node=69527.2
       1    4680    6320
Encroach Node=68131.0
       1    4000    6290
Encroach Node=67511.6
       1    4000    6400
Encroach Node=65955.8
       1    3650    6190
Encroach Node=65434.6
       1    4209    5610
Encroach Node=64273.7
       1    4875    5245
Encroach Node=64247.2
       1    4875    5245
Encroach Node=64220.7
       1    4875    5245
Encroach Node=64094.0
       1    4920    5113
Encroach Node=64059.0
       1    4920    5113
Encroach Node=64024.0
       1    4920    5113
Encroach Node=64010.4
       1    4935    5088
Encroach Node=63985.4
       1    4935    5088
Encroach Node=63960.4
       1    4935    5088
Encroach Node=63959.7
       1    4925    5100
Encroach Node=63908.2
       1    4925    5100
Encroach Node=63856.7
       1    4925    5100
Encroach Node=62823.2
       1    4450    5625
Encroach Node=61905.2
       1    4550    5500
Encroach Node=60625.3
       1    4650    5300
Encroach Node=59423.1
       1    4650    5200
Encroach Node=58613.7
       1    4650    5100
Encroach Node=58387.5
       1    4600  5095.1
Encroach Node=58359.5
       1    4600  5095.1
Encroach Node=58331.5
       1    4600  5095.1
Encroach Node=57555.5
       1    4500    5600
Encroach Node=56513.3
       1    4680    5520
Encroach Node=55557.7
       1    4800    5130
Encroach Node=54459.2
       1    4476    5310
Encroach Node=53801.7
       1 4920.96 5096.36
Encroach Node=53275.7
       1  4947.4  5057.4
Encroach Node=52844.3
       1    4915  5075.5
Encroach Node=52815.3
       1    4915  5075.5
Encroach Node=52786.3
       1    4915  5075.5
Encroach Node=52465.7
       1    4937  5083.9
Encroach Node=52221.3
       1    4937    5265
Encroach Node=52207.8
       1    4937    5265
Encroach Node=52194.3
       1    4937    5265
Encroach Node=51283.9
       1    4700    5300
Encroach Node=51096.9
       1  4941.3    5290
Encroach Node=51083.9
       1  4941.3    5290
Encroach Node=51070.9
       1  4941.3    5290
Encroach Node=50549.6
       1    4915    5200
Encroach Node=50021.9
       1    4825    5175
Encroach Node=49980.9
       1    4825    5175
Encroach Node=49939.9
       1    4825    5175
Encroach Node=49231.7
       1    4240    5180
Encroach Node=48480.5
       1    4250    5180
Encroach Node=48196.5
       1    4300    5320
Encroach Node=48183.0
       1    4300    5320
Encroach Node=48169.5
       1    4300    5320
Encroach Node=47607.9
       1    4150    5435
Encroach Node=46939.0
       1    4025    5460
Encroach Node=46594.8
       1    3950    5400
Encroach Node=46560.8
       1    3950    5400
Encroach Node=46526.8
       1    3950    5400
Encroach Node=46499.9
       1    3925    5425
Encroach Node=46489.4
       1    3925    5425
Encroach Node=46478.9
       1    3925    5425
Encroach Node=45952.3
       1    3925    5355
Encroach Node=45161.4
       1    3620    5360
Encroach Node=44549.9
       1    3580    5475
Encroach Node=44143.3
       1    3600    5600
Encroach Node=43215.5
       1    3850    5250
Encroach Node=42471.0
       1    4080    5330
Encroach Node=41863.8
       1    3880 5332.97
Encroach Node=41285.4
       1    3870    5400
Encroach Node=41243.9
       1    3870    5400
Encroach Node=41202.4
       1    3870    5400
Encroach Node=41197.2
       1    3870    5400
Encroach Node=41185.7
       1    3870    5400
Encroach Node=40951.8
       1    3850 5652.33
Encroach Node=40919.3
       1    3850 5652.33
Encroach Node=40886.8
       1    3850 5652.33
Encroach Node=40846.9
       1    3790    5866
Encroach Node=40726.2
       1    3790    5866
Encroach Node=40605.5
       1    3790    5866
Encroach Node=40584.6
       1    3730 5682.26
Encroach Node=40550.1
       1    3730 5682.26
Encroach Node=40515.6
       1    3730 5682.26
Encroach Node=39969.8
       1    3747    5350
Encroach Node=39188.6
       1    3580    5410
Encroach Node=38170.2
       1    3650    5200
Encroach Node=37258.6
       1    4000    5240
Encroach Node=36107.2
       1    4000    5450
Encroach Node=35434.7
       1    4730    5275
Encroach Node=35045.7
       1    4935    5075
Encroach Node=35025.9
       1    4935    5075
Encroach Node=35006.1
       1    4935    5075
Encroach Node=34984.3
       1  4925.5  5110.5
Encroach Node=34927.3
       1  4925.5  5110.5
Encroach Node=34870.3
       1  4925.5  5110.5
Encroach Node=33920.1
       1    4825    5175
Encroach Node=32749.8
       1    4825    5175
Encroach Node=31824.3
       1    4900    5100
Encroach Node=30679.1
       1    4850    5250
Encroach Node=30099.1
       1    4865    5125
Encroach Node=29757.8
       1    4850    5150
Encroach Node=29731.3
       1    4850    5150
Encroach Node=29704.8
       1    4850    5150
Encroach Node=28983.7
       1    4900    5070
Encroach Node=28387.3
       1    4880    5120
Encroach Node=27992.0
       1 4863.86  5046.5
Encroach Node=27567.7
       1    4900    5100
Encroach Node=27317.0
       1    4850    5130
Encroach Node=27306.0
       1    4850    5130
Encroach Node=27304.8
       1    4850    5130
Encroach Node=27242.8
       1    4850    5130
Encroach Node=27180.8
       1    4850    5130
Encroach Node=27179.0
       1    4850    5130
Encroach Node=27167.5
       1    4850    5130
Encroach Node=26466.1
       1    4880    5100
Encroach Node=25982.8
       1    4836    5075
Encroach Node=25318.4
       1    4888    5150
Encroach Node=24564.2
       1    4850    5086
Encroach Node=23984.6
       1    4810    5100
Encroach Node=23286.2
       1    4908    5087
Encroach Node=22973.4
       1  4918.6    5077
Encroach Node=22951.4
       1  4918.6    5077
Encroach Node=22929.4
       1  4918.6    5077
Encroach Node=22630.3
       1  4920.3  5065.3
Encroach Node=22609.0
       1  4920.3  5065.3
Encroach Node=22587.7
       1  4920.3  5065.3
Encroach Node=22186.8
       1    4920    5080
Encroach Node=21829.0
       1  4935.6  5095.6
Encroach Node=21589.8
       1    4930    5070
Encroach Node=21362.0
       1    4910    5080
Encroach Node=21333.0
       1    4910    5080
Encroach Node=21304.0
       1    4910    5080
Encroach Node=21010.4
       1    4867    5145
Encroach Node=20948.9
       1    4867    5145
Encroach Node=20887.4
       1    4867    5145
Encroach Node=20880.6
       1    4885    5135
Encroach Node=20869.6
       1    4885    5135
Encroach Node=20858.6
       1    4885    5135
Encroach Node=19860.0
       1 4892.45    5239
Encroach Node=18597.4
       1  4876.5    5092
Encroach Node=18107.1
       1  4893.8  5121.2
Encroach Node=17130.3
       1  4908.6  5063.6
Encroach Node=16004.0
       1  4948.3    5155
Encroach Node=15045.6
       1    4913  5102.3
Encroach Node=13937.2
       1    4850    5075
Encroach Node=13341.9
       1    4800    5080
Encroach Node=12945.5
       1    4890    5110
Encroach Node=12935.0
       1    4890    5110
Encroach Node=12931.7
       1    4890    5111
Encroach Node=12904.8
       1    4890    5111
Encroach Node=12877.9
       1    4890    5111
Encroach Node=12117.3
       1    4910    5110
Encroach Node=10905.1
       1    4910    5085
Encroach Node=9879.2
       1    4870  5083.8
Encroach Node=8777.0
       1  4904.7    5500
Encroach Node=8024.4
       1    4880    5120
Encroach Node=6779.3
       1    4880    5120
Encroach Node=5748.4
       1    4900    5100
Encroach Node=4492.0
       1    4900    5170
Encroach Node=3597.9
       1    4850    5110
Encroach Node=2709.4
       1    4880    5120
Encroach Node=1695.9
       1    4830    5070
Encroach Node=678.7
       1    4930    5150
Computation Interval=1HOUR
Output Interval=1HOUR
Run HTab= 0
Run UNet= 0
Run PostProcess= 0
UNET Theta= 1
UNET ZTol= 0.02
UNET ZSATol= 0.1
UNET MxIter= 20
UNET MaxInSteps= 20
UNET DtIC= 0
UNET DtMin= 0
UNET MaxCRTS= 20
UNET WFStab= 2
UNET SFStab= 1
UNET WFX= 1
UNET SFX= 1
UNET Convert EG Bridges=-1
UNET Use Existing IB Tables=-1
Instantaneous Interval=1HOUR
Write IC File= 0
Write Velocity= 0
Write Detailed= 0

--- P118-00-00.p01 (plan) ---

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Plan Title=FEMA Effective June 2007
Short Identifier=FEMAeff0607
Geom File= g01
Flow File= f01
Interactive Comp Mode
Encroach Param= -1, 0, 0, 0

--- P118-00-00.f02 (steady flow) ---

Flow Title= Floodway
Number of Profiles= 2
Profile Names=1PCT_100yr, 1PCTFloodway_100yrFW
River Rch & RM=P118-00-00,P118-00-00_0007,104245.4
    1172    1172
River Rch & RM=P118-00-00,P118-00-00_0007,103600.6
    1234    1234
River Rch & RM=P118-00-00,P118-00-00_0007,102844.1
    1292    1292
River Rch & RM=P118-00-00,P118-00-00_0007,102169
    1349    1349
River Rch & RM=P118-00-00,P118-00-00_0007,101525.5
    1442    1442
River Rch & RM=P118-00-00,P118-00-00_0007,100544.6
    1545    1545
River Rch & RM=P118-00-00,P118-00-00_0007,99524.3
    1616    1616
River Rch & RM=P118-00-00,P118-00-00_0007,98862.7
    1670    1670
River Rch & RM=P118-00-00,P118-00-00_0007,98434.7
    1758    1758
River Rch & RM=P118-00-00,P118-00-00_0007,97617.6
    1897    1897
River Rch & RM=P118-00-00,P118-00-00_0007,96497.8
    2061    2061
River Rch & RM=P118-00-00,P118-00-00_0007,95272.1
    2209    2209
River Rch & RM=P118-00-00,P118-00-00_0007,94253.5
    2342    2342
River Rch & RM=P118-00-00,P118-00-00_0007,93387.8
    2451    2451
River Rch & RM=P118-00-00,P118-00-00_0007,92719.1
    2628    2628
River Rch & RM=P118-00-00,P118-00-00_0007,91689.3
    2748    2748
River Rch & RM=P118-00-00,P118-00-00_0007,91029.5
    2924    2924
River Rch & RM=P118-00-00,P118-00-00_0007,90112.3
    3083    3083
River Rch & RM=P118-00-00,P118-00-00_0007,89332.1
    3242    3242
River Rch & RM=P118-00-00,P118-00-00_0007,88590.5
    3506    3506
River Rch & RM=P118-00-00,P118-00-00_0007,87434.8
    3713    3713
River Rch & RM=P118-00-00,P118-00-00_0007,86591.9
    3841    3841
River Rch & RM=P118-00-00,P118-00-00_0007,86213.8
    3982    3982
River Rch & RM=P118-00-00,P118-00-00_0007,85559.7
    4251    4251
River Rch & RM=P118-00-00,P118-00-00_0007,84594.2
    5888    5888
River Rch & RM=P118-00-00,P118-00-00_0007,83450.7
    6309    6309
River Rch & RM=P118-00-00,P118-00-00_0007,73423.3
    6566    6566
River Rch & RM=P118-00-00,P118-00-00_0007,67511.6
    6576    6576
River Rch & RM=P118-00-00,P118-00-00_0007,65955.8
    6586    6586
River Rch & RM=P118-00-00,P118-00-00_0007,64273.7
    7681    7681
River Rch & RM=P118-00-00,P118-00-00_0007,60625.3
    7871    7871
River Rch & RM=P118-00-00,P118-00-00_0007,55557.7
    8042    8042
River Rch & RM=P118-00-00,P118-00-00_0007,51096.9
    8219    8219
River Rch & RM=P118-00-00,P118-00-00_0007,46594.8
    8316    8316
River Rch & RM=P118-00-00,P118-00-00_0007,44143.3
    9539    9539
River Rch & RM=P118-00-00,P118-00-00_0007,43215.5
    9539    9539
River Rch & RM=P118-00-00,P118-00-00_0007,36107.2
   10699   10699
River Rch & RM=P118-00-00,P118-00-00_0007,29757.8
   11271   11271
River Rch & RM=P118-00-00,P118-00-00_0007,23286.2
   11300   11300
River Rch & RM=P118-00-00,P118-00-00_0007,22973.4
   11828   11828
River Rch & RM=P118-00-00,P118-00-00_0007,19860
   12311   12311
River Rch & RM=P118-00-00,P118-00-00_0007,17130.3
   12517   12517
River Rch & RM=P118-00-00,P118-00-00_0007,16004
   13094   13094
River Rch & RM=P118-00-00,P118-00-00_0007,12945.5
   13489   13489
River Rch & RM=P118-00-00,P118-00-00_0007,10905.1
   13917   13917
River Rch & RM=P118-00-00,P118-00-00_0007,8777
   14550   14550
River Rch & RM=P118-00-00,P118-00-00_0007,5748.4
   15017   15017
River Rch & RM=P118-00-00,P118-00-00_0007,3597.9
   15674   15674
Boundary for River Rch & Prof#=P118-00-00,P118-00-00_0007, 1
Up Type= 0
Dn Type= 3
Dn Slope= 0.00280
Boundary for River Rch & Prof#=P118-00-00,P118-00-00_0007, 2
Up Type= 0
Dn Type= 3
Dn Slope= 0.00280

--- P118-00-00.f01 (steady flow) ---

Flow Title= FEMA Effective June 2007
Number of Profiles= 4
Profile Names=10PCT_10yr, 2PCT_50yr, 1PCT_100yr, 0.2PCT_500yr
River Rch & RM=P118-00-00,P118-00-00_0007,104245.4
     679    1007    1172    2023
River Rch & RM=P118-00-00,P118-00-00_0007,103600.6
     715    1061    1234    2109
River Rch & RM=P118-00-00,P118-00-00_0007,102844.1
     749    1112    1292    2189
River Rch & RM=P118-00-00,P118-00-00_0007,102169
     783    1162    1349    2269
River Rch & RM=P118-00-00,P118-00-00_0007,101525.5
     838    1243    1442    2395
River Rch & RM=P118-00-00,P118-00-00_0007,100544.6
     899    1333    1545    2534
River Rch & RM=P118-00-00,P118-00-00_0007,99524.3
     940    1396    1616    2628
River Rch & RM=P118-00-00,P118-00-00_0007,98862.7
     972    1443    1670    2699
River Rch & RM=P118-00-00,P118-00-00_0007,98434.7
    1024    1520    1758    2815
River Rch & RM=P118-00-00,P118-00-00_0007,97617.6
    1106    1642    1897    2994
River Rch & RM=P118-00-00,P118-00-00_0007,96497.8
    1204    1787    2061    3204
River Rch & RM=P118-00-00,P118-00-00_0007,95272.1
    1291    1917    2209    3389
River Rch & RM=P118-00-00,P118-00-00_0007,94253.5
    1370    2034    2342    3555
River Rch & RM=P118-00-00,P118-00-00_0007,93387.8
    1435    2130    2451    3689
River Rch & RM=P118-00-00,P118-00-00_0007,92719.1
    1540    2286    2628    3904
River Rch & RM=P118-00-00,P118-00-00_0007,91689.3
    1611    2393    2748    4049
River Rch & RM=P118-00-00,P118-00-00_0007,91029.5
    1716    2549    2924    4259
River Rch & RM=P118-00-00,P118-00-00_0007,90112.3
    1811    2689    3083    4447
River Rch & RM=P118-00-00,P118-00-00_0007,89332.1
    1906    2830    3242    4633
River Rch & RM=P118-00-00,P118-00-00_0007,88590.5
    2063    3064    3506    4938
River Rch & RM=P118-00-00,P118-00-00_0007,87434.8
    2186    3247    3713    5173
River Rch & RM=P118-00-00,P118-00-00_0007,86591.9
    2263    3361    3841    5318
River Rch & RM=P118-00-00,P118-00-00_0007,86213.8
    2347    3486    3982    5476
River Rch & RM=P118-00-00,P118-00-00_0007,85559.7
    2508    3726    4251    5776
River Rch & RM=P118-00-00,P118-00-00_0007,84594.2
    3634    5268    5888    7723
River Rch & RM=P118-00-00,P118-00-00_0007,83450.7
    4153    5617    6309    8137
River Rch & RM=P118-00-00,P118-00-00_0007,73423.3
    4484    5828    6566    8386
River Rch & RM=P118-00-00,P118-00-00_0007,67511.6
    4484    5840    6576    8547
River Rch & RM=P118-00-00,P118-00-00_0007,65955.8
    4484    5852    6586    8724
River Rch & RM=P118-00-00,P118-00-00_0007,64273.7
    5125    6788    7681   10335
River Rch & RM=P118-00-00,P118-00-00_0007,60625.3
    5371    7004    7871   10556
River Rch & RM=P118-00-00,P118-00-00_0007,55557.7
    5597    7200    8042   10754
River Rch & RM=P118-00-00,P118-00-00_0007,51096.9
    5835    7404    8219   10958
River Rch & RM=P118-00-00,P118-00-00_0007,46594.8
    5969    7517    8316   11071
River Rch & RM=P118-00-00,P118-00-00_0007,44143.3
    6604    8703    9539   12194
River Rch & RM=P118-00-00,P118-00-00_0007,43215.5
    6604    8703    9539   12340
River Rch & RM=P118-00-00,P118-00-00_0007,36107.2
    7578    9853   10699   13748
River Rch & RM=P118-00-00,P118-00-00_0007,29757.8
    8019   10614   11271   13792
River Rch & RM=P118-00-00,P118-00-00_0007,23286.2
    8041   10652   11300   13794
River Rch & RM=P118-00-00,P118-00-00_0007,22973.4
    8285   11049   11828   14563
River Rch & RM=P118-00-00,P118-00-00_0007,19860
    8506   11409   12311   15271
River Rch & RM=P118-00-00,P118-00-00_0007,17130.3
    8599   11560   12517   15573
River Rch & RM=P118-00-00,P118-00-00_0007,16004
    8857   11985   13094   16429
River Rch & RM=P118-00-00,P118-00-00_0007,12945.5
    9031   12274   13489   17019
River Rch & RM=P118-00-00,P118-00-00_0007,10905.1
    9218   12584   13917   17661
River Rch & RM=P118-00-00,P118-00-00_0007,8777
    9491   13040   14550   18617
River Rch & RM=P118-00-00,P118-00-00_0007,5748.4
    9690   13373   15017   19327
River Rch & RM=P118-00-00,P118-00-00_0007,3597.9
    9966   13840   15674   20334
Boundary for River Rch & Prof#=P118-00-00,P118-00-00_0007, 1
Up Type= 0
Dn Type= 3
Dn Slope= 0.00280
Boundary for River Rch & Prof#=P118-00-00,P118-00-00_0007, 2
Up Type= 0
Dn Type= 3
Dn Slope= 0.00280
Boundary for River Rch & Prof#=P118-00-00,P118-00-00_0007, 3
Up Type= 0
Dn Type= 3
Dn Slope= 0.00280
Boundary for River Rch & Prof#=P118-00-00,P118-00-00_0007, 4
Up Type= 0
Dn Type= 3
Dn Slope= 0.00280

--- P118-00-00.g01 (geometry) ---

Geom Title=P118-00-00 June 2007
Version=Version 3.0.1  Mar 2001

River Reach=P118-00-00      ,P118-00-00_0007
Reach XY= 30
       3084639.1     13899135.45       3089410.5       13899307.
       3098400.6     13891556.08      3103880.78      13893049.2
      3106682.38     13890825.24      3111881.63     13889482.98
       3115614.5       13890118.      3119961.75       13889521.
      3122604.82     13890863.55       3124601.5       13890798.
      3127217.75       13887978.       3126933.9     13884659.25
      3127995.33     13883106.23      3127525.25       13880675.
      3128960.75       13879236.      3130838.75       13878740.
      3133093.25       13880143.      3135305.25       13879700.
       3137325.5       13878001.      3138855.59     13878150.34
      3139916.94     13876279.14      3144361.75       13876150.
      3149892.25       13873617.      3153093.75       13874858.
      3155078.75       13874282.      3155622.25       13875019.
        3157020.     13874676.64      3157361.25       13873626.
      3159377.56     13873854.88      3161571.25       13871495.

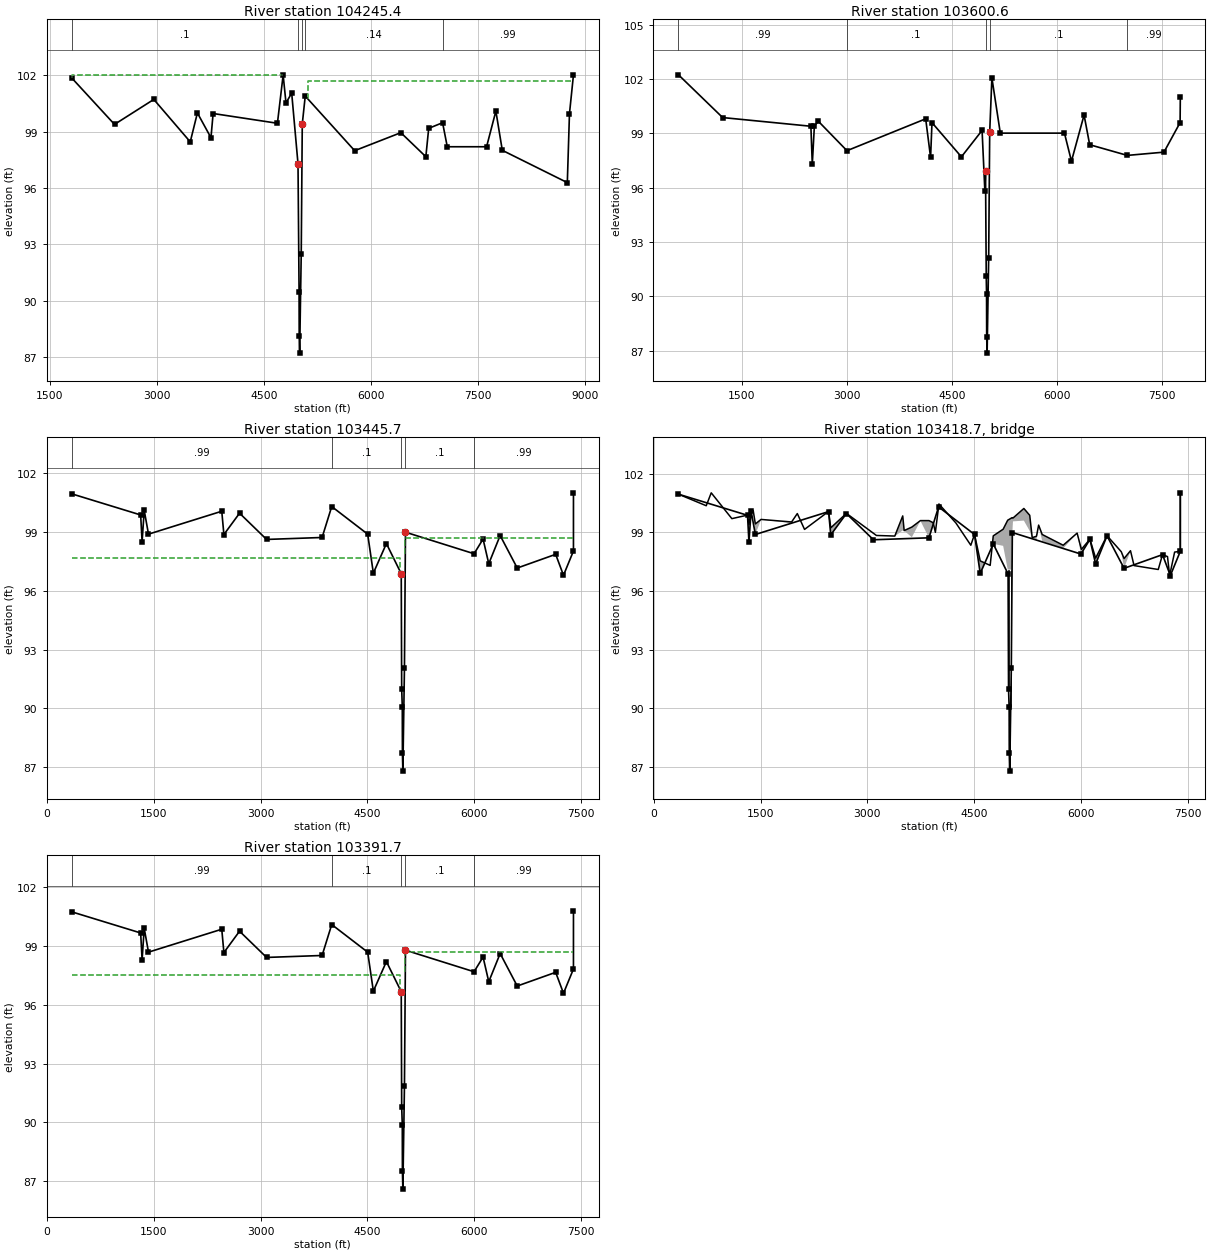
Type RM Length L Ch R = 1 ,104245.4,656.5,644.8,617.4
BEGIN DESCRIPTION:
Cross Section 104245.4-Interpolated
END DESCRIPTION:
XS GIS Cut Line= 5
      3084466.87     13902322.01      3084639.08     13899257.13
      3084639.08     13898985.72      3084667.65     13897900.09
      3083773.79     13895462.82
#Sta/Elev= 30
  1808.6  101.86  2408.6   99.38  2958.6  100.71  3468.6   98.45  3568.6   99.99
  3758.6   98.67  3788.6   99.96  4688.6   99.44  4768.6  102.01  4808.6  100.52
  4888.3  101.05  4976.7   97.28  4991.6   90.46  4993.3   88.11  4999.6    87.2
  5021.8   92.46  5036.4    99.4  5077.9  100.89  5769.7   97.98  6415.7   98.94
  6765.7   97.66  6805.7   99.17    7000   99.47  7065.7   98.19  7615.7   98.19
  7745.7  100.09  7835.7      98  8745.7   96.28  8775.7   99.95  8831.7  102.02
#Mann= 5 , 1 , 0
  1808.6      .1       0  4976.7     .04       0  5036.4      .1       0
  5077.9     .14       0    7000     .99       0
#XS Ineff= 2 , 0
       0  4768.6  102.01  5118.3       0  101.68
Permanent Ineff=
       F       F
Bank Sta=4976.7,5036.4
XS Rating Curve= 0
Exp/Cntr=.3,.1

Type RM Length L Ch R = 1 ,103600.6,138.1,154.9,189.1
BEGIN DESCRIPTION:
Cross Section 103600.6-Interpolated
END DESCRIPTION:
XS GIS Cut Line= 6
       3084401.1     13903444.72      3084822.47     13902386.51
      3085032.99     13901554.97      3085268.57     13899891.95
      3085206.63     13898145.39      3085246.54     13896412.59
#Sta/Elev= 30
   596.2  102.24  1226.2   99.88  2485.2    99.4  2505.2   97.31  2535.2   99.43
    2593   99.67    3000   98.05    4123   99.81    4193   97.68    4213    99.6
  4632.6   97.71  4927.7   99.17  4967.7    95.8  4976.7   96.95  4987.1   91.11
  4991.6   90.13  4993.3   87.78  4999.6   86.87  5021.8   92.13  5036.4   99.07
  5067.7  102.07  5187.7   99.02  6102.9   99.02  6202.9   97.47  6382.9  100.02
  6462.9   98.38    7000   97.79  7522.9   97.97  7752.9    99.6  7756.2     101
#Mann= 5 , 1 , 0
   596.2     .99       0    3000      .1       0  4976.7     .04       0
  5036.4      .1       0    7000     .99       0
#XS Ineff= 2 , 0
       0  4252.4    98.9    5123       0   99.81
Permanent Ineff=
       F       F
Bank Sta=4976.7,5036.4
XS Rating Curve= 0
Exp/Cntr=.5,.3

Type RM Length L Ch R = 1 ,103445.7,54,54,54
BEGIN DESCRIPTION:
Upstream Section of Bridge/Culvert/Weir
END DESCRIPTION:
XS GIS Cut Line= 6
       3084584.2     13903648.42      3085299.03     13902283.06
      3085412.38     13899877.47      3085422.32     13899543.47
      3085472.23     13898541.92      3085537.44       13896778.
#Sta/Elev= 30
   345.3  100.96  1315.3   99.88  1335.3   98.51  1365.3  100.11  1425.3    98.9
  2454.8  100.07  2484.8   98.88  2704.8   99.97  3084.8   98.63  3864.8   98.73
    4000  100.31    4505    98.9    4585   96.91  4768.2   98.42  4976.7   96.88
    4983   91.01  4991.6   90.06  4993.3   87.71  4999.6    86.8  5021.8   92.06
  5036.4      99    6000    97.9  6126.6   98.65  6206.6   97.39  6366.6   98.83
  6606.6   97.17  7146.6   97.87  7256.6    96.8  7396.6   98.04  7396.8  101.01
#Mann= 5 , 1 , 0
   345.3     .99       0    4000      .1       0  4976.7     .04       0
  5036.4      .1       0    6000     .99       0
#XS Ineff= 2 , 0
       0    4961    97.7 5034.11       0    98.7
Permanent Ineff=
       F       F
Bank Sta=4976.7,5036.4
XS Rating Curve= 0
Exp/Cntr=.5,.3

Type RM Length L Ch R = 3 ,103418.7,,,
BEGIN DESCRIPTION:
MOSIELLE ROAD
Structure ID: P18-51
END DESCRIPTION:
Bridge Culvert--1,0,-1,-1, 0
Deck Dist Width WeirC Skew NumUp NumDn MinLoCord MaxHiCord MaxSubmerge Is_Ogee
10,34,2.6,0, 60, 60, , , .95, 0, 1,1,,
   345.3   735.3   805.3  1095.3  1315.3  1335.3  1365.3  1395.3  1425.3  1505.3
  1934.8  2014.8  2116.4  2454.8  2484.8  2704.8  3126.4  3384.8  3496.4  3516.4
  3624.8  3744.8  3864.8  3924.8  3954.8  4004.8    4243    4453    4505    4585
    4725  4768.2  4907.3 4971.21  5032.4  5036.4  5045.3  5198.2  5280.8  5315.7
  5375.8  5405.8  5455.8  5750.9  5946.6  6006.6  6126.6  6206.6  6366.6  6566.6
  6606.6  6696.6  6746.6  7086.6  7146.6  7216.6  7246.6  7316.6  7396.6  7396.8
  100.95  100.36  101.02    99.7   99.88    99.4  100.11  100.11   99.43   99.66
   99.53   99.96   99.15  100.07   99.23   99.97   98.84   98.81   99.84   99.09
   99.27    99.6    99.6   99.49      99  100.45   99.48   98.34    98.9   97.54
   97.31   98.82   99.16   99.62   99.75   99.74   99.73  100.22   99.87   98.73
    98.8   99.37   98.89   98.34   98.96   98.13   98.65   97.68   98.83   98.01
   97.66   98.06    97.3    97.1   97.86   97.76   96.79   97.99   98.03     101
  100.95  100.35  101.01   99.69   99.87    98.5   100.1   100.1   98.89   99.65
   99.11   99.95   99.14  100.06   98.87   99.96   98.83    98.8    99.1   99.08
   98.75   99.59   98.72   99.48   98.97  100.44   98.85   98.34   98.89    96.9
   97.22   98.41   98.31    97.1   97.09   98.99   99.56    99.6   99.07   98.64
   98.51   99.36   98.56   98.05   98.95   97.76   98.64   97.38   98.82      98
   97.16   98.05   97.29    97.1   97.86   97.76   96.79   97.99   98.03     101
   345.3   735.3   805.3  1095.3  1315.3  1335.3  1365.3  1395.3  1425.3  1505.3
  1934.8  2014.8  2116.4  2454.8  2484.8  2704.8  3126.4  3384.8  3496.4  3516.4
  3624.8  3744.8  3864.8  3924.8  3954.8  4004.8    4243    4453    4505    4585
    4725  4768.2  4907.3 4971.21  5032.4  5036.4  5045.3  5198.2  5280.8  5315.7
  5375.8  5405.8  5455.8  5750.9  5946.6  6006.6  6126.6  6206.6  6366.6  6566.6
  6606.6  6696.6  6746.6  7086.6  7146.6  7216.6  7246.6  7316.6  7396.6  7396.8
  100.95  100.36  101.02    99.7   99.88    99.4  100.11  100.11   99.43   99.66
   99.53   99.96   99.15  100.07   99.23   99.97   98.84   98.81   99.84   99.09
   99.27    99.6    99.6   99.49      99  100.45   99.48   98.34    98.9   97.54
   97.31   98.82   99.16   99.62   99.75   99.74   99.73  100.22   99.87   98.73
    98.8   99.37   98.89   98.34   98.96   98.13   98.65   97.68   98.83   98.01
   97.66   98.06    97.3    97.1   97.86   97.76   96.79   97.99   98.03     101
  100.76  100.16  100.82    99.5   99.68   98.31   99.91   99.91    98.7   99.46
   98.92   99.76   98.95   99.87   98.68   99.77   98.64   98.61   98.91   98.89
   98.56    99.4   98.53   99.29   98.78  100.25   98.66   98.15    98.7   96.71
   97.03   98.22   98.12   96.91    96.9    98.8   99.37   99.41   98.88   98.45
   98.32   99.17   98.37   97.86   98.76   97.57   98.45   97.19   98.63   97.81
   96.97   97.86    97.1   96.91   97.67   97.57    96.6    97.8   97.84  100.81
Pier Skew, UpSta & Num, DnSta & Num=  ,4983, 2 ,4983, 2 , 0 , 0 , 0 ,,
     1.2     1.2
      90    98.2
     1.2     1.2
   89.81   98.01
Pier Skew, UpSta & Num, DnSta & Num=  ,5013.5, 2 ,5013.5, 2 , 0 , 0 , 0 ,,
     1.2     1.2
   88.88   98.28
     1.2     1.2
   88.69   98.09
Abutment Skew #Up #Dn= , 2 , 2
  4971.1  4974.6
   97.12   96.96
  4971.1  4974.6
   96.93   96.77
Abutment Skew #Up #Dn= , 2 , 2
  5029.3 5032.49
   95.62   97.25
  5029.3 5032.49
   95.43   97.06
BR Coef= 1 , 1 , 0 ,1.25, 0 ,,,.8,-1,2,0,
WSPro=,,,, 1 ,,,, 0 ,,,, 0 ,,,,-1 ,-1 ,-1 , 0 , 0 , 0 , 0 , 0
BR U #Sta/Elev= 30
   345.3  100.95  1315.3   99.87  1335.3    98.5  1365.3   100.1  1425.3   98.89
  2454.8  100.06  2484.8   98.87  2704.8   99.96  3084.8   98.62  3864.8   98.72
    4000   100.3    4505   98.89    4585    96.9  4768.2   98.41  4976.7   96.87
    4983      91  4991.6   90.05  4993.3    87.7  4999.6   86.79  5021.8   92.05
  5036.4   98.99    6000   97.89  6126.6   98.64  6206.6   97.38  6366.6   98.82
  6606.6   97.16  7146.6   97.86  7256.6   96.79  7396.6   98.03  7396.8     101
BR U #Mann= 5
   345.3     .99    4000      .1  4976.7     .04  5036.4      .1    6000     .99
BR U Banks=4976.7,5036.4
BR D #Sta/Elev= 30
   345.3  100.76  1315.3   99.68  1335.3   98.31  1365.3   99.91  1425.3    98.7
  2454.8   99.87  2484.8   98.68  2704.8   99.77  3084.8   98.43  3864.8   98.53
    4000  100.11    4505    98.7    4585   96.71  4768.2   98.22  4976.7   96.68
    4983   90.81  4991.6   89.86  4993.3   87.51  4999.6    86.6  5021.8   91.86
  5036.4    98.8    6000    97.7  6126.6   98.45  6206.6   97.19  6366.6   98.63
  6606.6   96.97  7146.6   97.67  7256.6    96.6  7396.6   97.84  7396.8  100.81
BR D #Mann= 5
   345.3     .99    4000      .1  4976.7     .04  5036.4      .1    6000     .99
BR D Banks=4976.7,5036.4
BC Design=,, 0 ,, 0 ,,,,,,

Type RM Length L Ch R = 1 ,103391.7,547.6,547.6,547.6
BEGIN DESCRIPTION:
Downstream Section of Bridge/Culvert/Weir
END DESCRIPTION:
XS GIS Cut Line= 6
      3084638.14     13903650.93      3085352.97     13902285.58
      3085466.32     13899879.99      3085476.26     13899545.99
      3085526.17     13898544.44      3085591.38     13896780.51
#Sta/Elev= 30
   345.3  100.75  1315.3   99.67  1335.3    98.3  1365.3    99.9  1425.3   98.69
  2454.8   99.86  2484.8   98.67  2704.8   99.76  3084.8   98.42  3864.8   98.52
    4000   100.1    4505   98.69    4585    96.7  4768.2   98.21  4976.7   96.67
    4983    90.8  4991.6   89.85  4993.3    87.5  4999.6   86.59  5021.8   91.85
  5036.4   98.79    6000   97.69  6126.6   98.44  6206.6   97.18  6366.6   98.62
  6606.6   96.96  7146.6   97.66  7256.6   96.59  7396.6   97.83  7396.8   100.8
#Mann= 5 , 1 , 0
   345.3     .99       0    4000      .1       0  4976.7     .04       0
  5036.4      .1       0    6000     .99       0
#XS Ineff= 2 , 0
       0    4961    97.5 5034.11       0    98.7
Permanent Ineff=
       F       F
Bank Sta=4976.7,5036.4
XS Rating Curve= 0
Exp/Cntr=.5,.3