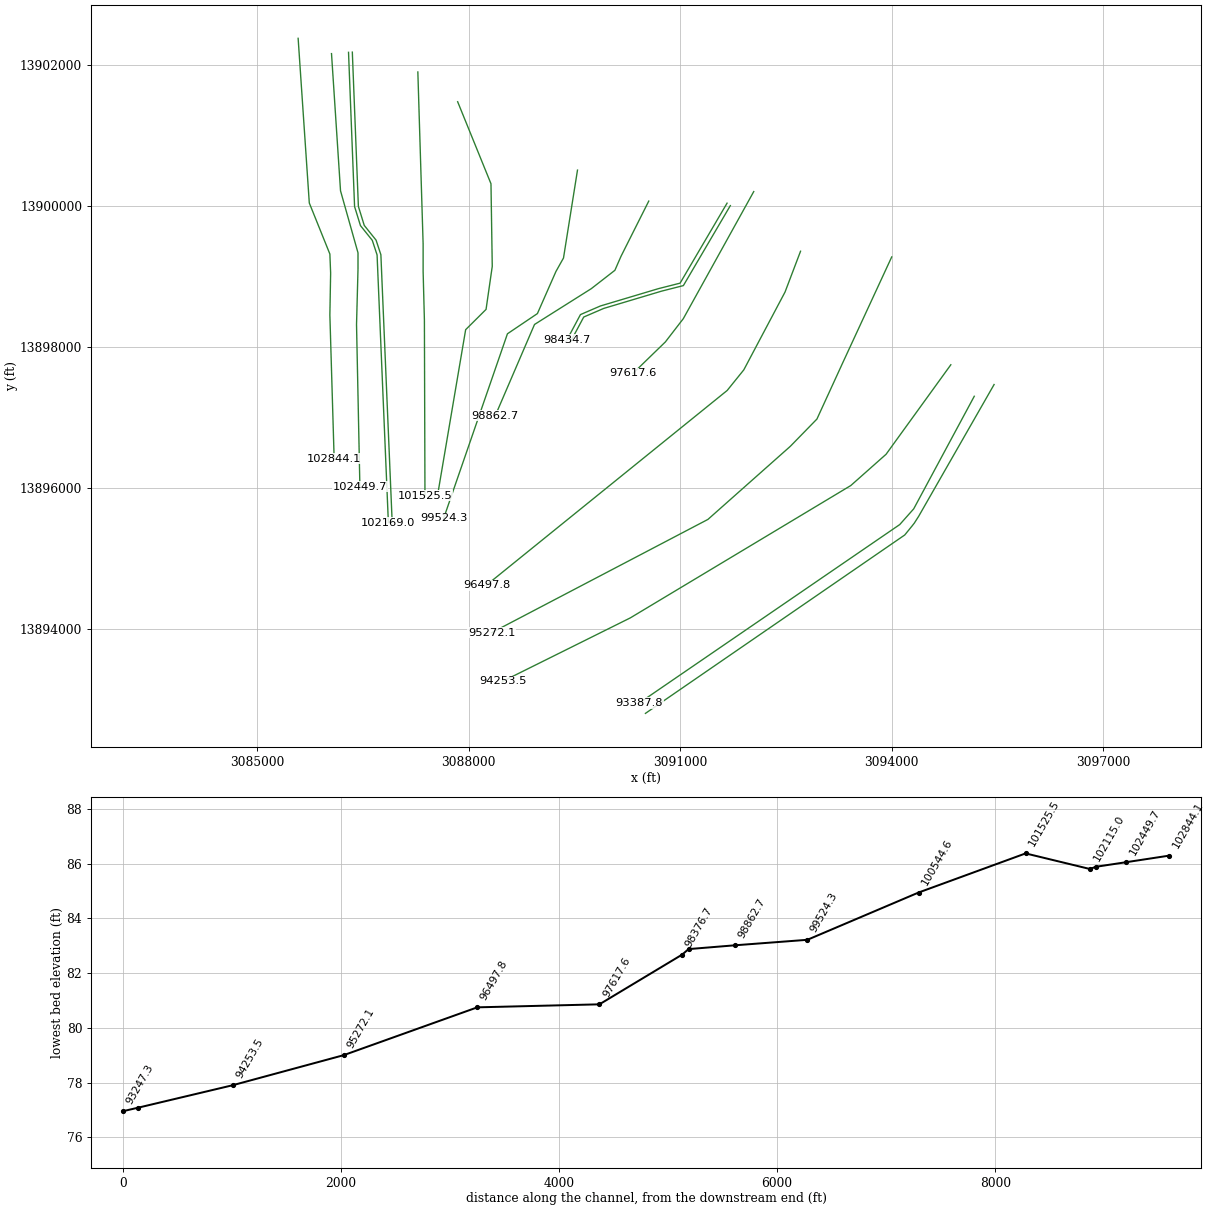
HEC-RAS study P118-00-00.PRJ: P118-00-00

--- P118-00-00.g01 (geometry) --- (continued)

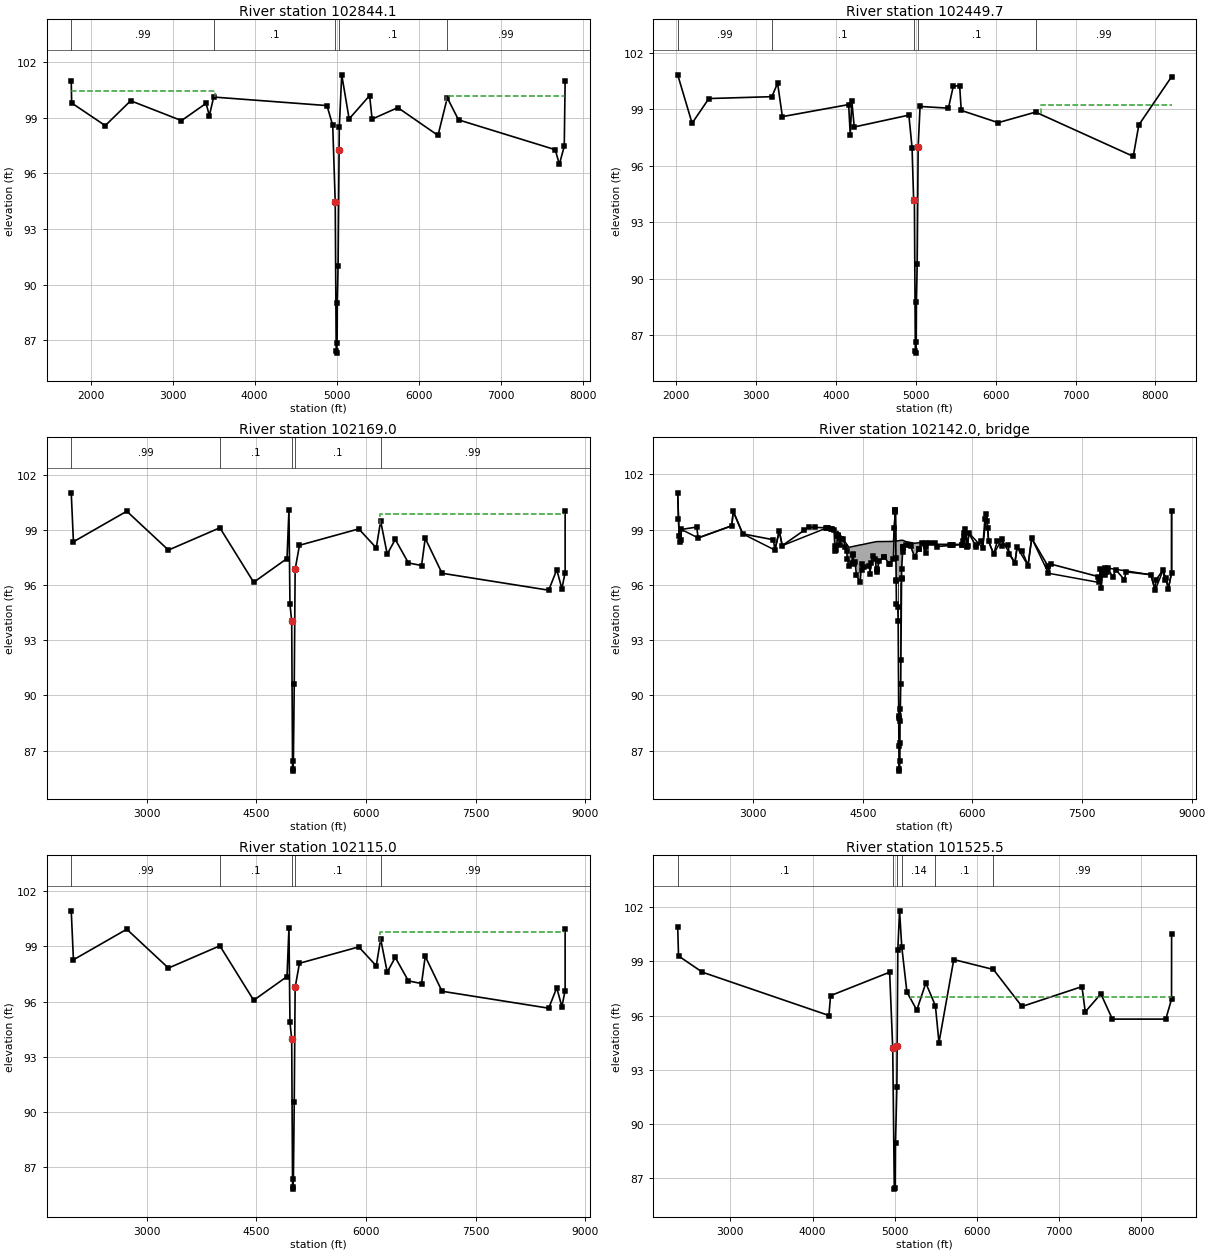
Type RM Length L Ch R = 1 ,102844.1,411.4,394.4,366.8
BEGIN DESCRIPTION:
Cross Section 102844.1-Interpolated
END DESCRIPTION:
XS GIS Cut Line= 6
       3085584.3     13902375.42      3085742.54     13900041.32
      3086034.19      13899317.6      3086044.99     13899047.55
      3086034.19     13898453.45      3086094.92     13896413.55
#Sta/Elev= 30
  1762.5     101  1767.5    99.8  2177.5   98.58  2487.5   99.92  3107.5   98.85
  3407.5   99.78  3447.5   99.12    3500  100.12  4882.3   99.66  4952.3   98.59
  4982.9   94.45  4994.7    86.4  5000.4    86.3  5006.1   86.87  5008.4      89
  5017.8   91.02  5030.1   97.26  5032.3   98.48  5062.3  101.32  5152.5   98.94
  5402.5   100.2  5432.5   98.93  5746.7   99.55  6236.7   98.05    6350  100.08
  6486.7   98.89  7666.7   97.28  7716.7   96.49  7776.7   97.46  7787.5     101
#Mann= 5 , 1 , 0
  1762.5     .99       0    3500      .1       0  4982.9     .04       0
  5030.1      .1       0    6350     .99       0
#XS Ineff= 2 , 0
       0  3517.5  100.45  6336.7       0  100.19
Permanent Ineff=
       F       F
Bank Sta=4982.9,5030.1
XS Rating Curve= 0
Exp/Cntr=.3,.1

Type RM Length L Ch R = 1 ,102449.7,224.4,280.7,318.5
BEGIN DESCRIPTION:
Cross Section 102449.7-Interpolated
END DESCRIPTION:
XS GIS Cut Line= 6
       3086057.4     13902158.98       3086185.2     13900214.01
      3086432.94     13899334.54      3086432.94     13899099.19
      3086412.12     13898317.02      3086459.83     13896017.48
#Sta/Elev= 30
    2021  100.84    2201   98.27    2411   99.58    3200   99.68    3271   100.4
    3331   98.62  4160.2   99.26  4180.2   97.66  4200.2   99.43  4230.2   98.07
  4913.9    98.7  4953.9   96.97  4973.9   94.14  4982.9   94.21  4994.7   86.16
  5000.4   86.06  5006.1   86.63  5008.4   88.76  5017.8   90.78  5030.1   97.02
  5053.9   99.16  5409.2   99.07  5469.2  100.23  5549.2  100.27  5569.2   98.95
  6031.7    98.3    6500   98.86  7721.7   96.51  7791.7   98.18  8201.7  100.74
#Mann= 5 , 1 , 0
    2021     .99       0    3200      .1       0  4982.9     .04       0
  5030.1      .1       0    6500     .99       0
#XS Ineff= 2 , 0
       0  4200.2   99.43  6561.7       0   99.22
Permanent Ineff=
       F       F
Bank Sta=4982.9,5030.1
XS Rating Curve= 0
Exp/Cntr=.5,.3

Type RM Length L Ch R = 1 ,102169.0,54,54,54
BEGIN DESCRIPTION:
Upstream Section of Bridge/Culvert/Weir
END DESCRIPTION:
XS GIS Cut Line= 6
      3086298.63     13902177.14      3086384.42     13899990.78
      3086467.58      13899720.9      3086635.31     13899511.85
      3086703.37     13899305.23      3086863.57     13895510.29
#Sta/Elev= 30
    1966  101.01    1996   98.35    2726  100.01    3296    97.9    4000   99.11
  4462.7   96.15  4918.7   97.44  4945.3  100.08  4959.1   94.95  4982.9   94.04
  4994.7   85.99  5000.4   85.89  5006.1   86.46  5017.8   90.61  5030.1   96.85
    5089   98.16  5900.6   99.05  6140.1   98.02    6200   99.48  6290.1   97.68
  6400.1   98.48  6580.1    97.2  6760.1   97.06  6810.1   98.54  7040.1   96.64
  8500.1   95.72  8610.1   96.83  8680.1    95.8  8724.6   96.68  8724.7  100.01
#Mann= 5 , 1 , 0
    1966     .99       0    4000      .1       0  4982.9     .04       0
  5030.1      .1       0    6200     .99       0
#XS Ineff= 2 , 0
       0 4951.41    97.8  6190.1       0   99.84
Permanent Ineff=
       F       F
Bank Sta=4982.9,5030.1
XS Rating Curve= 0
Exp/Cntr=.5,.3

Type RM Length L Ch R = 3 ,102142.0,,,
BEGIN DESCRIPTION:
ANN LOUISE ROAD
Structure ID: P18-50
END DESCRIPTION:
Bridge Culvert--1,0,-1,-1, 0
Deck Dist Width WeirC Skew NumUp NumDn MinLoCord MaxHiCord MaxSubmerge Is_Ogee
10,34,2.6,0, 60, 60, , , .95, 0, 1,1,,
    1966    1986    1996    2016    2246    2706    2726    2856    3296    3356
    3396  4015.9  4105.9  4124.7  4154.7    4228    4308    4358  4462.7  4482.7
  4598.3  4638.3  4688.3  4918.7  4929.3  4945.3  4952.3  4955.7  4959.1  5020.4
    5047    5089  5206.6  5308.4  5358.4  5860.6  5900.6  5930.6  5950.6  6140.1
  6190.1  6220.1  6290.1  6400.1  6580.1  6610.1  6760.1  6810.1  7040.1  7730.1
  7750.1  7760.1  7780.1  7820.1  8440.1  8500.1  8610.1  8680.1  8724.6  8724.7
     101   98.68   98.34   99.01   98.55   99.21     100   98.77   97.89   98.93
   98.13   99.11   98.98    98.6   98.91    98.5   98.04   98.08   98.17   98.18
   98.28   98.31   98.35   98.36   99.11  100.08   98.38   98.38   98.38   98.42
   98.42   98.35   98.26   98.31   98.21    98.2   99.05   98.06   98.82   98.01
   99.84   98.37   97.67   98.47   97.19   98.04   97.05   98.53   96.63   96.13
   96.86   95.85   96.78   96.93   96.55   95.71   96.82   95.79   96.67     100
     101   98.68   98.34   99.01   98.55   99.21     100   98.77   97.89   98.93
   98.13    99.1   98.97   97.82   98.67   98.49   97.01   97.66   96.14   97.16
   96.57   97.59   96.69   97.43    99.1  100.07   97.47    96.2   96.12   96.16
   98.02   98.15   97.53    98.3   97.75   98.19   99.04   98.05   98.81   98.01
   99.84   98.37   97.67   98.47   97.19   98.04   97.05   98.53   96.63   96.13
   96.86   95.85   96.78   96.93   96.55   95.71   96.82   95.79   96.67     100
    1966    1986    1996    2016    2246    2706    2726    2856    3296    3356
    3396  4015.9  4105.9  4124.7  4154.7    4228    4308    4358  4462.7  4482.7
  4598.3  4638.3  4688.3  4918.7  4929.3  4945.3  4952.3  4955.7  4959.1  5020.4
    5047    5089  5206.6  5308.4  5358.4  5860.6  5900.6  5930.6  5950.6  6140.1
  6190.1  6220.1  6290.1  6400.1  6580.1  6610.1  6760.1  6810.1  7040.1  7730.1
  7750.1  7760.1  7780.1  7820.1  8440.1  8500.1  8610.1  8680.1  8724.6  8724.7
     101   98.68   98.34   99.01   98.55   99.21     100   98.77   97.89   98.93
   98.13   99.11   98.98    98.6   98.91    98.5   98.04   98.08   98.17   98.18
   98.28   98.31   98.35   98.36   99.11  100.08   98.38   98.38   98.38   98.42
   98.42   98.35   98.26   98.31   98.21    98.2   99.05   98.06   98.82   98.01
   99.84   98.37   97.67   98.47   97.19   98.04   97.05   98.53   96.63   96.13
   96.86   95.85   96.78   96.93   96.55   95.71   96.82   95.79   96.67     100
  100.92    98.6   98.26   98.93   98.47   99.13   99.92   98.69   97.81   98.85
   98.05   99.02   98.89   97.74   98.59   98.41   96.93   97.58   96.06   97.08
   96.49   97.51   96.61   97.35   99.02   99.99   97.39   96.12   96.04   96.08
   97.94   98.07   97.45   98.22   97.67   98.11   98.96   97.97   98.73   97.93
   99.76   98.29   97.59   98.39   97.11   97.96   96.97   98.45   96.55   96.05
   96.78   95.77    96.7   96.85   96.47   95.63   96.74   95.71   96.59   99.92
Pier Skew, UpSta & Num, DnSta & Num=  ,4982.6, 2 ,4982.6, 2 , 0 , 0 , 0 ,,
     1.2     1.2
   92.84   97.14
     1.2     1.2
   92.76   97.06
Pier Skew, UpSta & Num, DnSta & Num=  ,5012.7, 2 ,5012.7, 2 , 0 , 0 , 0 ,,
     1.2     1.2
   88.14   97.15
     1.2     1.2
   88.06   97.07
Abutment Skew #Up #Dn= , 2 , 2
  4955.5  4991.1
    96.2   88.77
  4955.5  4991.1
   96.12   88.69
Abutment Skew #Up #Dn= , 2 , 2
  5020.4 5029.29
   91.92   96.33
  5020.4 5029.29
   91.84   96.25
BR Coef= 1 , 1 , 0 ,1.25, 0 ,,,.8,-1,2,0,
WSPro=,,,, 1 ,,,, 0 ,,,, 0 ,,,,-1 ,-1 ,-1 , 0 , 0 , 0 , 0 , 0
BR U #Sta/Elev= 163
    1966     101    1976   99.57    1986   98.68    1996   98.34    2006   98.43
    2016   99.01    2226   99.14    2246   98.55    2706   99.21    2726     100
    2856   98.77    3276   98.45    3296   97.89    3356   98.93    3396   98.13
  3699.4   98.97  3755.9   99.13  3849.4   99.12    4000    99.1  4009.4    99.1
  4015.9    99.1  4059.4   99.04  4079.4   99.01  4105.9   98.97  4115.9   98.13
  4124.7   97.82  4134.7   97.87    4154   98.64  4154.7   98.67  4164.7   98.69
  4184.7   98.17  4194.7   98.48    4228   98.49  4261.9   98.05    4278   97.84
    4288   97.39    4308   97.01    4348   97.18    4358   97.66  4362.7    97.6
  4382.7   97.12  4392.7   97.25  4412.7   96.51  4462.7   96.14  4482.7   97.16
  4492.7   96.83  4518.3   96.99  4588.3   97.05  4598.3   96.57  4608.3   97.17
  4638.3   97.59  4668.3   97.42  4688.3   96.69  4695.2    96.8  4699.2   96.87
  4724.3    97.3    4784   97.51  4788.8   97.53  4862.5   97.14  4868.9   97.11
  4918.7   97.43  4929.3    99.1  4945.3  100.07 4945.39  100.04  4945.5     100
 4945.61   99.95  4952.3   97.47 4955.61   96.24  4955.7    96.2  4959.1   94.94
  4976.8   94.82  4982.9   94.03    4991   88.87  4991.1   88.77  4992.6   87.26
  4994.7   85.98  5000.4   85.88  5006.1   86.45  5007.5   87.39  5008.4   88.58
  5012.7   89.23  5017.8    90.6  5020.4   91.92 5029.09   96.33  5029.2   96.38
  5030.1   96.84  5043.8    97.8    5047   98.02 5049.29   98.03  5049.4   98.03
 5049.51   98.03    5089   98.15    5150   98.14  5153.3    98.1  5206.6   97.53
  5264.6   97.93  5264.8   97.93  5308.4    98.3  5358.4   97.75  5364.4   98.06
  5368.4   98.27  5417.6   98.28  5490.6   98.29  5510.6   98.08  5689.3   98.14
  5709.3   98.14  5719.3   98.15  5739.3   98.15  5859.3   98.19  5860.6   98.19
  5869.3   98.37  5879.3   98.59  5889.3    98.8  5900.6   99.04  5929.3   98.09
  5930.6   98.05  5931.7   98.09  5950.6   98.81  6041.7   98.14  6050.1   98.08
  6120.1   98.36  6140.1   98.01  6170.1   99.59  6190.1   99.84    6200   99.47
  6210.1   99.09  6220.1   98.37  6290.1   97.67  6340.1   98.38  6400.1   98.47
  6410.1   98.13  6490.1   98.16  6500.1   97.68  6580.1   97.19  6610.1   98.04
  6680.1   97.82  6760.1   97.05  6810.1   98.53  7030.1   97.04  7040.1   96.63
  7070.1   97.13  7720.1   96.45  7730.1   96.13  7750.1   96.86  7760.1   95.85
  7780.1   96.78  7810.1   96.51  7820.1   96.93  7840.1    96.7  7850.1   96.92
  7920.1   96.41  7960.1   96.83  8080.1   96.27  8100.1   96.71  8440.1   96.55
  8500.1   95.71  8510.1   96.26  8610.1   96.82  8630.1   96.24  8650.1   96.37
  8680.1   95.79  8724.6   96.67  8724.7     100
BR U #Mann= 5
    1966     .99    4000      .1  4982.9     .04  5030.1      .1    6200     .99
BR U Banks=4982.9,5030.1
BR D #Sta/Elev= 163
    1966  100.92    1976   99.49    1986    98.6    1996   98.26    2006   98.35
    2016   98.93    2226   99.06    2246   98.47    2706   99.13    2726   99.92
    2856   98.69    3276   98.37    3296   97.81    3356   98.85    3396   98.05
  3699.4   98.89  3755.9   99.05  3849.4   99.04    4000   99.02  4009.4   99.02
  4015.9   99.02  4059.4   98.96  4079.4   98.93  4105.9   98.89  4115.9   98.05
  4124.7   97.74  4134.7   97.79    4154   98.56  4154.7   98.59  4164.7   98.61
  4184.7   98.09  4194.7    98.4    4228   98.41  4261.9   97.97    4278   97.76
    4288   97.31    4308   96.93    4348    97.1    4358   97.58  4362.7   97.52
  4382.7   97.04  4392.7   97.17  4412.7   96.43  4462.7   96.06  4482.7   97.08
  4492.7   96.75  4518.3   96.91  4588.3   96.97  4598.3   96.49  4608.3   97.09
  4638.3   97.51  4668.3   97.34  4688.3   96.61  4695.2   96.72  4699.2   96.79
  4724.3   97.22    4784   97.43  4788.8   97.45  4862.5   97.06  4868.9   97.03
  4918.7   97.35  4929.3   99.02  4945.3   99.99 4945.39   99.96  4945.5   99.92
 4945.61   99.87  4952.3   97.39 4955.61   96.16  4955.7   96.12  4959.1   94.86
  4976.8   94.74  4982.9   93.95    4991   88.79  4991.1   88.69  4992.6   87.18
  4994.7    85.9  5000.4    85.8  5006.1   86.37  5007.5   87.31  5008.4    88.5
  5012.7   89.15  5017.8   90.52  5020.4   91.84 5029.09   96.25  5029.2    96.3
  5030.1   96.76  5043.8   97.72    5047   97.94 5049.29   97.95  5049.4   97.95
 5049.51   97.95    5089   98.07    5150   98.06  5153.3   98.02  5206.6   97.45
  5264.6   97.85  5264.8   97.85  5308.4   98.22  5358.4   97.67  5364.4   97.98
  5368.4   98.19  5417.6    98.2  5490.6   98.21  5510.6      98  5689.3   98.06
  5709.3   98.06  5719.3   98.07  5739.3   98.07  5859.3   98.11  5860.6   98.11
  5869.3   98.29  5879.3   98.51  5889.3   98.72  5900.6   98.96  5929.3   98.01
  5930.6   97.97  5931.7   98.01  5950.6   98.73  6041.7   98.06  6050.1      98
  6120.1   98.28  6140.1   97.93  6170.1   99.51  6190.1   99.76    6200   99.39
  6210.1   99.01  6220.1   98.29  6290.1   97.59  6340.1    98.3  6400.1   98.39
  6410.1   98.05  6490.1   98.08  6500.1    97.6  6580.1   97.11  6610.1   97.96
  6680.1   97.74  6760.1   96.97  6810.1   98.45  7030.1   96.96  7040.1   96.55
  7070.1   97.05  7720.1   96.37  7730.1   96.05  7750.1   96.78  7760.1   95.77
  7780.1    96.7  7810.1   96.43  7820.1   96.85  7840.1   96.62  7850.1   96.84
  7920.1   96.33  7960.1   96.75  8080.1   96.19  8100.1   96.63  8440.1   96.47
  8500.1   95.63  8510.1   96.18  8610.1   96.74  8630.1   96.16  8650.1   96.29
  8680.1   95.71  8724.6   96.59  8724.7   99.92
BR D #Mann= 5
    1966     .99    4000      .1  4982.9     .04  5030.1      .1    6200     .99
BR D Banks=4982.9,5030.1
BC Design=,, 0 ,, 0 ,,,,,,

Type RM Length L Ch R = 1 ,102115.0,589.5,589.5,589.5
BEGIN DESCRIPTION:
Downstream Section of Bridge/Culvert/Weir
END DESCRIPTION:
XS GIS Cut Line= 6
      3086352.57      13902179.7      3086438.36     13899993.34
      3086521.52     13899723.46      3086689.25     13899514.41
      3086757.31     13899307.79      3086917.51     13895512.85
#Sta/Elev= 30
    1966  100.93    1996   98.27    2726   99.93    3296   97.82    4000   99.03
  4462.7   96.07  4918.7   97.36  4945.3     100  4959.1   94.87  4982.9   93.96
  4994.7   85.91  5000.4   85.81  5006.1   86.38  5017.8   90.53  5030.1   96.77
    5089   98.08  5900.6   98.97  6140.1   97.94    6200    99.4  6290.1    97.6
  6400.1    98.4  6580.1   97.12  6760.1   96.98  6810.1   98.46  7040.1   96.56
  8500.1   95.64  8610.1   96.75  8680.1   95.72  8724.6    96.6  8724.7   99.93
#Mann= 5 , 1 , 0
    1966     .99       0    4000      .1       0  4982.9     .04       0
  5030.1      .1       0    6200     .99       0
#XS Ineff= 2 , 0
       0 4951.41    97.6  6190.1       0   99.77
Permanent Ineff=
       F       F
Bank Sta=4982.9,5030.1
XS Rating Curve= 0
Exp/Cntr=.5,.3

Type RM Length L Ch R = 1 ,101525.5,981.6,980.9,965.7
BEGIN DESCRIPTION:
Cross Section 101525.5
END DESCRIPTION:
XS GIS Cut Line= 5
      3087281.37     13901898.66       3087356.2     13899460.78
       3087356.2     13899070.55      3087374.35     13898380.84
      3087382.36     13895890.06
#Sta/Elev= 30
  2358.5   100.9  2368.5    99.3  2658.5    98.4  4198.5      96  4218.5    97.1
  4937.5    98.4    4975   94.19  4994.2   86.38  5006.1   86.44  5008.8   88.95
  5025.5   92.04  5028.7    94.3    5037   99.65  5058.2   101.8  5084.7   99.82
  5147.5    97.3  5267.8    96.3  5377.8    97.8  5494.2   96.54  5537.8    94.5
  5717.8    99.1    6200   98.55  6547.7    96.5  7277.7    97.6  7317.7    96.2
  7507.7    97.2  7647.7    95.8  8297.7    95.8  8367.7    96.9  8368.5   100.5
#Mann= 6 , 1 , 0
  2358.5      .1       0    4975     .04       0  5028.7      .1       0
  5084.7     .14       0  5494.2      .1       0    6200     .99       0
#XS Ineff= 2 , 0
       0  4937.5    98.4    5192       0      97
Permanent Ineff=
       F       F
Bank Sta=4975,5028.7
XS Rating Curve= 0
Exp/Cntr=.3,.1

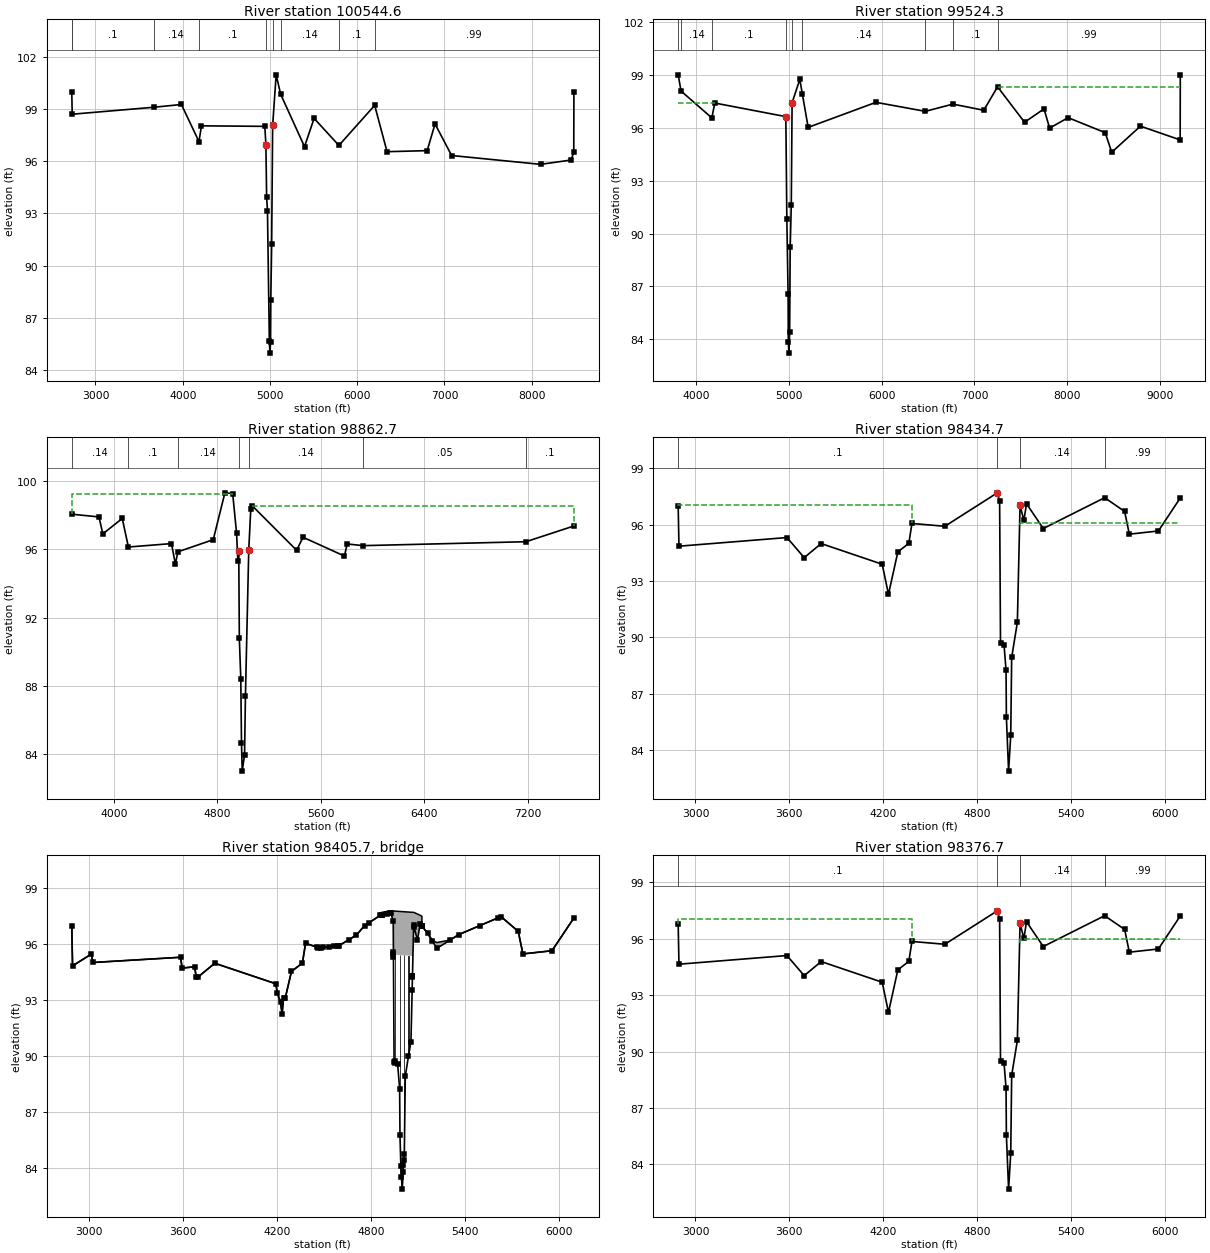
Type RM Length L Ch R = 1 ,100544.6,1031,1020.3,909.7
BEGIN DESCRIPTION:
Cross Section 100544.6
END DESCRIPTION:
XS GIS Cut Line= 6
      3087845.69      13901476.6      3088318.17     13900313.85
      3088336.32     13899143.15      3088248.37     13898532.63
      3087959.14     13898245.06       3087574.2     13895975.93
#Sta/Elev= 30
  2728.4     100  2733.4   98.72  3666.2   99.12  3984.9   99.28  4186.2   97.14
  4214.9   98.05  4940.9   98.02  4953.3   96.95  4961.6   93.93  4971.3   93.17
  4992.8   85.63    5000   84.95  5006.7    85.6  5009.5   88.04  5019.3   91.24
  5030.6   98.07  5070.9  100.99  5122.6   99.87  5395.8   96.85  5505.8   98.48
  5789.9   96.92    6200   99.23  6341.8   96.56  6801.8   96.62  6891.8   98.16
  7081.8   96.34  8101.8   95.83  8451.8   96.08  8481.8   96.53  8483.4     100
#Mann= 9 , 1 , 0
  2728.4      .2       0  2733.4      .1       0  3666.2     .14       0
  4186.2      .1       0  4953.3     .04       0  5030.6      .1       0
  5122.6     .14       0  5789.9      .1       0    6200     .99       0
Bank Sta=4953.3,5030.6
XS Rating Curve= 0
Exp/Cntr=.3,.1

Type RM Length L Ch R = 1 ,99524.3 ,885.7,661.6,522.6
BEGIN DESCRIPTION:
Cross Section 99524.3
END DESCRIPTION:
XS GIS Cut Line= 6
      3089544.62      13900507.3      3089346.28     13899261.28
      3089239.41     13899070.77      3088976.45     13898473.45
      3088551.51     13898187.01      3087646.81     13895569.25
#Sta/Elev= 30
  3805.1      99  3836.1   98.08  4167.8   96.56  4200.1    97.4    4966   96.63
  4976.9   90.85  4990.3   86.57    4993   83.83    5000   83.22  5007.1   84.43
  5013.2   89.25  5024.8    91.6  5033.6   97.42  5116.9   98.74  5143.6   97.93
  5206.9   96.02  5937.9   97.44  6470.5   96.93  6767.9   97.34  7100.4   96.99
  7249.6   98.32  7540.4   96.31  7750.4   97.07  7810.4   95.98  8010.4   96.57
  8410.4   95.72  8480.4   94.61  8790.4   96.09  9218.5   95.31  9220.1      99
#Mann= 9 , 1 , 0
  3805.1      .2       0  3836.1     .14       0  4167.8      .1       0
    4966     .04       0  5033.6      .1       0  5143.6     .14       0
  6470.5     .05       0  6767.9      .1       0  7249.6     .99       0
#XS Ineff= 2 , 0
       0    4200    97.4  7250.4       0   98.33
Permanent Ineff=
       F       F
Bank Sta=4966,5033.6
XS Rating Curve= 0
Exp/Cntr=.3,.1

Type RM Length L Ch R = 1 ,98862.7 ,881.1,428,309.2
BEGIN DESCRIPTION:
Cross Section 98862.7-Interpolated
END DESCRIPTION:
XS GIS Cut Line= 6
      3090554.92     13900068.03      3090161.42     13899284.99
      3090074.71      13899086.8      3089740.26     13898826.67
      3088935.11     13898318.81      3088378.18     13897023.48
#Sta/Elev= 30
  3675.7   98.05  3885.7   97.89  3915.7    96.9  4065.7    97.8  4113.1   96.13
  4445.7   96.33  4475.7   95.14  4495.7   95.85  4768.4   96.56  4858.4    99.3
  4918.4   99.26  4948.4   96.96  4958.4   95.34 4965.33    95.9 4969.83   90.81
 4981.23   88.39 4986.53   84.69 4992.03   83.02 5010.13   83.97 5017.03   87.43
 5042.63   95.96  5058.4   98.37  5068.4   98.55  5412.1   95.94  5462.1    96.7
  5782.1    95.6  5802.1   96.31  5925.6   96.21  7183.5   96.44    7554   97.36
#Mann= 7 , 1 , 0
  3675.7     .14       0  4113.1      .1       0  4495.7     .14       0
 4965.33     .04       0 5042.63     .14       0  5925.6     .05       0
  7183.5      .1       0
#XS Ineff= 2 , 0
       0  4918.4   99.26  5068.4       0   98.55
Permanent Ineff=
       F       F
Bank Sta=4965.33,5042.63
XS Rating Curve= 0
Exp/Cntr=.5,.3

Type RM Length L Ch R = 1 ,98434.7 ,58,58,58
BEGIN DESCRIPTION:
Upstream Section of Bridge/Culvert/Weir
END DESCRIPTION:
XS GIS Cut Line= 6
      3091665.05     13900038.66      3090999.32     13898904.88
      3090690.08     13898826.22      3089869.68     13898581.22
      3089586.62     13898459.13      3089393.73      13898098.1
#Sta/Elev= 30
  2889.5      97  2894.5   94.85  3584.5   95.31  3694.5   94.24  3802.9   94.99
  4192.9   93.89  4232.9   92.29  4292.9   94.55  4362.9      95  4382.9   96.06
  4593.2   95.91 4928.23   97.69 4943.01   97.23 4948.58   89.69 4971.03   89.61
 4983.99   88.25 4986.08   85.76 5000.26   82.88 5013.92   84.78 5019.92   88.93
  5056.2   90.79 5073.43   97.02 5097.79   96.22 5114.84   97.11 5221.68   95.79
  5613.8   97.43  5741.5    96.7  5771.5   95.49  5957.2   95.66  6097.2   97.42
#Mann= 4 , 1 , 0
  2889.5      .1       0 4928.23    .035       0 5073.43     .14       0
  5613.8     .99       0
#XS Ineff= 2 , 0
       0  4382.9   97.06  5070.6       0    96.1
Permanent Ineff=
       F       F
Bank Sta=4928.23,5073.43
XS Rating Curve= 0
Exp/Cntr=.5,.3

Type RM Length L Ch R = 3 ,98405.7 ,,,
BEGIN DESCRIPTION:
ACCESS ROAD, SKEW ANGLE OF 30 DEGREES
Structure ID: P18-48
END DESCRIPTION:
Bridge Culvert--1,0,-1,-1, 0
Deck Dist Width WeirC Skew NumUp NumDn MinLoCord MaxHiCord MaxSubmerge Is_Ogee
10,38,2.6,0, 45, 45, , , .95, 0, 1,1,,
  2889.5  2894.5  3014.5  3024.5  3584.5  3594.5  3674.5  3684.5  3694.5  3802.9
  4192.9  4202.9  4222.9  4232.9  4242.9  4252.9  4292.9  4362.9  4382.9  4463.2
  4593.2 4707.07 4759.79 4869.69  4869.8 4928.23 4943.01 4944.32 4944.41 5065.84
 5065.95 5073.43 5097.79 5114.84  5126.3 5126.41  5193.7 5221.68  5304.5  5361.5
  5631.5  5741.5  5771.5  5957.2  6097.2
      97   94.85   95.48   95.03   95.31   94.73    94.8   94.25   94.24   94.99
   93.89   93.38   92.91   92.29   93.15   93.11   94.55      95   96.06   95.83
   95.92    96.5   97.01    97.6   97.72    97.8    97.8   97.79   97.79   97.72
   97.72   97.72   97.63   97.56   97.51      97   96.22    96.1   96.23   96.53
   97.49    96.7   95.49   95.66   97.42
      97   94.85   95.48   95.03   95.31   94.73    94.8   94.25   94.24   94.99
   93.89   93.38   92.91   92.29   93.15   93.11   94.55      95   96.06   95.82
   95.91   96.49      97   97.59   97.59   97.69   97.23   95.46   95.45   95.38
   94.32   97.02   96.22   97.11   96.99   96.99   96.17   95.79   96.22   96.52
   97.49    96.7   95.49   95.66   97.42
  2889.5  2894.5  3014.5  3024.5  3584.5  3594.5  3674.5  3684.5  3694.5  3802.9
  4192.9  4202.9  4222.9  4232.9  4242.9  4252.9  4292.9  4362.9  4382.9  4463.2
  4593.2 4707.07 4759.79 4869.69  4869.8 4928.23 4943.01 4944.32 4944.41 5065.84
 5065.95 5073.43 5097.79 5114.84  5126.3 5126.41  5193.7 5221.68  5304.5  5361.5
  5631.5  5741.5  5771.5  5957.2  6097.2
      97   94.85   95.48   95.03   95.31   94.73    94.8   94.25   94.24   94.99
   93.89   93.38   92.91   92.29   93.15   93.11   94.55      95   96.06   95.83
   95.92    96.5   97.01    97.6   97.72    97.8    97.8   97.79   97.79   97.72
   97.72   97.72   97.63   97.56   97.51      97   96.22    96.1   96.23   96.53
   97.49    96.7   95.49   95.66   97.42
   96.82   94.67    95.3   94.85   95.13   94.55   94.62   94.07   94.06   94.81
   93.71    93.2   92.73   92.11   92.97   92.93   94.37   94.82   95.88   95.64
   95.73   96.31   96.82   97.41   97.41   97.51   97.05   95.28   95.27    95.2
   94.14   96.84   96.04   96.93   96.81   96.81   95.99   95.61   96.04   96.34
   97.31   96.52   95.31   95.48   97.24
Pier Skew, UpSta & Num, DnSta & Num=  ,4956.2, 2 ,4956.2, 2 , 0 , 0 , 0 ,,
     1.3     1.3
   88.66   96.45
     1.3     1.3
   88.48   96.27
Pier Skew, UpSta & Num, DnSta & Num=  ,4984, 2 ,4984, 2 , 0 , 0 , 0 ,,
     1.3     1.3
   86.47   96.43
     1.3     1.3
   86.29   96.25
Pier Skew, UpSta & Num, DnSta & Num=  ,5012.2, 2 ,5012.2, 2 , 0 , 0 , 0 ,,
     1.3     1.3
   83.41   96.41
     1.3     1.3
   83.23   96.23
Pier Skew, UpSta & Num, DnSta & Num=  ,5040.5, 2 ,5040.5, 2 , 0 , 0 , 0 ,,
     1.3     1.3
   88.99   96.39
     1.3     1.3
   88.81   96.21
BR Coef= 1 , 1 , 0 ,1.25, 0 ,,,.8,0,2,0,
WSPro=,,,, 1 ,,,, 0 ,,,, 0 ,,,,-1 ,-1 ,-1 , 0 , 0 , 0 , 0 , 0
BR U #Sta/Elev= 81
  2889.5      97  2894.5   94.85  3014.5   95.48  3024.5   95.03  3584.5   95.31
  3594.5   94.73  3674.5    94.8  3684.5   94.25  3694.5   94.24  3802.9   94.99
  4192.9   93.89  4202.9   93.38  4222.9   92.91  4232.9   92.29  4242.9   93.15
  4252.9   93.11  4292.9   94.55  4362.9      95  4382.9   96.06  4454.5   95.85
  4463.2   95.82  4484.5   95.83  4494.5   95.84  4534.5   95.87  4564.5   95.89
  4593.2   95.91  4594.5   95.92    4662   96.26 4707.07   96.49 4759.79      97
  4786.9   97.15  4860.8   97.57 4869.69   97.59  4869.8   97.59 4869.91   97.59
  4904.5   97.65  4919.6   97.67 4928.23   97.69 4943.01   97.23 4944.23   95.58
 4944.32   95.46 4944.41   95.33 4948.58   89.69 4953.89   89.76 4956.15   89.66
 4971.03   89.61 4983.99   88.25 4986.08   85.76 4991.91    84.1 4995.56   83.51
 5000.26   82.88 5006.87    83.8    5008   84.18 5012.18   84.45 5013.92   84.78
 5019.92   88.93 5040.54   90.02  5056.2   90.79  5063.9   93.57 5065.76   94.25
 5065.84   94.28 5065.95   94.32 5073.43   97.02  5075.8   96.94 5097.79   96.22
 5114.84   97.11 5126.19   96.99  5126.3   96.99 5126.41   96.99 5163.13   96.59
  5193.7   96.17 5221.68   95.79  5304.5   96.22  5361.5   96.52  5496.9   97.01
  5613.8   97.43  5631.5   97.49  5741.5    96.7  5771.5   95.49  5957.2   95.66
  6097.2   97.42
BR U #Mann= 4
  2889.5      .1 4928.23    .035 5073.43     .14  5613.8     .99
BR U Banks=4928.23,5073.43
BR D #Sta/Elev= 81
  2889.5   96.82  2894.5   94.67  3014.5    95.3  3024.5   94.85  3584.5   95.13
  3594.5   94.55  3674.5   94.62  3684.5   94.07  3694.5   94.06  3802.9   94.81
  4192.9   93.71  4202.9    93.2  4222.9   92.73  4232.9   92.11  4242.9   92.97
  4252.9   92.93  4292.9   94.37  4362.9   94.82  4382.9   95.88  4454.5   95.67
  4463.2   95.64  4484.5   95.65  4494.5   95.66  4534.5   95.69  4564.5   95.71
  4593.2   95.73  4594.5   95.74    4662   96.08 4707.07   96.31 4759.79   96.82
  4786.9   96.97  4860.8   97.39 4869.69   97.41  4869.8   97.41 4869.91   97.41
  4904.5   97.47  4919.6   97.49 4928.23   97.51 4943.01   97.05 4944.23    95.4
 4944.32   95.28 4944.41   95.15 4948.58   89.51 4953.89   89.58 4956.15   89.48
 4971.03   89.43 4983.99   88.07 4986.08   85.58 4991.91   83.92 4995.56   83.33
 5000.26    82.7 5006.87   83.62    5008      84 5012.18   84.27 5013.92    84.6
 5019.92   88.75 5040.54   89.84  5056.2   90.61  5063.9   93.39 5065.76   94.07
 5065.84    94.1 5065.95   94.14 5073.43   96.84  5075.8   96.76 5097.79   96.04
 5114.84   96.93 5126.19   96.81  5126.3   96.81 5126.41   96.81 5163.13   96.41
  5193.7   95.99 5221.68   95.61  5304.5   96.04  5361.5   96.34  5496.9   96.83
  5613.8   97.25  5631.5   97.31  5741.5   96.52  5771.5   95.31  5957.2   95.48
  6097.2   97.24
BR D #Mann= 4
  2889.5      .1 4928.23    .035 5073.43     .14  5613.8     .99
BR D Banks=4928.23,5073.43
BC Design=,, 0 ,, 0 ,,,,,,

Type RM Length L Ch R = 1 ,98376.7 ,759.1,759.1,759.1
BEGIN DESCRIPTION:
Downstream Section of Bridge/Culvert/Weir
END DESCRIPTION:
XS GIS Cut Line= 6
      3091711.41     13900003.81      3091045.68     13898870.02
      3090736.44     13898791.36      3089916.04     13898546.36
      3089632.98     13898424.27       3089440.1     13898063.25
#Sta/Elev= 30
  2889.5    96.8  2894.5   94.65  3584.5   95.11  3694.5   94.04  3802.9   94.79
  4192.9   93.69  4232.9   92.09  4292.9   94.35  4362.9    94.8  4382.9   95.86
  4593.2   95.71 4928.23   97.49 4943.01   97.03 4948.58   89.49 4971.03   89.41
 4983.99   88.05 4986.08   85.56 5000.26   82.68 5013.92   84.58 5019.92   88.73
  5056.2   90.59 5073.43   96.82 5097.79   96.02 5114.84   96.91 5221.68   95.59
  5613.8   97.23  5741.5    96.5  5771.5   95.29  5957.2   95.46  6097.2   97.22
#Mann= 4 , 1 , 0
  2889.5      .1       0 4928.23    .035       0 5073.43     .14       0
  5613.8     .99       0
#XS Ineff= 2 , 0
       0  4382.9   97.06  5070.6       0      96
Permanent Ineff=
       F       F
Bank Sta=4928.23,5073.43
XS Rating Curve= 0
Exp/Cntr=.5,.3

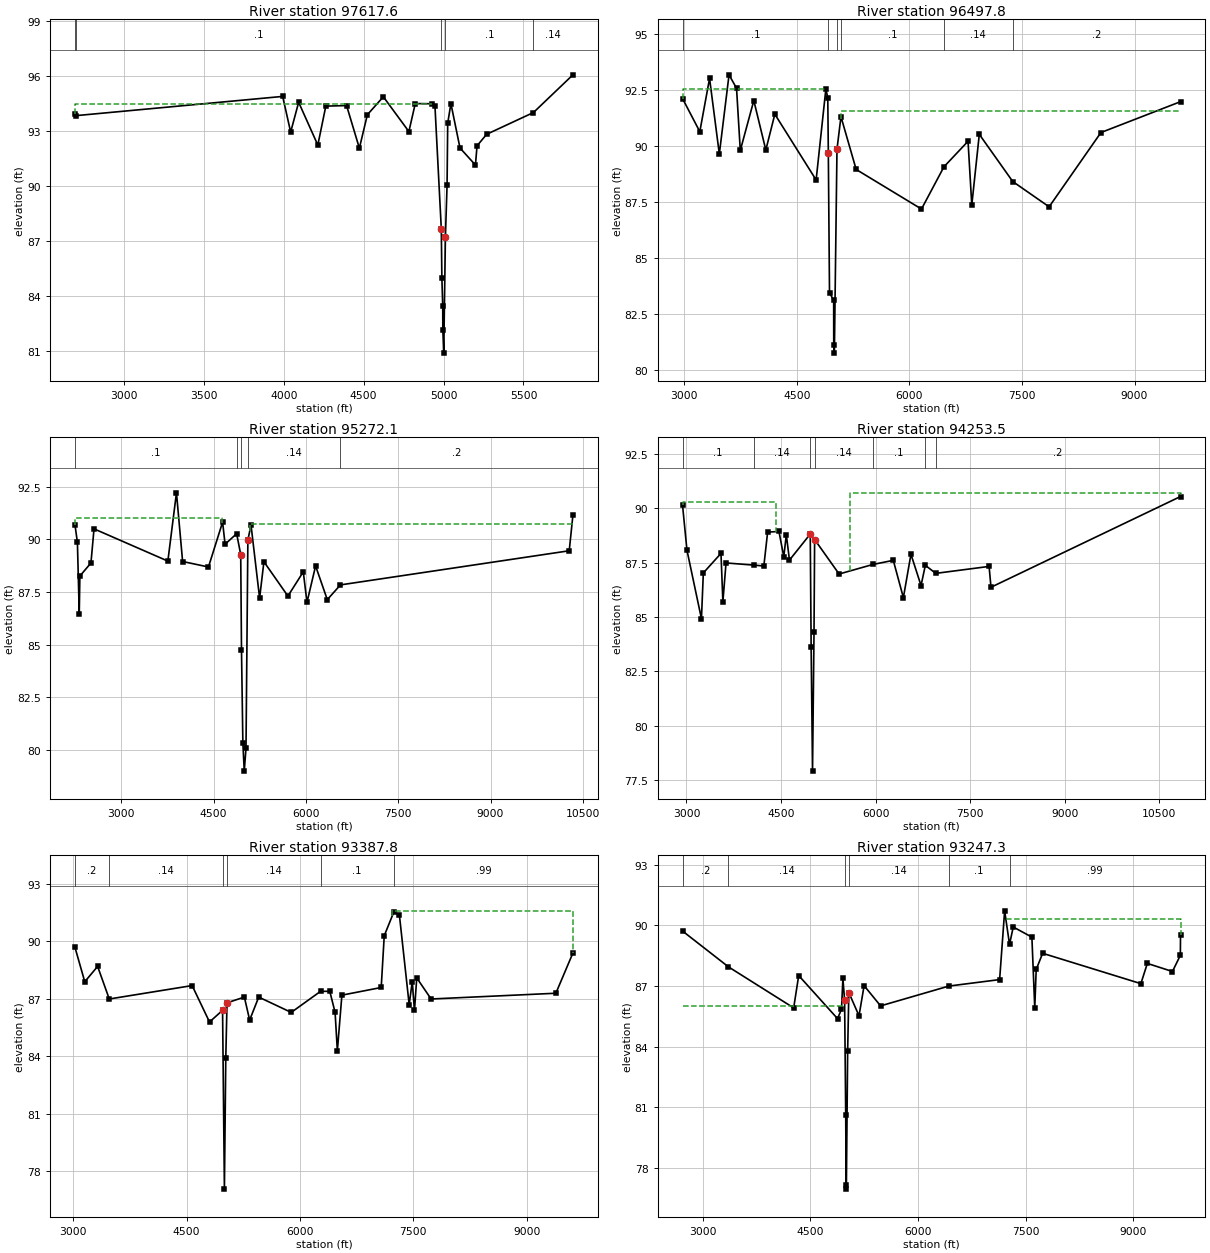
Type RM Length L Ch R = 1 ,97617.6 ,1197.1,1119.8,976.3
BEGIN DESCRIPTION:
Cross Section 97617.6
END DESCRIPTION:
XS GIS Cut Line= 4
      3092043.18      13900202.9      3091044.79     13898401.25
      3090790.34      13898071.4      3090331.16     13897625.55
#Sta/Elev= 30
  2693.1   93.95  2700.1   93.84  3993.1   94.89  4043.1   92.94  4093.1   94.57
  4213.1   92.23  4263.1   94.36  4393.1   94.39  4473.1   92.06  4523.1   93.89
  4623.1   94.87  4782.9   92.97  4822.9    94.5  4928.1   94.49    4946   94.38
  4985.8   87.66  4989.4   84.97  4994.8   83.42  4995.4   82.15  5001.1   80.86
  5011.6   87.23  5021.9   90.05  5025.9   93.42  5045.9    94.5  5102.9   92.07
  5199.5   91.14  5209.5   92.19  5269.5   92.82  5562.5   94.01  5809.5   96.07
#Mann= 5 , 1 , 0
  2693.1     .14       0  2700.1      .1       0  4985.8    .045       0
  5011.6      .1       0  5562.5     .14       0
#XS Ineff= 2 , 0
       0  4928.1   94.49  5045.9       0    94.5
Permanent Ineff=
       F       F
Bank Sta=4985.8,5011.6
XS Rating Curve= 0
Exp/Cntr=.3,.1

Type RM Length L Ch R = 1 ,96497.8 ,1220.4,1225.7,1411
BEGIN DESCRIPTION:
Cross Section 96497.8
END DESCRIPTION:
XS GIS Cut Line= 5
      3092706.76     13899357.06      3092486.68     13898778.21
      3091902.39     13897675.59      3091666.78     13897383.44
      3088253.33     13894623.02
#Sta/Elev= 30
  2979.7   92.13  3209.7   90.65  3339.7   93.03  3469.7   89.65  3598.9   93.19
  3698.9   92.59  3748.9   89.81  3928.9   92.04  4088.9   89.83  4208.9   91.43
  4758.9   88.49  4888.7   92.56  4914.1   92.16  4921.4    89.7  4937.1   83.45
  4992.6   83.11  4993.5    81.1  5001.8   80.75  5036.7   89.86  5089.7   91.32
  5292.1   88.96  6162.1   87.19  6461.7   89.08  6782.1   90.22  6832.1   87.37
  6932.1   90.53  7377.8   88.42  7862.1   87.29  8552.1   90.61  9612.1   91.99
#Mann= 6 , 1 , 0
  2979.7      .1       0  4921.4     .04       0  5036.7     .14       0
  5089.7      .1       0  6461.7     .14       0  7377.8      .2       0
#XS Ineff= 2 , 0
       0  4888.7   92.56  5096.8       0   91.58
Permanent Ineff=
       F       F
Bank Sta=4921.4,5036.7
XS Rating Curve= 0
Exp/Cntr=.3,.1

Type RM Length L Ch R = 1 ,95272.1 ,1258.6,1018.6,763.9
BEGIN DESCRIPTION:
Cross Section 95272.1
END DESCRIPTION:
XS GIS Cut Line= 6
      3093999.35     13899276.58      3093306.58     13897779.26
      3092939.04     13896978.21      3092562.07     13896591.82
      3091393.49     13895555.17       3088328.4     13893949.94
#Sta/Elev= 30
  2245.4    90.7  2285.5   89.86  2315.5   86.48  2325.5   88.26  2505.5   88.88
  2555.5    90.5  3755.5   88.97  3895.3   92.21  3995.3   88.95  4415.3   88.69
  4645.3   90.82  4685.3   89.77  4873.6   90.27  4939.6   89.28  4952.3   84.75
  4974.5   80.35  4997.1      79  5025.5   80.09  5055.9   89.96  5106.7   90.69
  5246.7   87.21  5316.5   88.94  5706.5   87.31  5956.5   88.46  6016.5   87.01
  6156.5   88.74  6346.5   87.14  6560.7   87.84 10278.6   89.46 10338.6   91.15
#Mann= 5 , 1 , 0
  2245.4      .1       0  4873.6     .14       0  4939.6     .04       0
  5055.9     .14       0  6560.7      .2       0
#XS Ineff= 2 , 0
       0    4640      91  5086.7       0   90.72
Permanent Ineff=
       F       F
Bank Sta=4939.6,5055.9
XS Rating Curve= 0
Exp/Cntr=.3,.1

Type RM Length L Ch R = 1 ,94253.5 ,700.3,865.7,1073.4
BEGIN DESCRIPTION:
Cross Section 94253.5
END DESCRIPTION:
XS GIS Cut Line= 5
      3094837.35     13897747.74      3093919.15     13896478.73
      3093419.67      13896035.8      3090292.73     13894158.82
      3088483.81     13893259.74
#Sta/Elev= 30
  2937.6   90.15  3007.6   88.08  3237.6   84.92  3267.6   87.03  3547.6   87.93
  3577.6    85.7  3627.6   87.49  4067.2   87.39  4227.6   87.35  4287.6   88.91
  4467.6   88.94    4544   87.77    4584   88.79    4634   87.62  4963.7   88.82
  4978.1    83.6    5000    77.9  5023.6   84.29  5033.2   88.57  5421.5   86.98
  5957.9   87.42  6281.5   87.61  6441.5   85.89  6561.5   87.89  6721.5   86.45
  6789.9   87.38  6955.3   87.01  7801.5   87.33  7831.5   86.37 10838.6   90.55
#Mann= 7 , 1 , 0
  2937.6      .1       0  4067.2     .14       0  4963.7    .035       0
  5033.2     .14       0  5957.9      .1       0  6789.9     .14       0
  6955.3      .2       0
#XS Ineff= 2 , 0
       0  4415.5    90.3  5596.7       0   90.72
Permanent Ineff=
       F       F
Bank Sta=4963.7,5033.2
XS Rating Curve= 0
Exp/Cntr=.3,.1

Type RM Length L Ch R = 1 ,93387.8 ,132.1,140.5,141.9
BEGIN DESCRIPTION:
Cross Section 93387.8-Interpolated
END DESCRIPTION:
XS GIS Cut Line= 4
      3095169.68      13897301.2      3094311.05     13895705.16
      3094112.86     13895482.19      3090420.45     13892953.19
#Sta/Elev= 30
  3023.7    89.7  3153.7    87.9  3323.7    88.7  3477.7      87  4573.7    87.7
  4803.7    85.8  4976.2   86.41  5000.5   77.08  5018.7   83.91  5035.1    86.8
  5264.4    87.1  5334.4    85.9  5454.4    87.1  5884.4    86.3  6272.2    87.4
  6394.4    87.4  6464.4    86.3  6494.4    84.3  6554.4    87.2  7074.4    87.6
  7114.4    90.3  7240.5   91.53  7314.4    91.4  7444.4    86.7  7484.4    87.9
  7514.4    86.4  7544.4    88.1  7734.4      87  9384.4    87.3  9609.9    89.4
#Mann= 6 , 1 , 0
  3023.7      .2       0  3477.7     .14       0  4976.2    .035       0
  5035.1     .14       0  6272.2      .1       0  7240.5     .99       0
#XS Ineff= 2 , 0
       0                    7220       0    91.6
Permanent Ineff=
       F       F
Bank Sta=4976.2,5035.1
XS Rating Curve= 0
Exp/Cntr=.5,.3

Type RM Length L Ch R = 1 ,93247.3 ,33.4,33.4,33.4
BEGIN DESCRIPTION:
Upstream Section of Bridge/Culvert/Weir
END DESCRIPTION:
XS GIS Cut Line= 6
      3095450.55     13897467.37      3094381.37     13895599.55
      3094318.66      13895501.3       3094290.2     13895465.25
      3094184.39     13895335.01      3090507.95      13892805.6
#Sta/Elev= 30
  2715.9   89.71  3356.1   87.94  4265.9   85.91  4335.9   87.51  4877.6   85.38
  4932.8   85.84  4952.4   87.37  4976.2   86.28  4991.6   80.62  4997.6   77.16
  5000.5   76.95  5018.7   83.78  5035.1   86.67  5177.1   85.52  5248.1   87.01
  5478.1   86.01  6430.4   86.99  7138.1   87.31  7208.1   90.71  7276.2   89.05
  7328.1   89.91  7588.1   89.41  7628.1   85.91  7648.1   87.81  7738.1   88.61
  9108.1   87.11  9198.1   88.11  9548.1   87.71  9658.6   88.51  9660.9   89.51
#Mann= 6 , 1 , 0
  2715.9      .2       0  3356.1     .14       0  4976.2    .035       0
  5035.1     .14       0  6430.4      .1       0  7276.2     .99       0
#XS Ineff= 2 , 0
       0    4977      86    7225       0    90.3
Permanent Ineff=
       F       F
Bank Sta=4976.2,5035.1
XS Rating Curve= 0
Exp/Cntr=.5,.3