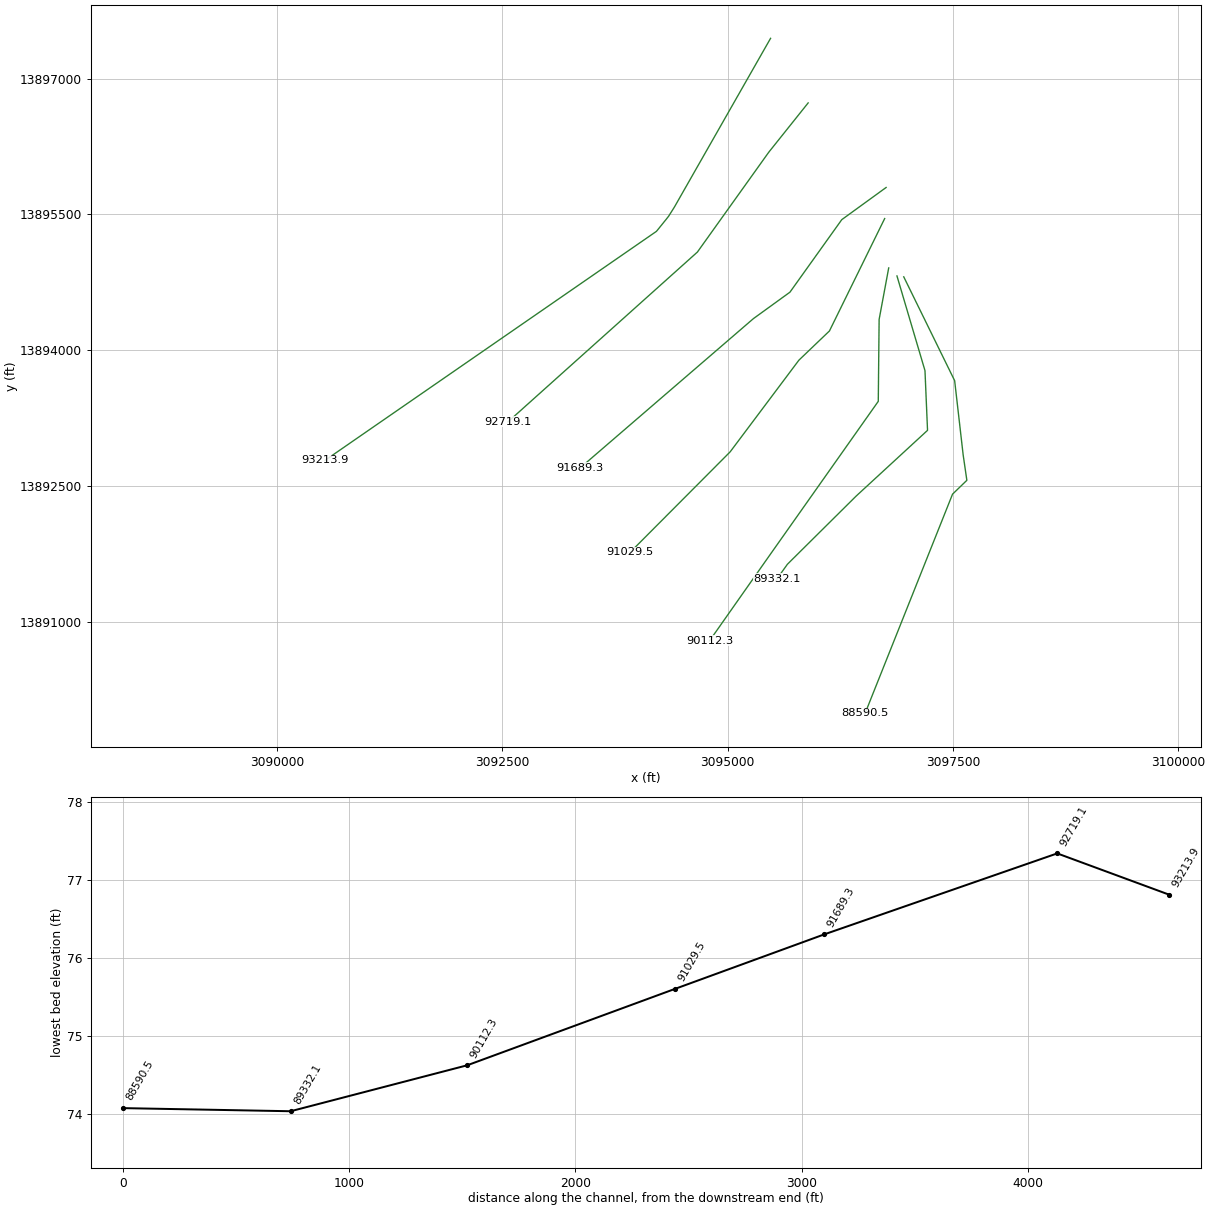
HEC-RAS study P118-00-00.PRJ: P118-00-00

--- P118-00-00.g01 (geometry) --- (continued)

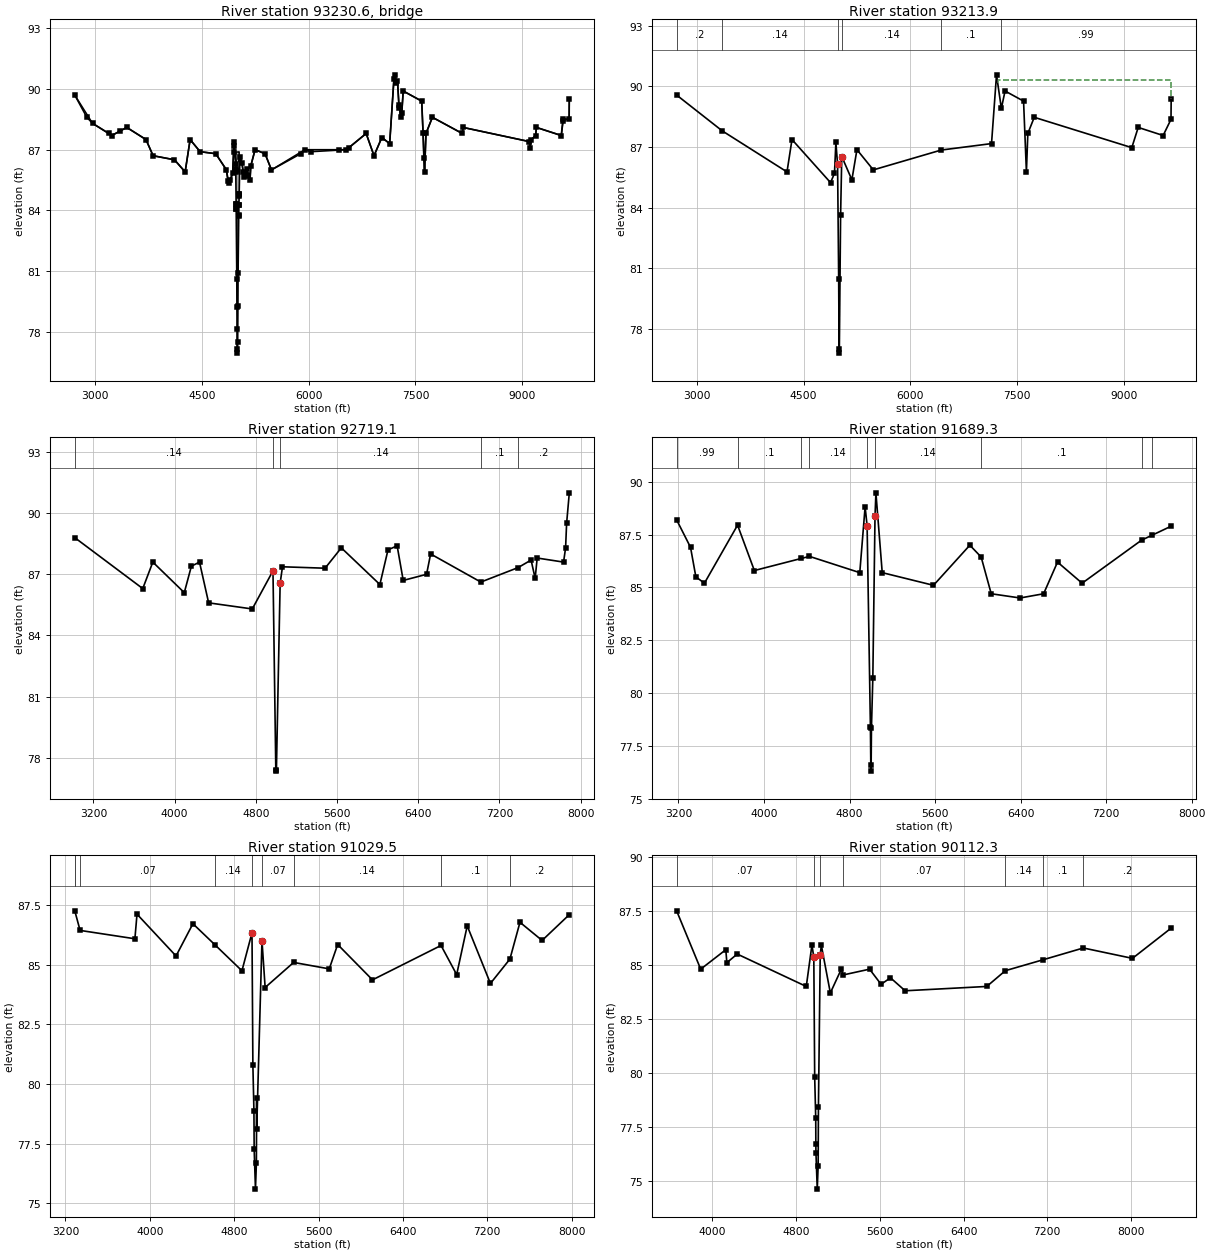
Type RM Length L Ch R = 3 ,93230.6 ,,,
BEGIN DESCRIPTION:
FOOTBRIDGE
Structure ID: P18-47
END DESCRIPTION:
Bridge Culvert--1,0,-1,-1, 0
Deck Dist Width WeirC Skew NumUp NumDn MinLoCord MaxHiCord MaxSubmerge Is_Ogee
10,13.4,2.6,0, 60, 60, , , .95, 0, 1,1,,
  2715.9  2965.9  3235.9  3445.9  3715.9  3815.9  4115.9  4265.9  4335.9  4475.9
  4695.9  4845.9  4877.6  4932.8  4952.4  4976.2 4976.89    4977  4982.6  5021.6
  5024.5 5024.61  5035.1  5063.1  5090.4  5130.3  5177.1  5188.1  5248.1  5388.1
  5478.1  5948.1  6528.1  6808.1  6918.1  7028.1  7138.1  7198.1  7208.1  7228.1
  7248.1  7268.1  7298.1  7308.1  7328.1  7588.1  7628.1  7648.1  7738.1  8158.1
  8168.1  9098.1  9108.1  9128.1  9188.1  9198.1  9548.1  9578.1  9658.6  9660.9
    89.7    88.3    87.7    88.1    87.5    86.7    86.5    85.9    87.5    86.9
    86.8      86   85.37   85.83   87.37   86.38   86.38   86.88   86.88   86.89
   86.89   86.39   86.67   86.36   85.73   86.07   85.51    86.2      87    86.8
      86      87      87    87.8    86.7    87.6    87.3    90.5    90.7    90.3
    90.4    89.2    88.6    88.8    89.9    89.4    85.9    87.8    88.6    87.8
    88.1    87.4    87.1    87.5    87.7    88.1    87.7    88.5    88.5    89.5
    89.7    88.3    87.7    88.1    87.5    86.7    86.5    85.9    87.5    86.9
    86.8      86   85.37   85.83   87.36   86.27   86.03      86   84.28   84.28
   84.79   84.81   86.66   86.35   85.63   86.06   85.51    86.2      87    86.8
      86      87      87    87.8    86.7    87.6    87.3    90.5    90.7    90.3
    90.4    89.2    88.6    88.8    89.9    89.4    85.9    87.8    88.6    87.8
    88.1    87.4    87.1    87.5    87.7    88.1    87.7    88.5    88.5    89.5
  2715.9  2965.9  3235.9  3445.9  3715.9  3815.9  4115.9  4265.9  4335.9  4475.9
  4695.9  4845.9  4877.6  4932.8  4952.4  4976.2 4976.89    4977  4982.6  5021.6
  5024.5 5024.61  5035.1  5063.1  5090.4  5130.3  5177.1  5188.1  5248.1  5388.1
  5478.1  5948.1  6528.1  6808.1  6918.1  7028.1  7138.1  7198.1  7208.1  7228.1
  7248.1  7268.1  7298.1  7308.1  7328.1  7588.1  7628.1  7648.1  7738.1  8158.1
  8168.1  9098.1  9108.1  9128.1  9188.1  9198.1  9548.1  9578.1  9658.6  9660.9
    89.7    88.3    87.7    88.1    87.5    86.7    86.5    85.9    87.5    86.9
    86.8      86   85.37   85.83   87.37   86.38   86.38   86.88   86.88   86.89
   86.89   86.39   86.67   86.36   85.73   86.07   85.51    86.2      87    86.8
      86      87      87    87.8    86.7    87.6    87.3    90.5    90.7    90.3
    90.4    89.2    88.6    88.8    89.9    89.4    85.9    87.8    88.6    87.8
    88.1    87.4    87.1    87.5    87.7    88.1    87.7    88.5    88.5    89.5
   89.56   88.16   87.56   87.96   87.36   86.56   86.36   85.76   87.36   86.76
   86.66   85.86   85.23   85.69   87.22   86.13   85.89   85.86   84.14   84.14
   84.65   84.67   86.52   86.21   85.49   85.92   85.37   86.06   86.86   86.66
   85.86   86.86   86.86   87.66   86.56   87.46   87.16   90.36   90.56   90.16
   90.26   89.06   88.46   88.66   89.76   89.26   85.76   87.66   88.46   87.66
   87.96   87.26   86.96   87.36   87.56   87.96   87.56   88.36   88.36   89.36
Pier Skew, UpSta & Num, DnSta & Num=  ,4995, 2 ,4995, 2 , 0 , 0 , 0 ,,
       1       1
   76.97   85.28
       1       1
   76.83   85.14
Pier Skew, UpSta & Num, DnSta & Num=  ,5008.9, 2 ,5008.9, 2 , 0 , 0 , 0 ,,
       1       1
   79.37   85.29
       1       1
   79.23   85.15
Abutment Skew #Up #Dn= , 2 , 2
  5018.6 5021.69
   83.74   84.29
  5018.6 5021.69
    83.6   84.15
BR Coef= 1 , 1 , 0 ,1.25, 0 ,,,.8,0,2,0,
WSPro=,,,, 1 ,,,, 0 ,,,, 0 ,,,,-1 ,-1 ,-1 , 0 , 0 , 0 , 0 , 0
BR U #Sta/Elev= 97
  2715.9    89.7  2885.9    88.6  2965.9    88.3  3195.9    87.8  3235.9    87.7
  3356.1   87.93  3445.9    88.1  3715.9    87.5  3815.9    86.7  4115.9    86.5
  4265.9    85.9  4335.9    87.5  4475.9    86.9  4695.9    86.8  4845.9      86
  4864.3   85.47  4877.6   85.37  4901.6   85.48  4932.8   85.83    4946   86.86
  4952.4   87.36  4955.8    87.2  4976.2   86.27 4976.89   86.03    4977      86
 4977.11   85.96  4977.3   85.89 4981.91   84.32    4982   84.29  4982.6   84.08
  4982.7   84.05  4991.6   80.61    4993   79.21  4995.1   78.13  4997.6   77.15
  5000.5   76.94  5003.6    77.5  5007.1   79.27    5009   80.88  5018.6   83.74
  5018.7   83.77 5021.49   84.26  5021.6   84.28  5023.9   84.69 5024.39   84.77
  5024.5   84.79 5024.61   84.81  5035.1   86.66  5063.1   86.35  5080.2    85.9
  5090.4   85.63  5108.4   85.82  5130.3   86.06  5146.5   85.73  5147.3   85.72
  5177.1   85.51  5188.1    86.2  5248.1      87  5388.1    86.8  5478.1      86
  5888.1    86.8  5948.1      87  6028.1    86.9  6430.4   86.98  6528.1      87
  6568.1    87.1  6808.1    87.8  6918.1    86.7  7028.1    87.6  7138.1    87.3
  7198.1    90.5  7208.1    90.7  7228.1    90.3  7248.1    90.4  7268.1    89.2
  7276.2   89.04  7298.1    88.6  7308.1    88.8  7328.1    89.9  7588.1    89.4
  7608.1    87.8  7618.1    86.6  7628.1    85.9  7648.1    87.8  7738.1    88.6
  8158.1    87.8  8168.1    88.1  9098.1    87.4  9108.1    87.1  9128.1    87.5
  9188.1    87.7  9198.1    88.1  9548.1    87.7  9568.1    88.4  9578.1    88.5
  9658.6    88.5  9660.9    89.5
BR U #Mann= 6
  2715.9      .2  3356.1     .14  4976.2    .035  5035.1     .14  6430.4      .1
  7276.2     .99
BR U Banks=4976.2,5035.1
BR D #Sta/Elev= 97
  2715.9   89.56  2885.9   88.46  2965.9   88.16  3195.9   87.66  3235.9   87.56
  3356.1   87.79  3445.9   87.96  3715.9   87.36  3815.9   86.56  4115.9   86.36
  4265.9   85.76  4335.9   87.36  4475.9   86.76  4695.9   86.66  4845.9   85.86
  4864.3   85.33  4877.6   85.23  4901.6   85.34  4932.8   85.69    4946   86.72
  4952.4   87.22  4955.8   87.06  4976.2   86.13 4976.89   85.89    4977   85.86
 4977.11   85.82  4977.3   85.75 4981.91   84.18    4982   84.15  4982.6   83.94
  4982.7   83.91  4991.6   80.47    4993   79.07  4995.1   77.99  4997.6   77.01
  5000.5    76.8  5003.6   77.36  5007.1   79.13    5009   80.74  5018.6    83.6
  5018.7   83.63 5021.49   84.12  5021.6   84.14  5023.9   84.55 5024.39   84.63
  5024.5   84.65 5024.61   84.67  5035.1   86.52  5063.1   86.21  5080.2   85.76
  5090.4   85.49  5108.4   85.68  5130.3   85.92  5146.5   85.59  5147.3   85.58
  5177.1   85.37  5188.1   86.06  5248.1   86.86  5388.1   86.66  5478.1   85.86
  5888.1   86.66  5948.1   86.86  6028.1   86.76  6430.4   86.84  6528.1   86.86
  6568.1   86.96  6808.1   87.66  6918.1   86.56  7028.1   87.46  7138.1   87.16
  7198.1   90.36  7208.1   90.56  7228.1   90.16  7248.1   90.26  7268.1   89.06
  7276.2    88.9  7298.1   88.46  7308.1   88.66  7328.1   89.76  7588.1   89.26
  7608.1   87.66  7618.1   86.46  7628.1   85.76  7648.1   87.66  7738.1   88.46
  8158.1   87.66  8168.1   87.96  9098.1   87.26  9108.1   86.96  9128.1   87.36
  9188.1   87.56  9198.1   87.96  9548.1   87.56  9568.1   88.26  9578.1   88.36
  9658.6   88.36  9660.9   89.36
BR D #Mann= 6
  2715.9      .2  3356.1     .14  4976.2    .035  5035.1     .14  6430.4      .1
  7276.2     .99
BR D Banks=4976.2,5035.1
BC Design=,, 0 ,, 0 ,,,,,,

Type RM Length L Ch R = 1 ,93213.9 ,494.8,494.8,494.8
BEGIN DESCRIPTION:
Downstream Section of Bridge/Culvert/Weir
END DESCRIPTION:
XS GIS Cut Line= 6
      3095475.72     13897445.42      3094406.53     13895577.59
      3094343.82     13895479.34      3094315.36     13895443.29
      3094209.55     13895313.05      3090533.12     13892783.65
#Sta/Elev= 30
  2715.9   89.57  3356.1    87.8  4265.9   85.77  4335.9   87.37  4877.6   85.24
  4932.8    85.7  4952.4   87.23  4976.2   86.14  4991.6   80.48  4997.6   77.02
  5000.5   76.81  5018.7   83.64  5035.1   86.53  5177.1   85.38  5248.1   86.87
  5478.1   85.87  6430.4   86.85  7138.1   87.17  7208.1   90.57  7276.2   88.91
  7328.1   89.77  7588.1   89.27  7628.1   85.77  7648.1   87.67  7738.1   88.47
  9108.1   86.97  9198.1   87.97  9548.1   87.57  9658.6   88.37  9660.9   89.37
#Mann= 6 , 1 , 0
  2715.9      .2       0  3356.1     .14       0  4976.2    .035       0
  5035.1     .14       0  6430.4      .1       0  7276.2     .99       0
#XS Ineff= 2 , 0
       0    4977    85.8    7225       0    90.3
Permanent Ineff=
       F       F
Bank Sta=4976.2,5035.1
XS Rating Curve= 0
Exp/Cntr=.5,.3

Type RM Length L Ch R = 1 ,92719.1 ,1105.6,1029.8,1026.7
BEGIN DESCRIPTION:
Cross Section 92719.1
END DESCRIPTION:
XS GIS Cut Line= 4
      3095892.79     13896731.89      3095455.27     13896186.58
      3094663.65     13895083.96      3092562.07     13893208.57
#Sta/Elev= 30
  3016.2    88.8  3686.2    86.3  3785.3    87.6  4095.3    86.1  4165.3    87.4
  4245.3    87.6  4335.3    85.6  4765.3    85.3  4969.3   87.17  4997.3   77.38
  5002.9   77.34  5039.9   86.56    5063   87.37  5482.7    87.3  5642.7    88.3
  6022.7    86.5  6102.7    88.2  6192.7    88.4  6252.7    86.7  6482.7      87
  6522.7      88  7017.6   86.62  7384.5   87.33  7512.7    87.7  7552.7    86.8
  7572.7    87.8  7832.7    87.6  7852.7    88.3  7862.7    89.5  7889.3      91
#Mann= 5 , 1 , 0
  3016.2     .14       0  4969.3    .035       0  5039.9     .14       0
  7017.6      .1       0  7384.5      .2       0
Bank Sta=4969.3,5039.9
XS Rating Curve= 0
Exp/Cntr=.3,.1

Type RM Length L Ch R = 1 ,91689.3 ,610.4,659.8,847.6
BEGIN DESCRIPTION:
Cross Section 91689.3
END DESCRIPTION:
XS GIS Cut Line= 5
      3096757.85     13895797.48      3096265.75     13895442.08
      3095690.88     13894641.03      3095285.64     13894348.88
      3093363.12     13892699.67
#Sta/Elev= 30
  3182.9    88.2  3312.9    86.9  3362.9    85.5  3442.9    85.2  3752.9   87.95
  3909.9    85.8  4347.2   86.37  4425.6   86.47  4895.9    85.7  4945.9   88.82
  4964.5   87.92  4995.4    78.4  4999.6    76.3  5002.3   76.59  5005.1   78.34
  5017.9   80.69  5038.5   88.38  5046.9   89.48  5105.9    85.7  5585.4    85.1
  5925.4      87  6031.2   86.44  6125.4    84.7  6395.4    84.5  6615.4    84.7
  6745.4    86.2  6975.4    85.2  7532.1   87.24    7633   87.48  7808.4    87.9
#Mann= 9 , 1 , 0
  3182.9     .99       0  3752.9      .1       0  4347.2     .07       0
  4425.6     .14       0  4964.5    .035       0  5038.5     .14       0
  6031.2      .1       0  7532.1     .14       0    7633      .2       0
Bank Sta=4964.5,5038.5
XS Rating Curve= 0
Exp/Cntr=.3,.1

Type RM Length L Ch R = 1 ,91029.5 ,660.6,917.2,1012.6
BEGIN DESCRIPTION:
Cross Section 91029.5-Interpolated
END DESCRIPTION:
XS GIS Cut Line= 5
      3096741.93     13895454.17      3096129.15      13894212.5
      3095790.51     13893889.98      3095027.56     13892877.09
      3093918.92     13891768.45
#Sta/Elev= 30
  3289.1   87.25  3339.5   86.43  3859.1   86.08  3879.1   87.11  4249.1   85.36
  4409.1   86.71    4615   85.84  4873.8   84.74  4969.2   86.33  4977.6   80.79
  4987.6   78.87  4989.7   77.28  5002.1    75.6  5010.8   76.69  5013.5   79.41
  5013.8   78.11  5063.8      86  5093.8   84.04  5364.1   85.09  5701.4   84.82
  5781.4   85.84  6111.4   84.36  6761.3    85.8  6909.5   84.58  7009.5   86.62
  7229.5   84.21  7414.2   85.23  7509.5   86.77  7719.5   86.01  7977.3   87.09
#Mann= 9 , 1 , 0
  3289.1      .2       0  3289.1      .1       0  3339.5     .07       0
    4615     .14       0  4969.2    .035       0  5063.8     .07       0
  5364.1     .14       0  6761.3      .1       0  7414.2      .2       0
#XS Ineff= 2 , 0
       0  3879.1   87.11  7009.5       0   86.62
Permanent Ineff=
       F       F
Bank Sta=4969.2,5063.8
XS Rating Curve= 0
Exp/Cntr=.3,.1

Type RM Length L Ch R = 1 ,90112.3 ,824.7,780.2,508.3
BEGIN DESCRIPTION:
Cross Section 90112.3
END DESCRIPTION:
XS GIS Cut Line= 5
      3096786.66     13894908.68      3096680.41     13894339.46
      3096670.98     13893434.75      3095455.27     13891719.56
      3094797.88     13890788.25
#Sta/Elev= 30
  3658.2    87.5  3888.2    84.8  4128.2    85.7  4138.2    85.1  4237.2    85.5
  4897.2      84  4951.3   85.92  4969.2   85.35  4977.6   79.81  4987.6   77.89
  4988.6   76.72  4989.7    76.3  5002.1   74.62  5010.8   75.71  5013.4    78.4
  5030.5   85.47  5041.3    85.9  5127.2    83.7    5232    84.8    5248   84.53
    5502    84.8    5612    84.1    5702    84.4    5842    83.8    6622      84
  6799.7   84.73  7156.4   85.23  7544.7   85.78  8014.3    85.3  8384.3    86.7
#Mann= 7 , 1 , 0
  3658.2     .07       0  4969.2    .035       0  5030.5     .14       0
    5248     .07       0  6799.7     .14       0  7156.4      .1       0
  7544.7      .2       0
Bank Sta=4969.2,5030.5
XS Rating Curve= 0
Exp/Cntr=.3,.1

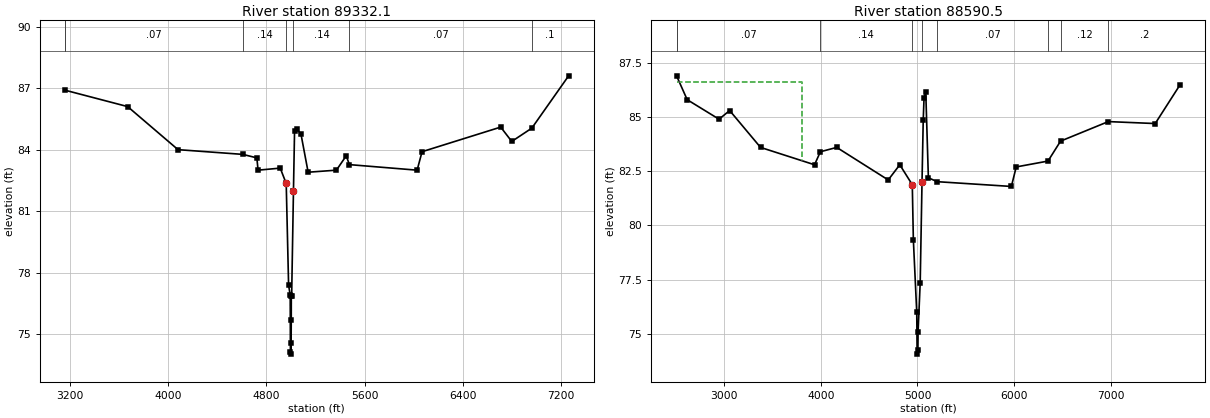
Type RM Length L Ch R = 1 ,89332.1 ,524.5,741.6,1063.9
BEGIN DESCRIPTION:
Cross Section 89332.1
END DESCRIPTION:
XS GIS Cut Line= 6
      3096878.31     13894820.09      3097189.31     13893774.01
      3097217.58     13893114.33      3096425.96     13892388.67
       3095662.6     13891634.74      3095545.95     13891472.26
#Sta/Elev= 30
  3162.5    86.9  3672.5    86.1  4082.5      84  4608.7   83.77  4723.8    83.6
  4733.8      83  4914.1    83.1  4962.8   82.35  4982.2   77.39  4995.3    76.9
  4996.9   74.14  5000.7   74.03  5002.7   74.59  5003.8   75.68  5004.2   76.88
    5007   76.86  5021.8      82  5030.7   84.93    5047   85.02  5082.9   84.76
  5141.2    82.9  5371.2      83  5451.2    83.7  5476.9   83.27  6028.1      83
  6068.1    83.9  6708.1    85.1  6798.1    84.4  6961.5   85.05    7261    87.6
#Mann= 7 , 1 , 0
  3162.5      .2       0  3162.5     .07       0  4608.7     .14       0
  4962.8    .035       0  5021.8     .14       0  5476.9     .07       0
  6961.5      .1       0
Bank Sta=4962.8,5021.8
XS Rating Curve= 0
Exp/Cntr=.3,.1

Type RM Length L Ch R = 1 ,88590.5 ,1067.9,1155.7,1201
BEGIN DESCRIPTION:
Cross Section 88590.5
END DESCRIPTION:
XS GIS Cut Line= 6
       3096953.6     13894810.44      3097518.58     13893662.81
      3097612.75     13892844.75      3097653.95     13892562.26
      3097495.04     13892409.24      3096524.53     13889987.31
#Sta/Elev= 30
  2504.3    86.9  2614.3    85.8  2944.3    84.9  3054.3    85.3  3374.3    83.6
  3933.5    82.8  3994.3    83.4  4163.5    83.6  4696.9    82.1  4816.9    82.8
  4946.4   81.88  4957.3   79.35  4992.6   75.99  4996.4   74.07  5004.5   74.26
  5006.4   75.11  5028.3   77.36  5047.1      82  5059.8   84.88  5068.2   85.89
    5086   86.15    5113    82.2  5204.3   82.02    5973    81.8    6023    82.7
  6352.2   82.97  6482.6   83.89  6977.3   84.79    7463    84.7  7722.2    86.5
#Mann= 9 , 1 , 0
  2504.3      .2       0  2504.3     .07       0  3994.3     .14       0
  4946.4    .035       0  5047.1     .14       0  5204.3     .07       0
  6352.2      .1       0  6482.6     .12       0  6977.3      .2       0
#XS Ineff= 2 , 0
       0    3800    86.6               0
Permanent Ineff=
       F       F
Bank Sta=4946.4,5047.1
XS Rating Curve= 0
Exp/Cntr=.3,.1