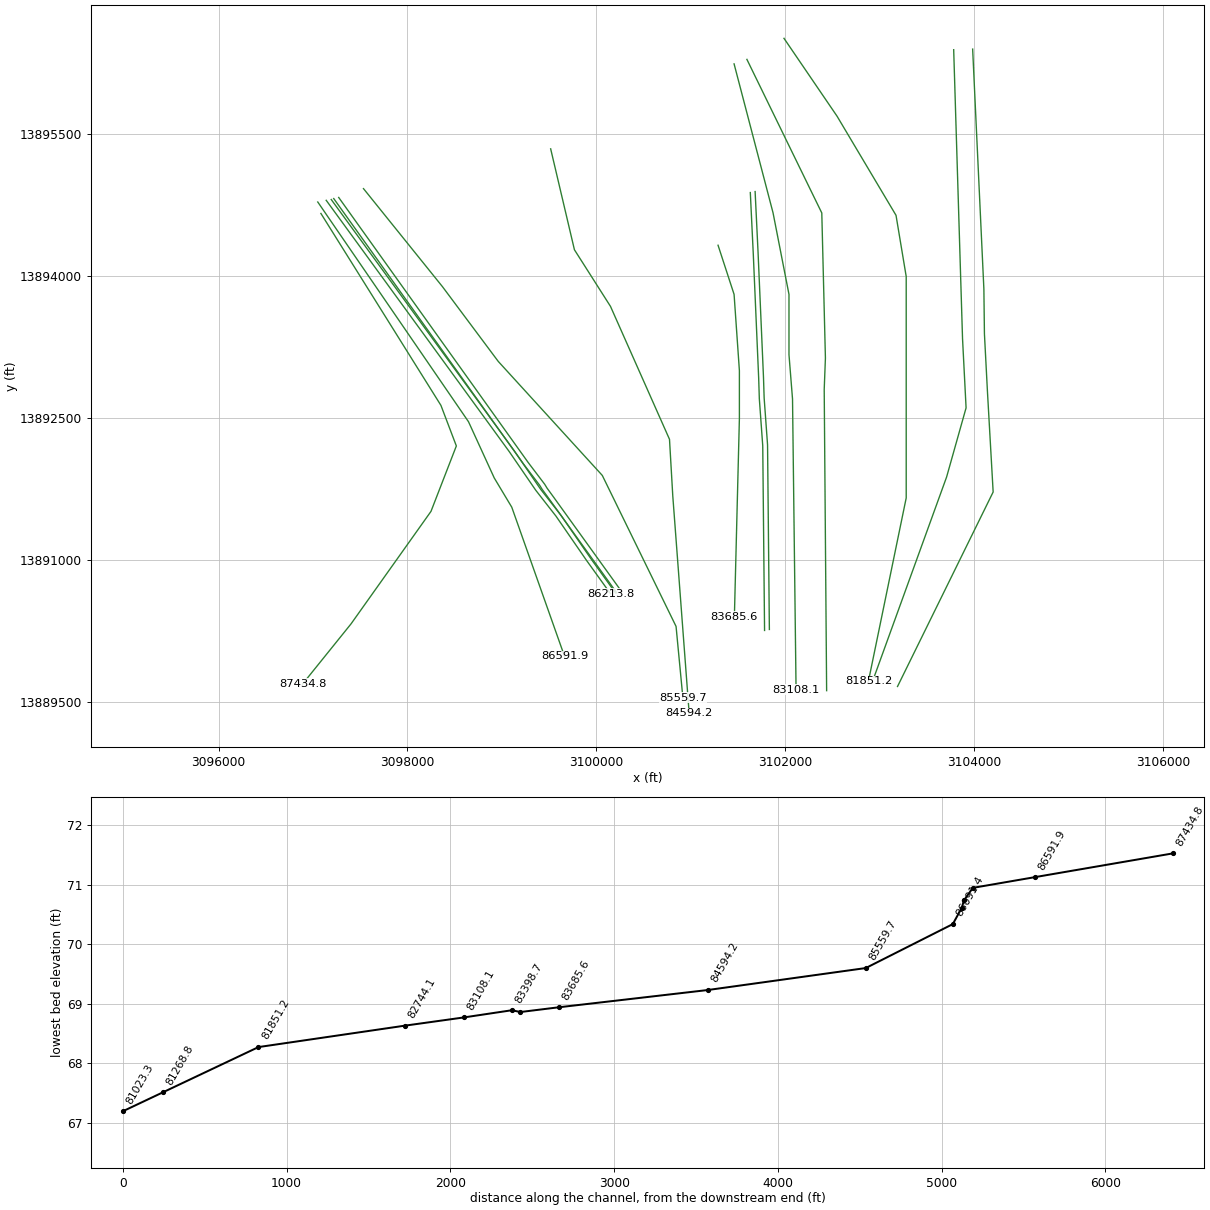
HEC-RAS study P118-00-00.PRJ: P118-00-00

--- P118-00-00.g01 (geometry) --- (continued)

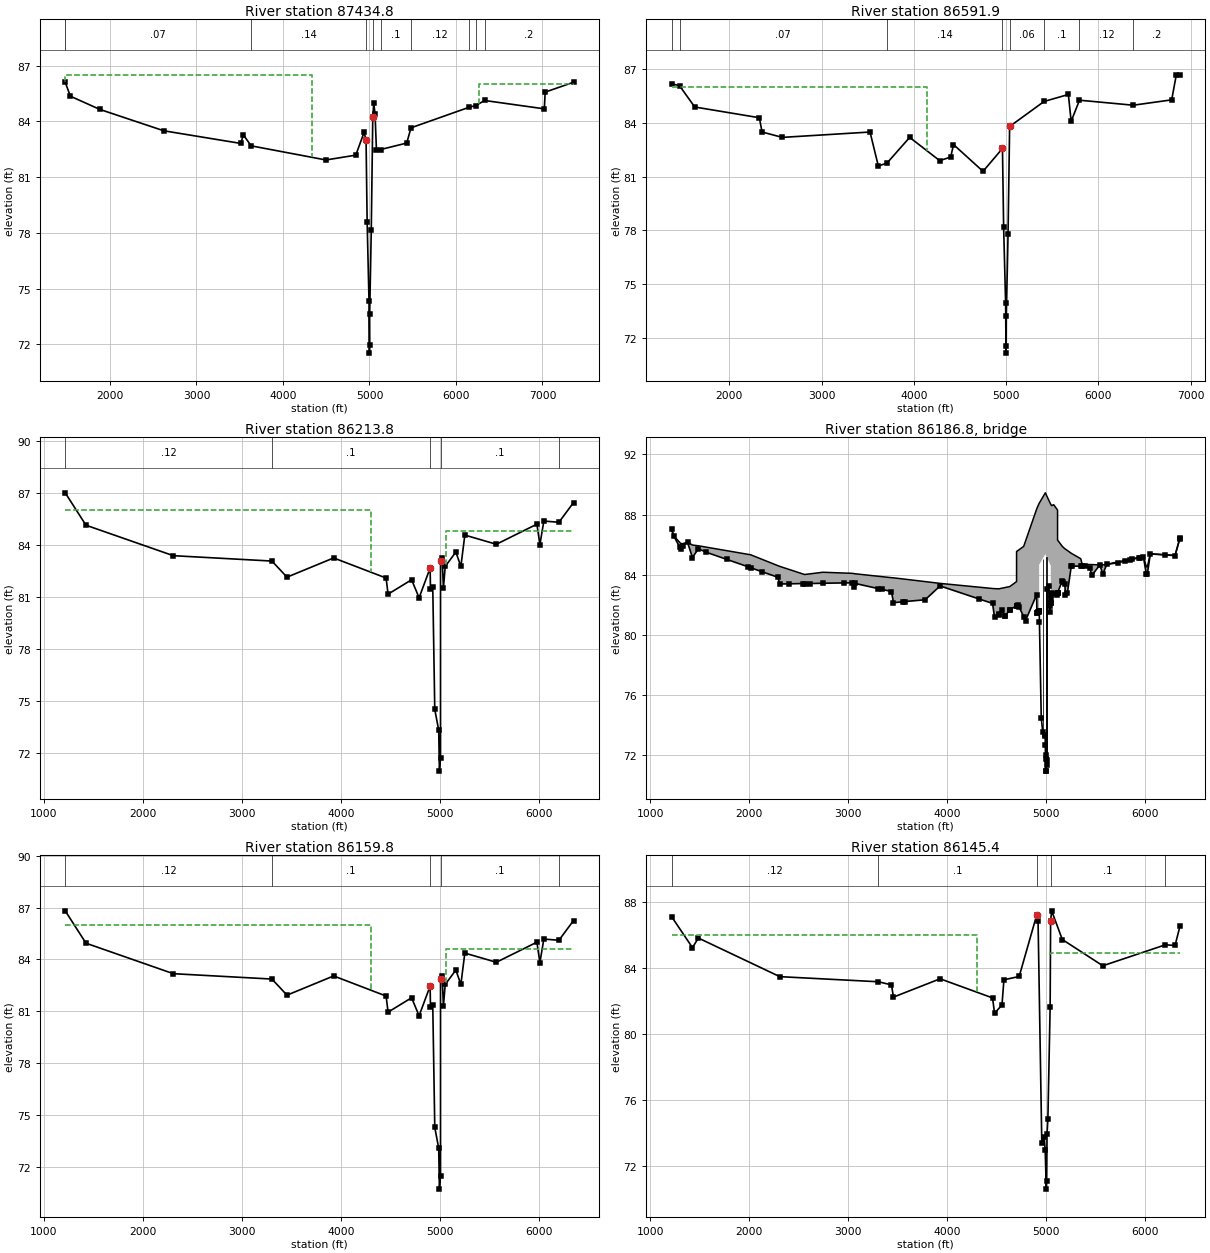
Type RM Length L Ch R = 1 ,87434.8 ,268.3,842.9,1342.1
BEGIN DESCRIPTION:
Cross Section 87434.8
END DESCRIPTION:
XS GIS Cut Line= 6
      3097083.07     13894663.31       3098354.3     13892632.88
      3098517.63      13892203.8      3098249.02     13891511.61
       3097402.1     13890321.43      3096888.54     13889684.84
#Sta/Elev= 30
  1482.2    86.1  1542.2   85.35  1882.2   84.64  2622.2   83.49  3512.2   82.81
  3542.2   83.27  3632.1   82.68  4496.9   81.92  4842.1   82.18  4938.1   83.41
  4960.8   82.98  4973.2   78.61  4994.9   74.31  4999.5   71.53  5001.4   71.95
  5002.5   73.62  5021.1   78.18  5038.3   84.21  5049.5   84.97  5064.8    84.4
  5080.9   82.43  5128.1   82.48  5430.9   82.83  5480.4   83.65  6155.1   84.76
  6231.3   84.85  6331.2   85.12  7021.7   84.67  7031.7   85.57  7359.6    86.1
#Mann= 10 , 1 , 0
  1482.2      .2       0  1482.2     .07       0  3632.1     .14       0
  4960.8    .035       0  5038.3     .14       0  5128.1      .1       0
  5480.4     .12       0  6155.1      .1       0  6231.3     .12       0
  6331.2      .2       0
#XS Ineff= 2 , 0
       0    4335    86.5  6270.9       0      86
Permanent Ineff=
       F       F
Bank Sta=4960.8,5038.3
XS Rating Curve= 0
Exp/Cntr=.3,.1

Type RM Length L Ch R = 1 ,86591.9 ,284.6,378.1,440.5
BEGIN DESCRIPTION:
Cross Section 86591.9-Interpolated
END DESCRIPTION:
XS GIS Cut Line= 5
      3097049.88     13894784.42      3098646.49     13892459.77
        3098919.      13891865.2       3099104.8     13891555.53
      3099663.93     13889976.83
#Sta/Elev= 30
    1375    86.2  1460.2   86.09    1625    84.9    2325    84.3    2355    83.5
    2575    83.2    3525    83.5    3615    81.6  3708.7   81.76    3955    83.2
  4279.9    81.9  4399.9    82.1  4429.9    82.8  4749.9    81.3  4960.8   82.58
  4973.2   78.21  4994.9   73.91  4999.5   71.13  5001.4   71.55  5002.5   73.22
  5021.1   77.78  5038.3   83.81  5411.9   85.21  5675.1    85.6  5705.1    84.1
  5795.7   85.28  6378.6      85  6795.1    85.3  6845.1    86.7  6885.1    86.7
#Mann= 8 , 1 , 0
    1375      .2       0  1460.2     .07       0  3708.7     .14       0
  4960.8    .035       0  5038.3     .06       0  5411.9      .1       0
  5795.7     .12       0  6378.6      .2       0
#XS Ineff= 2 , 0
       0    4140      86               0
Permanent Ineff=
       F       F
Bank Sta=4960.8,5038.3
XS Rating Curve= 0
Exp/Cntr=.5,.3

Type RM Length L Ch R = 1 ,86213.8 ,54,54,54
BEGIN DESCRIPTION:
Upstream Section of Bridge/Culvert/Weir
END DESCRIPTION:
XS GIS Cut Line= 6
      3097139.23     13894802.41      3099077.56     13892144.42
      3099358.02     13891735.93      3099572.87     13891461.35
      3099896.52     13890992.86      3100149.98     13890641.25
#Sta/Elev= 30
  1214.8   87.02  1424.8   85.15  2307.5   83.39  3303.9   83.08    3456   82.15
  3927.4   83.26  4457.4    82.1  4477.4   81.17 4715.08      82 4790.94   80.96
 4902.47   82.68  4905.6   81.48    4929   81.58 4949.37   74.51 4989.13   73.31
 4996.17   70.95  5007.4   71.68 5007.48   83.07 5023.93   83.25 5036.71   81.52
  5054.9   82.77 5162.34    83.6    5213   82.77    5253   84.58  5571.5   84.05
  5981.5   85.21  6011.5   84.03  6051.5   85.39  6203.9   85.32  6351.5   86.46
#Mann= 5 , 1 , 0
  1214.8     .12       0  3303.9      .1       0 4902.47    .035       0
 5007.48      .1       0  6203.9     .14       0
#XS Ineff= 2 , 0
       0    4300      86  5062.6       0    84.8
Permanent Ineff=
       F       F
Bank Sta=4902.47,5007.48
XS Rating Curve= 0
Exp/Cntr=.5,.3

Type RM Length L Ch R = 3 ,86186.8 ,,,
BEGIN DESCRIPTION:
VETERANS MEMORIAL BOULEVARD, SKEW ANGLE OF 30 DEGREES
Structure ID: P18-45
END DESCRIPTION:
Bridge Culvert--1,0,-1,-1, 0
Deck Dist Width WeirC Skew NumUp NumDn MinLoCord MaxHiCord MaxSubmerge Is_Ogee
10,34,2.6,0, 60, 60, , , .95, 0, 1,1,,
  1214.8  1234.8  1304.8  1324.8  1374.8  1424.8  1484.8  2013.9  2287.5  2307.5
  2557.9  2742.9  3037.5  3057.5    3066    3436    3456    3776  3927.4  4457.4
  4477.4  4522.4  4552.4 4580.49 4631.73 4699.89    4700 4715.08  4771.9 4790.94
 4902.47  4905.6 4928.05 4928.14  4990.5 5045.83 5045.94  5054.9  5075.4 5107.01
  5114.2 5114.31 5162.34 5188.27    5193    5213    5253  5348.4  5363.4  5441.5
  5461.5  5541.5  5571.5  5611.5  5981.5  6011.5  6021.5  6051.5  6301.5  6351.5
   87.02    86.6   86.09   86.07   86.17   85.98   85.93   85.33   84.61   84.56
   84.02   84.17    84.1   84.08   84.07   83.81    83.8   83.55   83.43   83.09
   83.08   83.07   83.11   83.15   83.22   83.55   85.55   85.62   85.89   86.25
   88.36   88.42   88.75   88.75   89.45   88.68   88.68    88.6   88.66   88.37
   88.31   86.31   85.89   85.73   85.71   85.62   85.43   85.07    84.7   84.68
   84.68   84.66   84.66    84.7   85.22   84.53   84.53    85.4   85.29   86.46
   87.02    86.6   85.72   85.94   86.16   85.15   85.73   84.47   83.84   83.39
   83.42   83.44   83.47   83.22   83.43   82.89   82.15   82.34   83.26    82.1
   81.17   81.35   81.67   81.23   81.68   81.94   81.94      82   81.22   80.96
   82.68   81.48   81.58   84.67   85.37    84.6   82.15   82.77   82.74   82.69
   82.81   82.81    83.6   83.39   82.63   82.77   84.58   84.57   84.57   84.42
   83.96   84.66   84.05   84.69   85.21   84.03   84.05   85.39   85.28   86.46
  1214.8  1234.8  1304.8  1324.8  1374.8  1424.8  1484.8  2013.9  2287.5  2307.5
  2557.9  2742.9  3037.5  3057.5    3066    3436    3456    3776  3927.4  4457.4
  4477.4  4522.4  4552.4 4580.49 4631.73 4699.89    4700 4715.08  4771.9 4790.94
 4902.47  4905.6 4928.05 4928.14  4990.5 5045.83 5045.94  5054.9  5075.4 5107.01
  5114.2 5114.31 5162.34 5188.27    5193    5213    5253  5348.4  5363.4  5441.5
  5461.5  5541.5  5571.5  5611.5  5981.5  6011.5  6021.5  6051.5  6301.5  6351.5
   87.02    86.6   86.09   86.07   86.17   85.98   85.93   85.33   84.61   84.56
   84.02   84.17    84.1   84.08   84.07   83.81    83.8   83.55   83.43   83.09
   83.08   83.07   83.11   83.15   83.22   83.55   85.55   85.62   85.89   86.25
   88.36   88.42   88.75   88.75   89.45   88.68   88.68    88.6   88.66   88.37
   88.31   86.31   85.89   85.73   85.71   85.62   85.43   85.07    84.7   84.68
   84.68   84.66   84.66    84.7   85.22   84.53   84.53    85.4   85.29   86.46
   86.91   86.49   85.61   85.83   86.05   85.04   85.62   84.36   83.73   83.28
   83.31   83.33   83.36   83.11   83.32   82.78   82.04   82.23   83.15   81.99
   81.06   81.24   81.56   81.12   81.57   81.83   81.83   81.89   81.11   80.85
   82.57   81.37   81.47   84.56   85.26   84.49   82.04   82.66   82.63   82.58
    82.7    82.7   83.49   83.28   82.52   82.66   84.47   84.46   84.46   84.31
   83.85   84.55   83.94   84.58    85.1   83.92   83.94   85.28   85.17   86.35
Pier Skew, UpSta & Num, DnSta & Num=  ,4964.5, 2 ,4964.5, 2 , 0 , 0 , 0 ,,
       2       2
   72.53   86.08
       2       2
   72.42   85.97
Pier Skew, UpSta & Num, DnSta & Num=  ,5001.8, 2 ,5001.8, 2 , 0 , 0 , 0 ,,
       2       2
   70.64   86.22
       2       2
   70.53   86.11
Abutment Skew #Up #Dn= , 2 , 2
 4927.94  4929.1
   84.67   81.55
 4927.94  4929.1
   84.56   81.44
Abutment Skew #Up #Dn= , 2 , 2
  5042.8 5046.03
   81.94    84.6
  5042.8 5046.03
   81.83   84.49
BR Coef= 1 , 1 , 0 ,1.25, 0 ,,,.8,0,2,0,
WSPro=,,,, 1 ,,,, 0 ,,,, 0 ,,,,-1 ,-1 ,-1 , 0 , 0 , 0 , 0 , 0
BR U #Sta/Elev= 113
  1214.8   87.02  1234.8    86.6  1293.9   85.86  1304.8   85.72  1324.8   85.94
  1374.8   86.16  1424.8   85.15  1484.8   85.73  1564.8    85.5  1768.9   85.03
  1988.9   84.53  2013.9   84.47  2128.9    84.2  2287.5   83.84  2307.5   83.39
  2397.9    83.4  2537.9   83.42  2557.9   83.42  2612.9   83.42  2742.9   83.44
  2952.9   83.46  3037.5   83.47  3057.5   83.22    3066   83.43  3303.9   83.08
  3342.9   83.03    3436   82.89    3456   82.15  3547.9    82.2  3567.9   82.22
    3776   82.34  3927.4   83.26  4322.9   82.39  4457.4    82.1  4477.4   81.17
  4522.4   81.35    4527    81.4  4552.4   81.67  4579.7   81.24 4580.49   81.23
 4631.73   81.68  4632.2   81.68 4699.89   81.94    4700   81.94 4700.11   81.94
 4715.08      82  4723.1   81.89  4771.9   81.22 4790.94   80.96 4902.47   82.68
  4905.6   81.48  4906.9   81.49  4911.7   81.51  4917.4   81.53 4928.05   81.58
 4928.14   81.58    4929   81.58  4929.1   81.55    4931   80.89 4949.37   74.51
  4964.5   73.54  4985.5   73.34 4989.13   73.31  4990.5    72.7  4992.6   71.77
 4996.17   70.95 4999.13   70.97 5001.83   72.04 5005.13   71.34  5007.4   71.68
 5007.48   83.07 5023.93   83.25 5036.71   81.52  5042.8   81.94 5045.83   82.15
 5045.94   82.15  5049.6   82.41  5052.8   82.63  5054.9   82.77  5075.4   82.74
 5107.01   82.69 5114.09   82.81  5114.2   82.81 5114.31   82.81 5162.34    83.6
  5169.9   83.54 5188.27   83.39    5193   82.63    5213   82.77    5253   84.58
  5265.1   84.58  5348.4   84.57  5363.4   84.57  5391.5   84.57  5441.5   84.42
  5461.5   83.96  5541.5   84.66  5571.5   84.05  5611.5   84.69  5721.5    84.8
  5793.4   84.91  5843.4   84.99  5863.4   85.02  5933.4   85.13  5943.4   85.15
  5981.5   85.21  6011.5   84.03  6021.5   84.05  6051.5   85.39  6203.9   85.32
  6301.5   85.28  6348.4   86.39  6351.5   86.46
BR U #Mann= 5
  1214.8     .12  3303.9      .1 4902.47    .035 5007.48      .1  6203.9     .14
BR U Banks=4902.47,5007.48
BR D #Sta/Elev= 113
  1214.8   86.91  1234.8   86.49  1293.9   85.75  1304.8   85.61  1324.8   85.83
  1374.8   86.05  1424.8   85.04  1484.8   85.62  1564.8   85.39  1768.9   84.92
  1988.9   84.42  2013.9   84.36  2128.9   84.09  2287.5   83.73  2307.5   83.28
  2397.9   83.29  2537.9   83.31  2557.9   83.31  2612.9   83.31  2742.9   83.33
  2952.9   83.35  3037.5   83.36  3057.5   83.11    3066   83.32  3303.9   82.97
  3342.9   82.92    3436   82.78    3456   82.04  3547.9   82.09  3567.9   82.11
    3776   82.23  3927.4   83.15  4322.9   82.28  4457.4   81.99  4477.4   81.06
  4522.4   81.24    4527   81.29  4552.4   81.56  4579.7   81.13 4580.49   81.12
 4631.73   81.57  4632.2   81.57 4699.89   81.83    4700   81.83 4700.11   81.83
 4715.08   81.89  4723.1   81.78  4771.9   81.11 4790.94   80.85 4902.47   82.57
  4905.6   81.37  4906.9   81.38  4911.7    81.4  4917.4   81.42 4928.05   81.47
 4928.14   81.47    4929   81.47  4929.1   81.44    4931   80.78 4949.37    74.4
  4964.5   73.43  4985.5   73.23 4989.13    73.2  4990.5   72.59  4992.6   71.66
 4996.17   70.84 4999.13   70.86 5001.83   71.93 5005.13   71.23  5007.4   71.57
 5007.48   82.96 5023.93   83.14 5036.71   81.41  5042.8   81.83 5045.83   82.04
 5045.94   82.04  5049.6    82.3  5052.8   82.52  5054.9   82.66  5075.4   82.63
 5107.01   82.58 5114.09    82.7  5114.2    82.7 5114.31    82.7 5162.34   83.49
  5169.9   83.43 5188.27   83.28    5193   82.52    5213   82.66    5253   84.47
  5265.1   84.47  5348.4   84.46  5363.4   84.46  5391.5   84.46  5441.5   84.31
  5461.5   83.85  5541.5   84.55  5571.5   83.94  5611.5   84.58  5721.5   84.69
  5793.4    84.8  5843.4   84.88  5863.4   84.91  5933.4   85.02  5943.4   85.04
  5981.5    85.1  6011.5   83.92  6021.5   83.94  6051.5   85.28  6203.9   85.21
  6301.5   85.17  6348.4   86.28  6351.5   86.35
BR D #Mann= 5
  1214.8     .12  3303.9      .1 4902.47    .035 5007.48      .1  6203.9     .14
BR D Banks=4902.47,5007.48
BC Design=,, 0 ,, 0 ,,,,,,

Type RM Length L Ch R = 1 ,86159.8 ,14.4,14.4,14.4
BEGIN DESCRIPTION:
Downstream Section of Bridge/Culvert/Weir
END DESCRIPTION:
XS GIS Cut Line= 6
      3097192.62     13894810.45      3099130.96     13892152.46
      3099411.42     13891743.97      3099626.27     13891469.39
      3099949.92      13891000.9      3100203.38      13890649.3
#Sta/Elev= 30
  1214.8   86.81  1424.8   84.94  2307.5   83.18  3303.9   82.87    3456   81.94
  3927.4   83.05  4457.4   81.89  4477.4   80.96 4715.08   81.79 4790.94   80.75
 4902.47   82.47  4905.6   81.27    4929   81.37 4949.37    74.3 4989.13    73.1
 4996.17   70.74  5007.4   71.47 5007.48   82.86 5023.93   83.04 5036.71   81.31
  5054.9   82.56 5162.34   83.39    5213   82.56    5253   84.37  5571.5   83.84
  5981.5      85  6011.5   83.82  6051.5   85.18  6203.9   85.11  6351.5   86.25
#Mann= 5 , 1 , 0
  1214.8     .12       0  3303.9      .1       0 4902.47    .035       0
 5007.48      .1       0  6203.9     .14       0
#XS Ineff= 2 , 0
       0    4300      86  5062.6       0    84.6
Permanent Ineff=
       F       F
Bank Sta=4902.47,5007.48
XS Rating Curve= 0
Exp/Cntr=.5,.3

Type RM Length L Ch R = 1 ,86145.4 ,54,54,54
BEGIN DESCRIPTION:
Upstream Section of Bridge/Culvert/Weir
END DESCRIPTION:
XS GIS Cut Line= 6
      3097218.91     13894820.79       3099225.6     13892017.42
      3099400.73     13891786.73      3099425.72     13891745.74
       3099494.5     13891651.49      3100216.67     13890649.86
#Sta/Elev= 30
  1214.8   87.12  1424.8   85.25  1484.8   85.83  2307.5   83.49  3303.9   83.18
    3436   82.99    3456   82.25  3927.4   83.36  4457.4    82.2  4477.4   81.27
  4552.4   81.77 4572.31    83.3  4726.3    83.5 4903.34   87.22 4917.16   86.89
 4955.02   73.39 4979.38   73.75 4989.21   72.96 5000.78   70.61 5004.35   71.12
 5007.74   73.96 5016.36   74.84 5039.24   81.66 5044.02   86.86 5054.55   87.48
 5162.34   85.74  5571.5   84.15  6203.9   85.42  6301.5   85.38  6351.5   86.56
#Mann= 5 , 1 , 0
  1214.8     .12       0  3303.9      .1       0 4903.34    .035       0
 5044.02      .1       0  6203.9     .14       0
#XS Ineff= 2 , 0
       0    4300      86 5042.13       0    84.9
Permanent Ineff=
       F       F
Bank Sta=4903.34,5044.02
XS Rating Curve= 0
Exp/Cntr=.5,.3

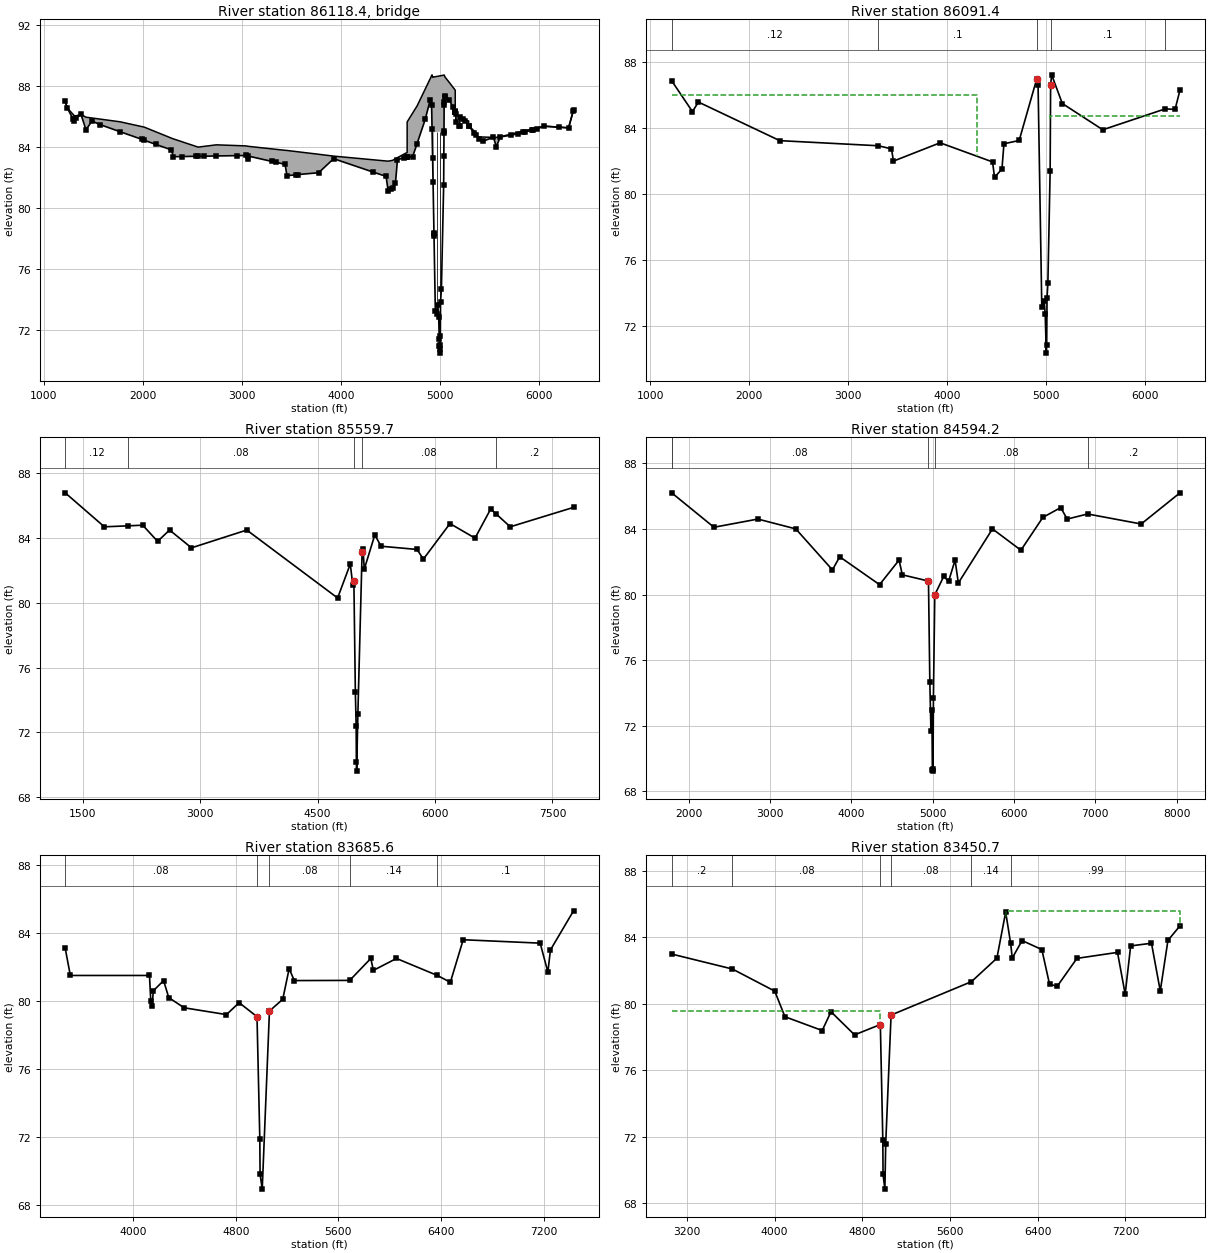
Type RM Length L Ch R = 3 ,86118.4 ,,,
BEGIN DESCRIPTION:
VETERANS MEMORIAL BOULEVARD, SKEW ANGLE OF 30 DEGREES
Structure ID: P18-44
END DESCRIPTION:
Bridge Culvert--1,0,-1,-1, 0
Deck Dist Width WeirC Skew NumUp NumDn MinLoCord MaxHiCord MaxSubmerge Is_Ogee
10,34,2.6,0, 60, 60, , , .95, 0, 1,1,,
  1214.8  1234.8  1304.8  1324.8  1374.8  1424.8  1484.8  1768.9  2013.9  2287.5
  2307.5  2557.9  2742.9  3037.5  3057.5    3066    3436    3456    3776  3927.4
  4457.4  4477.4  4522.4  4552.4 4572.31 4670.09  4670.2  4726.3  4770.5 4852.97
 4903.34 4917.16  4921.7  4927.4 4932.05  4941.1 4941.19 5042.46 5044.02 5054.55
 5096.22  5156.2 5156.31 5162.08 5162.34 5199.75 5199.93 5253.52  5291.5  5291.7
  5348.4  5363.4  5391.5  5441.5  5541.5  5571.5  5611.5  6051.5  6301.5  6351.5
   87.02    86.6   86.09   86.07   86.17   85.98   85.93   85.68   85.33   84.61
   84.56   84.02   84.17    84.1   84.08   84.07   83.81    83.8   83.55   83.43
   83.11    83.1   83.15   83.26   83.33   83.67   85.67   86.26   86.72   87.83
   88.51    88.7   88.76    88.6   88.61   88.62   88.62   88.74   88.75    88.6
   88.26   87.75    86.3    86.2   85.69   85.41   86.01   85.75   85.74   85.43
   85.07   84.82   84.69   84.68   84.66   84.66    84.7    85.4   85.29   86.46
   87.02    86.6   85.72   85.94   86.16   85.15   85.73   85.03   84.47   83.84
   83.39   83.42   83.44   83.47   83.22   83.43   82.89   82.15   82.34   83.26
    82.1   81.17   81.35   81.67    83.2   83.34   83.34    83.4   84.25   85.84
   87.12   86.79   85.24   83.29    81.7   78.39   84.99   85.06   86.76   87.38
   87.12   86.29   86.29   86.19   85.64    85.4      86   85.74   85.42   85.42
   84.94   84.81   84.57   84.42   84.66   84.05   84.69   85.39   85.28   86.46
  1214.8  1234.8  1304.8  1324.8  1374.8  1424.8  1484.8  1768.9  2013.9  2287.5
  2307.5  2557.9  2742.9  3037.5  3057.5    3066    3436    3456    3776  3927.4
  4457.4  4477.4  4522.4  4552.4 4572.31 4670.09  4670.2  4726.3  4770.5 4852.97
 4903.34 4917.16  4921.7  4927.4 4932.05  4941.1 4941.19 5042.46 5044.02 5054.55
 5096.22  5156.2 5156.31 5162.08 5162.34 5199.75 5199.93 5253.52  5291.5  5291.7
  5348.4  5363.4  5391.5  5441.5  5541.5  5571.5  5611.5  6051.5  6301.5  6351.5
   87.02    86.6   86.09   86.07   86.17   85.98   85.93   85.68   85.33   84.61
   84.56   84.02   84.17    84.1   84.08   84.07   83.81    83.8   83.55   83.43
   83.11    83.1   83.15   83.26   83.33   83.67   85.67   86.26   86.72   87.83
   88.51    88.7   88.76    88.6   88.61   88.62   88.62   88.74   88.75    88.6
   88.26   87.75    86.3    86.2   85.69   85.41   86.01   85.75   85.74   85.43
   85.07   84.82   84.69   84.68   84.66   84.66    84.7    85.4   85.29   86.46
   86.86   86.44   85.56   85.78      86   84.99   85.57   84.87   84.31   83.68
   83.23   83.26   83.28   83.31   83.06   83.27   82.73   81.99   82.18    83.1
   81.94   81.01   81.19   81.51   83.04   83.18   83.18   83.24   84.09   85.68
   86.96   86.63   85.08   83.13   81.54   78.23   84.83    84.9    86.6   87.22
   86.96   86.13   86.13   86.03   85.48   85.24   85.84   85.58   85.26   85.26
   84.78   84.65   84.41   84.26    84.5   83.89   84.53   85.23   85.12    86.3
Pier Skew, UpSta & Num, DnSta & Num=  ,4968.2, 2 ,4968.2, 2 , 0 , 0 , 0 ,,
       2       2
   72.11   86.02
       2       2
   71.95   85.86
Pier Skew, UpSta & Num, DnSta & Num=  ,5004.4, 2 ,5004.4, 2 , 0 , 0 , 0 ,,
       2       2
   69.75   86.07
       2       2
   69.59   85.91
Abutment Skew #Up #Dn= , 2 , 2
 5040.98 5042.55
   83.45   85.11
 5040.98 5042.55
   83.29   84.95
BR Coef= 1 , 1 , 0 ,1.25, 0 ,,,.8,0,2,0,
WSPro=,,,, 1 ,,,, 0 ,,,, 0 ,,,,-1 ,-1 ,-1 , 0 , 0 , 0 , 0 , 0
BR U #Sta/Elev= 108
  1214.8   87.02  1234.8    86.6  1293.9   85.86  1304.8   85.72  1324.8   85.94
  1374.8   86.16  1424.8   85.15  1484.8   85.73  1564.8    85.5  1768.9   85.03
  1988.9   84.53  2013.9   84.47  2128.9    84.2  2287.5   83.84  2307.5   83.39
  2397.9    83.4  2537.9   83.42  2557.9   83.42  2612.9   83.42  2742.9   83.44
  2952.9   83.46  3037.5   83.47  3057.5   83.22    3066   83.43  3303.9   83.08
  3342.9   83.03    3436   82.89    3456   82.15  3547.9    82.2  3567.9   82.22
    3776   82.34  3927.4   83.26  4322.9   82.39  4457.4    82.1  4477.4   81.17
  4507.9   81.29  4522.4   81.35  4552.4   81.67 4572.31    83.2  4639.3   83.31
 4670.09   83.34  4670.2   83.34 4670.31   83.34  4726.3    83.4  4770.5   84.25
 4852.97   85.84 4903.34   87.12 4917.16   86.79  4921.7   85.24  4927.4   83.29
 4932.05    81.7  4941.1   78.39 4941.19   78.35 4941.62    78.2 4955.02   73.29
 4968.16    73.1 4979.38   73.65 4989.21   72.86 4994.35   71.44 4996.96   70.96
 5000.78   70.51 5003.65   70.78 5004.35   71.02 5005.57   71.65 5007.74   73.86
 5016.36   74.74 5039.24   81.56 5040.98   83.45 5042.35   84.94 5042.46   85.06
 5044.02   86.76  5047.3   86.95  5053.6   87.32 5054.55   87.38 5096.22   87.12
  5130.5   86.66 5149.29   86.41 5156.09   86.29  5156.2   86.29 5156.31   86.29
 5162.08   86.19 5162.34   85.64 5198.97   85.43 5199.75    85.4 5199.93      86
  5230.6   85.85 5253.52   85.74  5291.5   85.42  5291.7   85.42  5348.4   84.94
  5363.4   84.81  5391.5   84.57  5441.5   84.42  5541.5   84.66  5571.5   84.05
  5611.5   84.69  5721.5    84.8  5793.4   84.91  5843.4   84.99  5863.4   85.02
  5933.4   85.13  5943.4   85.15  5981.5   85.21  6051.5   85.39  6203.9   85.32
  6301.5   85.28  6348.4   86.39  6351.5   86.46
BR U #Mann= 5
  1214.8     .12  3303.9      .1 4903.34    .035 5044.02      .1  6203.9     .14
BR U Banks=4903.34,5044.02
BR D #Sta/Elev= 108
  1214.8   86.86  1234.8   86.44  1293.9    85.7  1304.8   85.56  1324.8   85.78
  1374.8      86  1424.8   84.99  1484.8   85.57  1564.8   85.34  1768.9   84.87
  1988.9   84.37  2013.9   84.31  2128.9   84.04  2287.5   83.68  2307.5   83.23
  2397.9   83.24  2537.9   83.26  2557.9   83.26  2612.9   83.26  2742.9   83.28
  2952.9    83.3  3037.5   83.31  3057.5   83.06    3066   83.27  3303.9   82.92
  3342.9   82.87    3436   82.73    3456   81.99  3547.9   82.04  3567.9   82.06
    3776   82.18  3927.4    83.1  4322.9   82.23  4457.4   81.94  4477.4   81.01
  4507.9   81.13  4522.4   81.19  4552.4   81.51 4572.31   83.04  4639.3   83.15
 4670.09   83.18  4670.2   83.18 4670.31   83.18  4726.3   83.24  4770.5   84.09
 4852.97   85.68 4903.34   86.96 4917.16   86.63  4921.7   85.08  4927.4   83.13
 4932.05   81.54  4941.1   78.23 4941.19   78.19 4941.62   78.04 4955.02   73.13
 4968.16   72.94 4979.38   73.49 4989.21    72.7 4994.35   71.28 4996.96    70.8
 5000.78   70.35 5003.65   70.62 5004.35   70.86 5005.57   71.49 5007.74    73.7
 5016.36   74.58 5039.24    81.4 5040.98   83.29 5042.35   84.78 5042.46    84.9
 5044.02    86.6  5047.3   86.79  5053.6   87.16 5054.55   87.22 5096.22   86.96
  5130.5    86.5 5149.29   86.25 5156.09   86.13  5156.2   86.13 5156.31   86.13
 5162.08   86.03 5162.34   85.48 5198.97   85.27 5199.75   85.24 5199.93   85.84
  5230.6   85.69 5253.52   85.58  5291.5   85.26  5291.7   85.26  5348.4   84.78
  5363.4   84.65  5391.5   84.41  5441.5   84.26  5541.5    84.5  5571.5   83.89
  5611.5   84.53  5721.5   84.64  5793.4   84.75  5843.4   84.83  5863.4   84.86
  5933.4   84.97  5943.4   84.99  5981.5   85.05  6051.5   85.23  6203.9   85.16
  6301.5   85.12  6348.4   86.23  6351.5    86.3
BR D #Mann= 5
  1214.8     .12  3303.9      .1 4903.34    .035 5044.02      .1  6203.9     .14
BR D Banks=4903.34,5044.02
BC Design=,, 0 ,, 0 ,,,,,,

Type RM Length L Ch R = 1 ,86091.4 ,531.7,531.7,531.7
BEGIN DESCRIPTION:
Downstream Section of Bridge/Culvert/Weir
END DESCRIPTION:
XS GIS Cut Line= 6
      3097271.67     13894832.29      3099278.36     13892028.92
      3099453.49     13891798.23      3099478.48     13891757.24
      3099547.26     13891662.99      3100269.43     13890661.36
#Sta/Elev= 30
  1214.8   86.85  1424.8   84.98  1484.8   85.56  2307.5   83.22  3303.9   82.91
    3436   82.72    3456   81.98  3927.4   83.09  4457.4   81.93  4477.4      81
  4552.4    81.5 4572.31   83.03  4726.3   83.23 4903.34   86.95 4917.16   86.62
 4955.02   73.12 4979.38   73.48 4989.21   72.69 5000.78   70.34 5004.35   70.85
 5007.74   73.69 5016.36   74.57 5039.24   81.39 5044.02   86.59 5054.55   87.21
 5162.34   85.47  5571.5   83.88  6203.9   85.15  6301.5   85.11  6351.5   86.29
#Mann= 5 , 1 , 0
  1214.8     .12       0  3303.9      .1       0 4903.34    .035       0
 5044.02      .1       0  6203.9     .14       0
#XS Ineff= 2 , 0
       0    4300      86 5042.13       0    84.7
Permanent Ineff=
       F       F
Bank Sta=4903.34,5044.02
XS Rating Curve= 0
Exp/Cntr=.5,.3

Type RM Length L Ch R = 1 ,85559.7 ,1055.3,965.5,548.1
BEGIN DESCRIPTION:
Cross Section 85559.7
END DESCRIPTION:
XS GIS Cut Line= 6
      3097534.08     13894925.98      3098370.75      13893888.5
      3098961.01     13893098.59      3100063.42     13891892.02
      3100844.65     13890294.84      3100917.08     13889538.36
#Sta/Elev= 30
  1277.3    86.8  1777.3    84.7  2080.1   84.76  2267.3    84.8  2457.3    83.8
  2610.1    84.5  2890.1    83.4  3596.2    84.5  4756.2    80.3  4918.2    82.4
  4950.2   81.09    4964   81.34  4982.7   74.51  4993.1   72.39  4995.8   70.19
  4999.4    69.6  5014.9   73.12  5069.1   83.14  5081.2   83.32  5096.7   82.08
  5231.3    84.2  5311.3    83.5  5771.3    83.3  5851.3    82.7  6191.3    84.9
  6511.3      84  6711.3    85.8  6777.1   85.51  6961.3    84.7  7769.3    85.9
#Mann= 5 , 1 , 0
  1277.3     .12       0  2080.1     .08       0    4964    .035       0
  5069.1     .08       0  6777.1      .2       0
Bank Sta=4964,5069.1
XS Rating Curve= 0
Exp/Cntr=.3,.1

Type RM Length L Ch R = 1 ,84594.2 ,895.4,908.6,1007.9
BEGIN DESCRIPTION:
Cross Section 84594.2
END DESCRIPTION:
XS GIS Cut Line= 6
      3099516.56      13895346.8      3099768.29     13894279.12
      3100150.22     13893680.18       3100775.2     13892273.96
      3100809.93     13891675.02      3100983.53     13889374.73
#Sta/Elev= 30
  1789.2    86.2  2309.2    84.1  2849.2    84.6  3316.2      84  3766.5    81.5
  3856.5    82.3  4346.5    80.6  4586.5    82.1  4626.5    81.2  4948.1   80.82
  4964.9   74.65  4978.7   71.65  4989.8   72.97  4996.4   69.27  4999.2   69.23
  5004.1   69.39  5008.9   73.66  5025.7   79.98  5135.4    81.1  5195.4    80.8
  5275.4    82.1  5315.4    80.7  5735.3      84  6085.3    82.7  6354.8    84.7
  6574.8    85.3  6654.8    84.6    6906   84.91  7564.8    84.3  8042.2    86.2
#Mann= 5 , 1 , 0
  1789.2      .2       0  1789.2     .08       0  4948.1    .035       0
  5025.7     .08       0    6906      .2       0
Bank Sta=4948.1,5025.7
XS Rating Curve= 0
Exp/Cntr=.3,.1

Type RM Length L Ch R = 1 ,83685.6 ,222.9,234.9,249
BEGIN DESCRIPTION:
Cross Section 83685.6-Interpolated
END DESCRIPTION:
XS GIS Cut Line= 5
      3101289.45     13894327.01      3101459.21     13893807.12
      3101515.48     13893000.55      3101515.48      13892494.1
      3101462.33     13890394.86
#Sta/Elev= 30
    3471    83.1    3511    81.5  4127.9    81.5  4137.9      80  4147.9    79.7
  4157.9    80.6  4237.9    81.2  4277.9    80.2  4397.9    79.6  4727.9    79.2
  4826.4    79.9  4965.8   79.08  4987.7   71.89  4989.8   69.82  5006.5   68.94
  5062.9   79.41  5166.4    80.1  5216.4    81.9  5256.4    81.2  5688.3   81.21
  5852.8    82.5  5872.8    81.8  6052.8    82.5  6371.5    81.5  6472.8    81.1
  6572.8    83.6  7172.8    83.4  7232.8    81.7  7252.8      83  7432.8    85.3
#Mann= 5 , 1 , 0
    3471     .08       0  4965.8    .035       0  5062.9     .08       0
  5688.3     .14       0  6371.5      .1       0
#XS Ineff= 2 , 0
       0                    7171       0    83.4
Permanent Ineff=
       F       F
Bank Sta=4965.8,5062.9
XS Rating Curve= 0
Exp/Cntr=.5,.3

Type RM Length L Ch R = 1 ,83450.7 ,52,52,52
BEGIN DESCRIPTION:
Upstream Section of Bridge/Culvert/Weir
END DESCRIPTION:
XS GIS Cut Line= 6
      3101631.12     13894884.33      3101662.72      13894231.7
      3101719.67     13892921.29      3101726.66     13892702.05
      3101762.83     13892204.75      3101782.08     13890251.88
#Sta/Elev= 30
    3062      83  3615.8    82.1    4002   80.77  4094.9   79.23  4434.9    78.4
  4514.9   79.53    4730   78.14  4965.1   78.76  4987.7   71.81  4989.8   69.74
  5006.5   68.86    5014   71.58  5062.9   79.33    5796   81.34    6028   82.75
    6108   85.52  6153.4   83.65    6168   82.76    6258   83.81    6438   83.27
    6508   81.19    6578   81.06    6758   82.74    7128    83.1    7198   80.59
    7248   83.49    7438   83.65    7518   80.78    7588   83.82    7698    84.7
#Mann= 6 , 1 , 0
    3062      .2       0  3615.8     .08       0  4965.1    .035       0
  5062.9     .08       0    5796     .14       0  6153.4     .99       0
#XS Ineff= 2 , 0
       0  4958.4    79.6    6115       0    85.6
Permanent Ineff=
       F       F
Bank Sta=4965.1,5062.9
XS Rating Curve= 0
Exp/Cntr=.5,.3

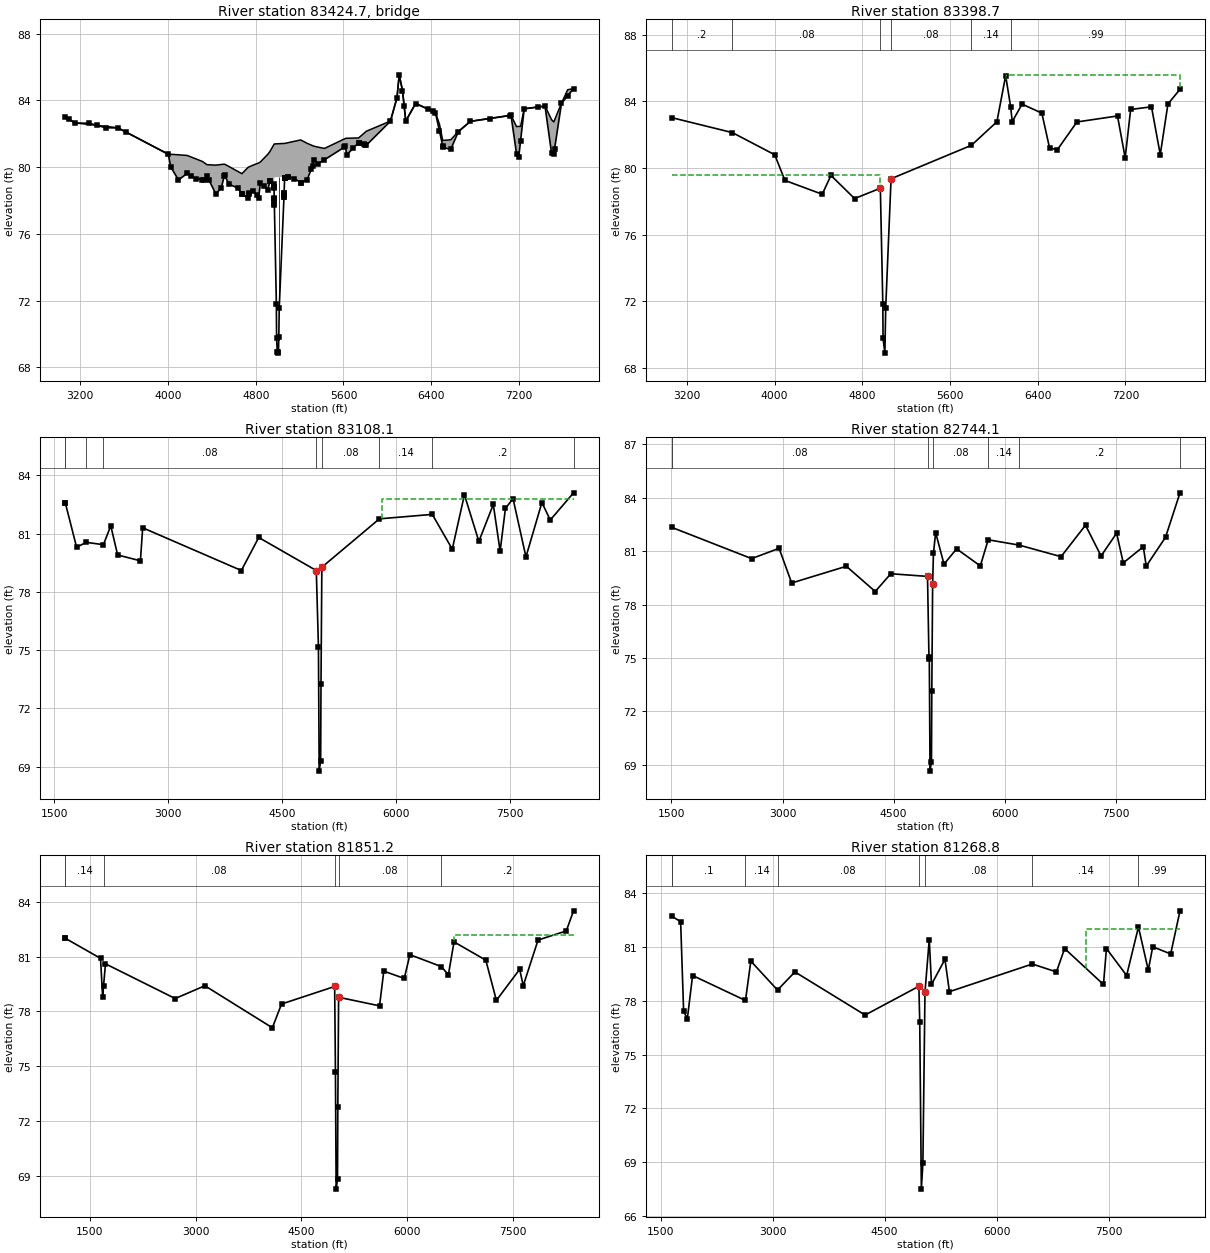
Type RM Length L Ch R = 3 ,83424.7 ,,,
BEGIN DESCRIPTION:
DEER TRAIL DRIVE
Structure ID: P18-43
END DESCRIPTION:
Bridge Culvert--1,0,-1,-1, 0
Deck Dist Width WeirC Skew NumUp NumDn MinLoCord MaxHiCord MaxSubmerge Is_Ogee
10,32,2.6,0, 60, 60, , , .95, 0, 1,1,,
    3062    3152    3542    4002  4024.9  4094.9  4174.9  4313.5  4354.9  4434.9
  4484.9  4514.9  4554.9  4673.5    4730  4774.9  4826.4  4841.7    4911  4929.1
  4965.1  4965.8  4968.3 4968.41  4968.5 5058.19  5058.3  5062.9  5209.5  5267.9
    5328    5368  5426.4    5618    5628    5738    5808    6028    6088    6108
    6138    6168    6258    6438    6475    6505    6578    6648    6758    7128
    7178    7198    7215    7248    7438    7498    7518    7588    7645    7698
      83   82.65   82.36   80.78   80.77   80.74    80.7   80.34   80.15   80.12
   80.16   80.18   80.04   79.61   79.99   80.12   80.25   80.31   80.78   80.94
   81.35   81.36   81.39   81.39   81.39   81.42   81.42   81.42   81.63   81.43
   81.26    81.2   81.12   81.72   81.73   81.75   82.15   82.76   84.17   85.53
    84.6   82.77   83.82   83.28   82.58    81.6   81.64   82.14   82.75   83.11
   82.43   82.44   82.44    83.5   83.66   82.84   82.71   83.83   84.64    84.7
      83   82.64   82.35   80.77   80.01   79.23   79.63   79.25   79.47    78.4
   78.74   79.53   78.98   78.42   78.14    78.6   78.18   79.03   78.66   79.18
   78.76      79   78.15   78.11   79.39   79.42   78.43   79.33   79.08   79.24
   80.41    80.2   80.44   81.24   80.73   81.47   81.31   82.75   84.16   85.52
   84.59   82.76   83.81   83.27   82.17   81.28   81.06   82.13   82.74    83.1
   80.81   80.59   81.58   83.49   83.65   80.82   80.78   83.82   84.28    84.7
    3062    3152    3542    4002  4024.9  4094.9  4174.9  4313.5  4354.9  4434.9
  4484.9  4514.9  4554.9  4673.5    4730  4774.9  4826.4  4841.7    4911  4929.1
  4965.1  4965.8  4968.3 4968.41  4968.5 5058.19  5058.3  5062.9  5209.5  5267.9
    5328    5368  5426.4    5618    5628    5738    5808    6028    6088    6108
    6138    6168    6258    6438    6475    6505    6578    6648    6758    7128
    7178    7198    7215    7248    7438    7498    7518    7588    7645    7698
   83.03   82.67   82.38    80.8   80.77   80.74    80.7   80.34   80.15   80.12
   80.16   80.18   80.04   79.61   79.99   80.12   80.25   80.31   80.78   80.94
   81.35   81.36   81.39   81.39   81.39   81.42   81.42   81.42   81.63   81.43
   81.26    81.2   81.12   81.72   81.73   81.75   82.15   82.78   84.19   85.55
   84.62   82.79   83.84    83.3   82.58    81.6   81.64   82.16   82.77   83.13
   82.43   82.44   82.44   83.52   83.68   82.84   82.71   83.85   84.64   84.73
   83.03   82.67   82.38    80.8   80.04   79.26   79.66   79.28    79.5   78.43
   78.77   79.56   79.01   78.45   78.17   78.63   78.21   79.06   78.69   79.21
   78.79   79.03   78.18   78.14   79.42   79.45   78.46   79.36   79.11   79.27
   80.44   80.23   80.47   81.27   80.76    81.5   81.34   82.78   84.19   85.55
   84.62   82.79   83.84    83.3    82.2   81.31   81.09   82.16   82.77   83.13
   80.84   80.62   81.61   83.52   83.68   80.85   80.81   83.85   84.31   84.73
Pier Skew, UpSta & Num, DnSta & Num=  ,5014, 2 ,5014, 2 , 0 , 0 , 0 ,,
     1.5     1.5
   70.24   80.41
     1.5     1.5
   70.27   80.44
Abutment Skew #Up #Dn= , 2 , 2
  4968.3  4969.5
   79.39   77.74
  4968.3  4969.5
   79.42   77.77
Abutment Skew #Up #Dn= , 2 , 2
  5057.3 5058.39
   78.24   79.42
  5057.3 5058.39
   78.27   79.45
BR Coef= 1 , 1 , 0 ,1.25, 0 ,,,.8,0,2,0,
WSPro=,,,, 1 ,,,, 0 ,,,, 0 ,,,,-1 ,-1 ,-1 , 0 , 0 , 0 , 0 , 0
BR U #Sta/Elev= 114
    3062      83  3093.1   82.88    3152   82.64    3282   82.63  3353.1    82.5
    3432   82.36    3542   82.35  3615.8    82.1    4002   80.77  4024.9   80.01
  4094.9   79.23  4174.9   79.63  4213.5   79.48  4254.9   79.32  4313.5   79.25
  4324.9   79.24  4354.9   79.47  4373.5   79.22  4434.9    78.4  4484.9   78.74
  4513.5   79.49  4514.9   79.53  4554.9   78.98  4634.9   78.75  4673.5   78.42
  4674.9   78.41    4730   78.14  4740.1   78.42    4741   78.44  4774.9    78.6
  4807.8   78.33  4826.4   78.18  4841.7   79.03    4874   78.86    4911   78.66
  4929.1   79.18    4932   79.15 4962.39   78.79  4962.5   78.79 4962.61   78.79
  4965.1   78.76  4965.8      79  4968.3   78.15 4968.41   78.11  4968.5   78.08
  4969.4   77.77  4969.5   77.74  4987.7   71.81  4989.8   69.74  4996.5    68.9
  5002.1   68.91  5006.5   68.86  5010.1   69.83    5014   71.58  5057.2   78.22
  5057.3   78.24 5058.19   78.41  5058.3   78.43  5058.4   78.45  5062.9   79.33
 5064.09   79.33  5064.2   79.33 5064.31   79.33  5092.5   79.42  5092.6   79.42
  5150.1   79.32  5209.5   79.08  5211.2   79.08  5267.9   79.24  5306.4   79.87
    5318   80.06    5328   80.41    5368    80.2  5426.4   80.44  5606.4   81.19
    5618   81.24    5628   80.73  5686.4   81.12    5738   81.47    5745   81.45
    5785   81.36    5796   81.34    5808   81.31    6028   82.75    6088   84.16
    6108   85.52    6138   84.59  6153.4   83.65    6168   82.76    6258   83.81
    6375   83.46    6415   83.34    6438   83.27    6475   82.17    6505   81.28
    6508   81.19    6578   81.06    6648   82.13    6758   82.74    6935   82.91
    7115   83.09    7128    83.1    7178   80.81    7198   80.59    7215   81.58
    7248   83.49    7375    83.6    7438   83.65    7498   80.82    7518   80.78
    7525   81.08    7588   83.82    7645   84.28    7698    84.7
BR U #Mann= 6
    3062      .2  3615.8     .08  4965.1    .035  5062.9     .08    5796     .14
  6153.4     .99
BR U Banks=4965.1,5062.9
BR D #Sta/Elev= 114
    3062   83.03  3093.1   82.91    3152   82.67    3282   82.66  3353.1   82.53
    3432   82.39    3542   82.38  3615.8   82.13    4002    80.8  4024.9   80.04
  4094.9   79.26  4174.9   79.66  4213.5   79.51  4254.9   79.35  4313.5   79.28
  4324.9   79.27  4354.9    79.5  4373.5   79.25  4434.9   78.43  4484.9   78.77
  4513.5   79.52  4514.9   79.56  4554.9   79.01  4634.9   78.78  4673.5   78.45
  4674.9   78.44    4730   78.17  4740.1   78.45    4741   78.47  4774.9   78.63
  4807.8   78.36  4826.4   78.21  4841.7   79.06    4874   78.89    4911   78.69
  4929.1   79.21    4932   79.18 4962.39   78.82  4962.5   78.82 4962.61   78.82
  4965.1   78.79  4965.8   79.03  4968.3   78.18 4968.41   78.14  4968.5   78.11
  4969.4    77.8  4969.5   77.77  4987.7   71.84  4989.8   69.77  4996.5   68.93
  5002.1   68.94  5006.5   68.89  5010.1   69.86    5014   71.61  5057.2   78.25
  5057.3   78.27 5058.19   78.44  5058.3   78.46  5058.4   78.48  5062.9   79.36
 5064.09   79.36  5064.2   79.36 5064.31   79.36  5092.5   79.45  5092.6   79.45
  5150.1   79.35  5209.5   79.11  5211.2   79.11  5267.9   79.27  5306.4    79.9
    5318   80.09    5328   80.44    5368   80.23  5426.4   80.47  5606.4   81.22
    5618   81.27    5628   80.76  5686.4   81.15    5738    81.5    5745   81.48
    5785   81.39    5796   81.37    5808   81.34    6028   82.78    6088   84.19
    6108   85.55    6138   84.62  6153.4   83.68    6168   82.79    6258   83.84
    6375   83.49    6415   83.37    6438    83.3    6475    82.2    6505   81.31
    6508   81.22    6578   81.09    6648   82.16    6758   82.77    6935   82.94
    7115   83.12    7128   83.13    7178   80.84    7198   80.62    7215   81.61
    7248   83.52    7375   83.63    7438   83.68    7498   80.85    7518   80.81
    7525   81.11    7588   83.85    7645   84.31    7698   84.73
BR D #Mann= 6
    3062      .2  3615.8     .08  4965.1    .035  5062.9     .08    5796     .14
  6153.4     .99
BR D Banks=4965.1,5062.9
BC Design=,, 0 ,, 0 ,,,,,,

Type RM Length L Ch R = 1 ,83398.7 ,290.6,290.6,290.6
BEGIN DESCRIPTION:
Downstream Section of Bridge/Culvert/Weir
END DESCRIPTION:
XS GIS Cut Line= 6
      3101682.03      13894894.9      3101713.64     13894242.28
      3101770.59     13892931.87      3101777.58     13892712.63
      3101813.75     13892215.33      3101832.99     13890262.45
#Sta/Elev= 30
    3062   83.03  3615.8   82.13    4002    80.8  4094.9   79.26  4434.9   78.43
  4514.9   79.56    4730   78.17  4965.1   78.79  4987.7   71.84  4989.8   69.77
  5006.5   68.89    5014   71.61  5062.9   79.36    5796   81.37    6028   82.78
    6108   85.55  6153.4   83.68    6168   82.79    6258   83.84    6438    83.3
    6508   81.22    6578   81.09    6758   82.77    7128   83.13    7198   80.62
    7248   83.52    7438   83.68    7518   80.81    7588   83.85    7698   84.73
#Mann= 6 , 1 , 0
    3062      .2       0  3615.8     .08       0  4965.1    .035       0
  5062.9     .08       0    5796     .14       0  6153.4     .99       0
#XS Ineff= 2 , 0
       0  4958.4    79.6    6115       0    85.6
Permanent Ineff=
       F       F
Bank Sta=4965.1,5062.9
XS Rating Curve= 0
Exp/Cntr=.5,.3

Type RM Length L Ch R = 1 ,83108.1 ,452.6,364,339.9
BEGIN DESCRIPTION:
Cross Section 83108.1-Interpolated
END DESCRIPTION:
XS GIS Cut Line= 6
      3101459.21     13896245.58      3101871.87     13894669.96
      3102040.69     13893807.12      3102040.69     13893169.37
       3102078.2     13892700.44      3102115.72     13889624.22
#Sta/Elev= 30
    1647    82.6  1647.1    82.6  1797.1    80.3  1924.7   80.55    2150   80.43
  2247.1    81.4  2337.1    79.9  2637.1    79.6  2667.1    81.3  3965.9    79.1
  4195.1    80.8  4952.8    79.1    4981   75.18  4990.9   68.77  5010.3   69.31
  5014.8   73.28    5026   79.27  5783.5   81.76  6479.9   81.99  6743.2    80.2
  6903.2      83  7093.2    80.6  7283.2    82.5  7373.2    80.1  7443.2    82.3
  7543.2    82.8  7713.2    79.8  7923.2    82.6  8033.2    81.7  8339.7    83.1
#Mann= 9 , 1 , 0
    1647      .2       0  1647.1      .1       0  1924.7     .14       0
    2150     .08       0  4952.8    .035       0    5026     .08       0
  5783.5     .14       0  6479.9      .2       0  8339.7      .2       0
#XS Ineff= 2 , 0
       0                  5813.2       0    82.8
Permanent Ineff=
       F       F
Bank Sta=4952.8,5026
XS Rating Curve= 0
Exp/Cntr=.3,.1

Type RM Length L Ch R = 1 ,82744.1 ,886.1,892.9,900.4
BEGIN DESCRIPTION:
Cross Section 82744.1-Interpolated
END DESCRIPTION:
XS GIS Cut Line= 5
      3101595.05     13896293.11      3102388.22     13894668.38
       3102426.6     13893133.21      3102413.81     13892800.59
      3102439.39      13889615.1
#Sta/Elev= 30
  1503.2   82.34  2583.2   80.58  2953.2   81.16  3123.2   79.21  3861.2   80.15
  4251.2   78.73  4461.2   79.73  4956.9   79.58  4976.9   74.92    4981   75.04
  4990.9   68.63  5010.3   69.17  5014.8   73.14    5026   79.13  5036.9   80.89
  5066.9   82.04  5179.7   80.27  5349.7   81.13  5669.7   80.17  5776.1   81.64
  6193.8   81.34  6759.7   80.69  7089.7   82.46  7299.7   80.73  7509.7   82.01
  7599.7   80.34  7869.7   81.25  7909.7   80.16  8169.7   81.78  8365.3   84.28
#Mann= 7 , 1 , 0
  1503.2      .2       0  1503.2     .08       0  4956.9    .035       0
    5026     .08       0  5776.1     .14       0  6193.8      .2       0
  8365.3      .2       0
#XS Ineff= 2 , 0
       0                  7089.7       0   82.46
Permanent Ineff=
       F       F
Bank Sta=4956.9,5026
XS Rating Curve= 0
Exp/Cntr=.3,.1

Type RM Length L Ch R = 1 ,81851.2 ,560.5,582.4,722.9
BEGIN DESCRIPTION:
Cross Section 81851.2
END DESCRIPTION:
XS GIS Cut Line= 6
      3101987.84     13896515.82      3102550.31     13895691.38
      3103174.43     13894643.48       3103282.3     13893996.25
       3103282.3      13891653.9      3102881.63     13889712.21
#Sta/Elev= 30
  1153.5      82  1153.6      82  1653.6    80.9  1683.6    78.8  1697.2   79.41
  1723.6    80.6  2711.6    78.7  3131.6    79.4  4087.5    77.1  4217.5    78.4
    4970   79.36    4981   74.68  4990.9   68.27  5010.3   68.81  5014.8   72.78
    5026   78.77  5605.7    78.3  5665.7    80.2  5955.7    79.8  6035.7    81.1
  6479.8   80.45  6580.7      80  6660.7    81.8  7110.7    80.8  7260.7    78.6
  7590.7    80.3  7640.7    79.4  7850.7    81.9  8250.7    82.4  8353.3    83.5
#Mann= 6 , 1 , 0
  1153.5      .2       0  1153.6     .14       0  1697.2     .08       0
    4970    .035       0    5026     .08       0  6479.8      .2       0
#XS Ineff= 2 , 0
       0                  6660.7       0    82.2
Permanent Ineff=
       F       F
Bank Sta=4970,5026
XS Rating Curve= 0
Exp/Cntr=.3,.1

Type RM Length L Ch R = 1 ,81268.8 ,243,245.5,246.8
BEGIN DESCRIPTION:
Cross Section 81268.8-Interpolated
END DESCRIPTION:
XS GIS Cut Line= 5
      3103785.13     13896395.64      3103878.91     13893338.19
      3103916.43     13892606.65       3103710.1     13891875.11
      3102941.04     13889755.52
#Sta/Elev= 30
  1649.2    82.7  1769.2    82.4  1809.2    77.4  1859.2      77  1929.2    79.4
  2637.4   78.01  2709.2    80.2  3066.3   78.59  3299.2    79.6  4239.2    77.2
  4959.2    78.8  4970.6   76.83  4992.2   67.51  5012.9   68.95    5041   78.48
  5098.1    81.4  5128.1    78.9  5308.1    80.3  5368.1    78.5  6478.2   80.04
  6800.7    79.6  6910.7    80.9  7430.7    78.9  7470.7    80.9  7740.7    79.4
  7899.2    82.1  8030.7    79.7  8090.7      81  8330.7    80.6  8455.5      83
#Mann= 8 , 1 , 0
  1649.2      .2       0  1649.2      .1       0  2637.4     .14       0
  3066.3     .08       0  4959.2    .035       0    5041     .08       0
  6478.2     .14       0  7899.2     .99       0
#XS Ineff= 2 , 0
       0                    7200       0      82
Permanent Ineff=
       F       F
Bank Sta=4959.2,5041
XS Rating Curve= 0
Exp/Cntr=.5,.3

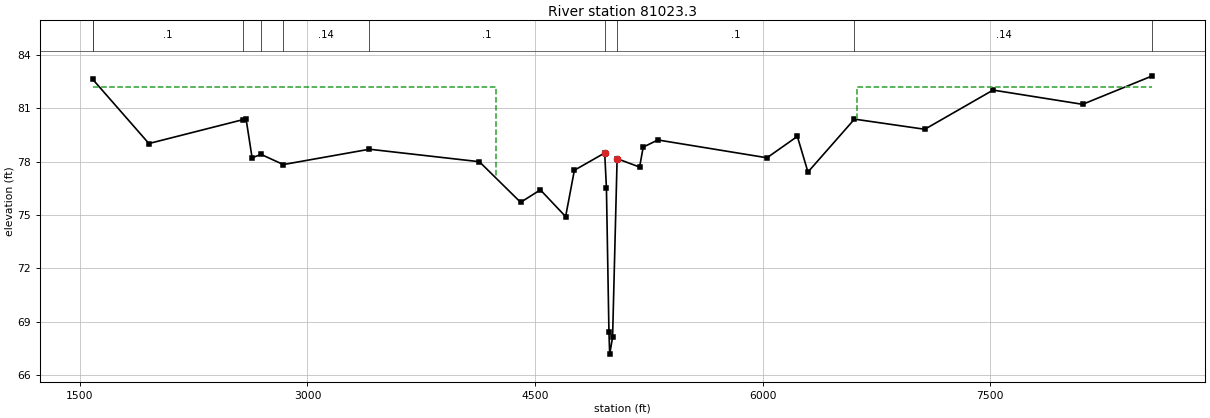
Type RM Length L Ch R = 1 ,81023.3 ,52,52,52
BEGIN DESCRIPTION:
Upstream Section of Bridge/Culvert/Weir
END DESCRIPTION:
XS GIS Cut Line= 6
      3103986.01     13896401.97      3104104.97     13893862.62
      3104110.81     13893389.01      3104142.93     13892775.07
      3104203.18     13891716.62      3103190.36     13889659.35
#Sta/Elev= 30
  1585.3   82.61  1955.3   79.01  2575.1   80.35  2595.3   80.41  2635.3   78.21
  2694.5    78.4  2840.9   77.83  3408.6   78.69  4133.1   77.99  4405.2   75.71
  4535.2   76.41  4701.7   74.91  4759.4   77.51  4959.2   78.48  4970.6   76.51
  4987.1   68.45  4992.2   67.19  5011.2   68.14    5041   78.16  5189.2   77.69
    5213   78.81  5309.8   79.21  6028.8   78.21  6228.8   79.41  6298.8   77.41
  6605.3   80.38  7068.8   79.81  7518.8   82.01  8108.8   81.21  8569.1   82.81
#Mann= 10 , 1 , 0
  1585.3      .2       0  1585.3      .1       0  2575.1     .14       0
  2694.5      .1       0  2840.9     .14       0  3408.6      .1       0
  4959.2    .035       0    5041      .1       0  6605.3     .14       0
  8569.1      .2       0
#XS Ineff= 2 , 0
       0    4245    82.2    6621       0    82.2
Permanent Ineff=
       F       F
Bank Sta=4959.2,5041
XS Rating Curve= 0
Exp/Cntr=.5,.3