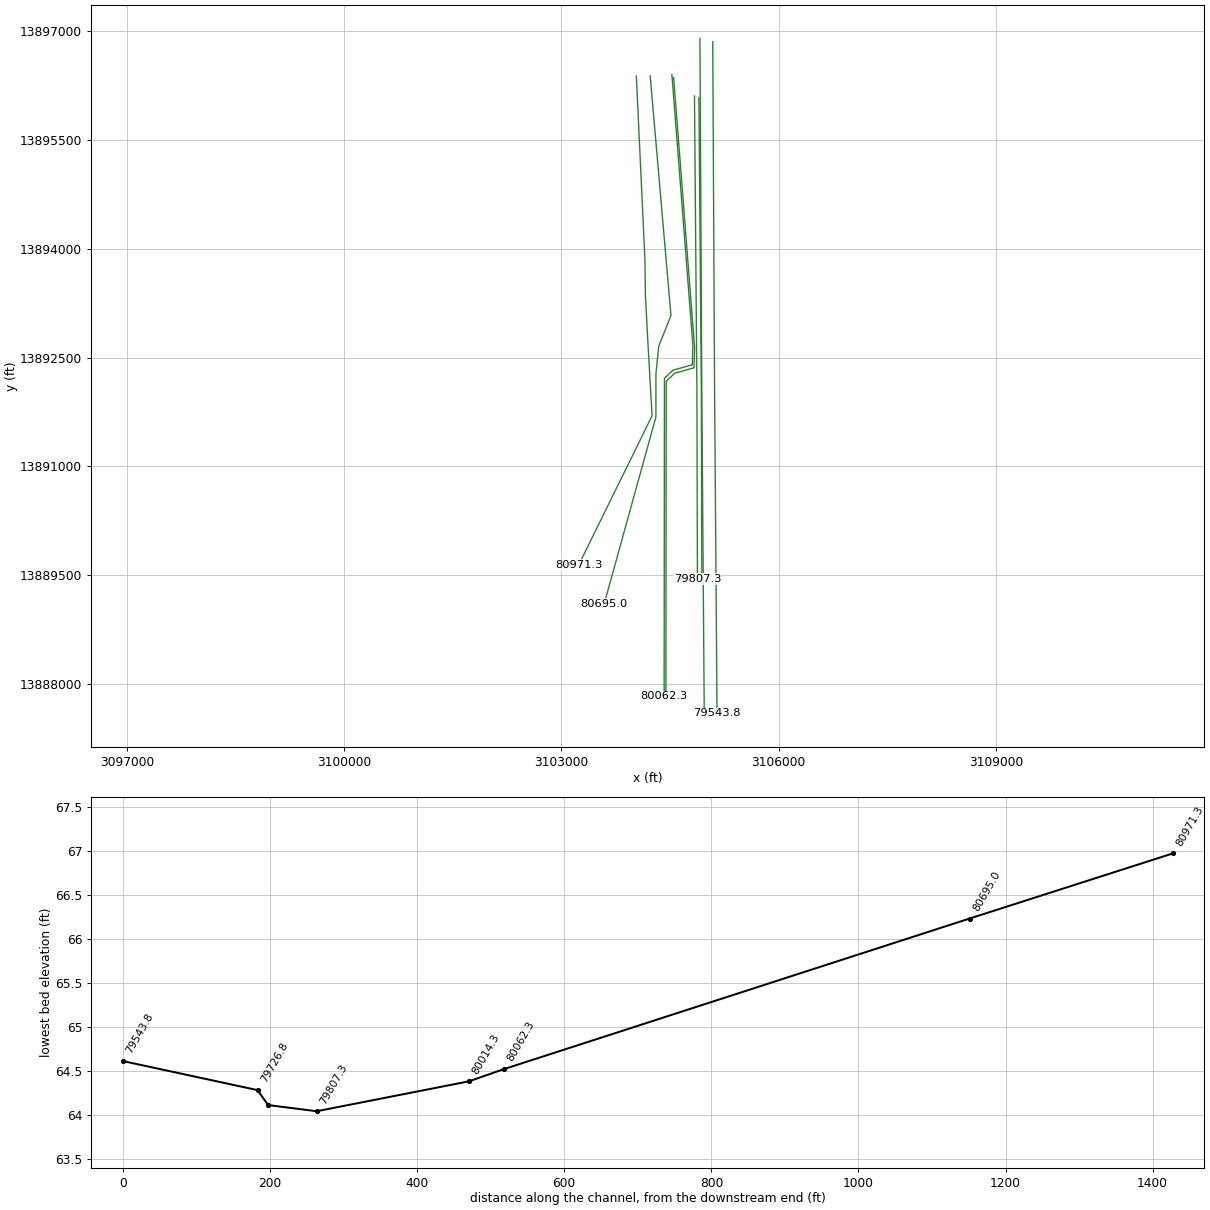
HEC-RAS study P118-00-00.PRJ: P118-00-00

--- P118-00-00.g01 (geometry) --- (continued)

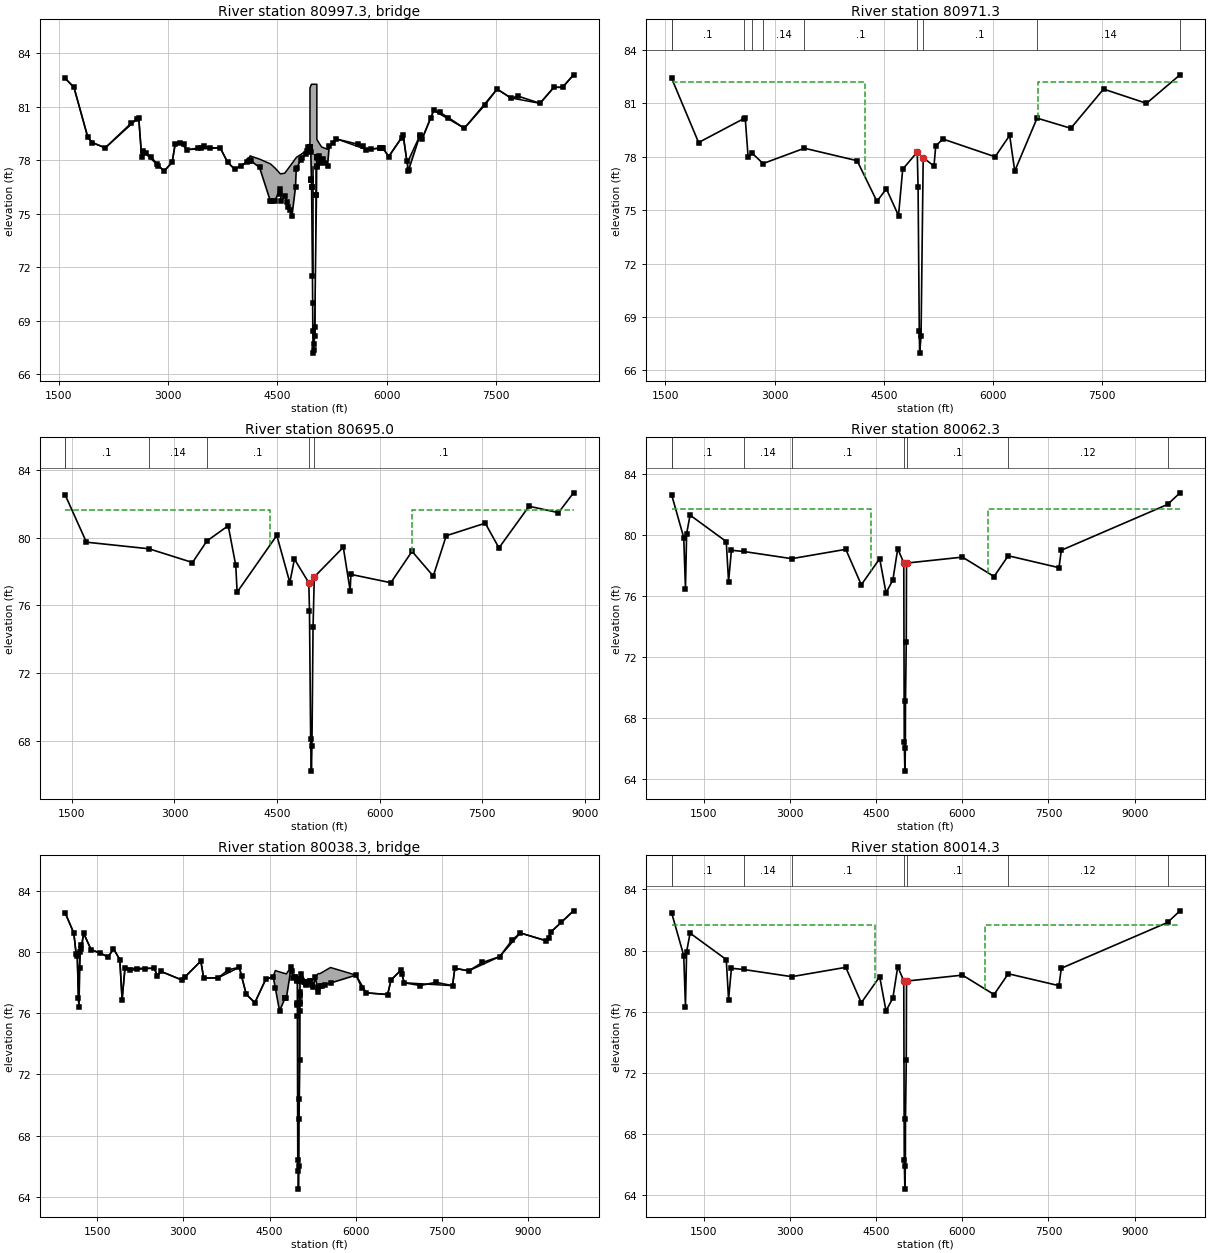
Type RM Length L Ch R = 3 ,80997.3 ,,,
BEGIN DESCRIPTION:
SONNY WOOD STREET
Structure ID: P18-41
END DESCRIPTION:
Bridge Culvert--1,0,-1,-1, 0
Deck Dist Width WeirC Skew NumUp NumDn MinLoCord MaxHiCord MaxSubmerge Is_Ogee
10,32,2.6,0, 60, 60, , , .95, 0, 1,1,,
  1585.3  1705.3  1895.3  1955.3  2135.3  2595.3  2635.3  2655.3  2945.3  3055.3
  3095.3  3165.3  3255.3  3715.3  3815.3  3915.3  4083.1  4125.2  4255.2  4405.2
  4465.2  4535.2  4543.1  4555.2  4601.7  4701.7  4749.5  4759.4  4906.9 4948.09
  4948.2  4959.2  4968.1 4968.21  4968.3  5040.1    5041  5042.7 5042.81  5082.7
  5108.5  5189.2    5213  5309.8  5719.8  5948.8  6028.8  6228.8  6278.1  6298.8
  6458.8  6488.8  6648.8  7068.8  7518.8  7708.8  8108.8  8298.8  8418.8  8569.1
    82.6    82.1    79.3      79    78.7    80.4    78.2    78.5    77.4    77.9
    78.9      79    78.6    78.7    77.9    77.5   77.91   78.25   78.07    77.8
   77.58   77.27   77.24   77.25   77.28   77.83    78.1   78.16   78.56   78.97
   82.07   82.18   82.27   82.27   82.27   82.27   82.27   82.27   79.17   78.91
   78.75   78.62   78.81   79.21   78.61   78.71   78.21   79.41      78   77.99
    79.4    79.2    80.8    79.8      82    81.5    81.2    82.1    82.1    82.8
    82.6    82.1    79.3      79    78.7    80.4    78.2    78.5    77.4    77.9
    78.9      79    78.6    78.7    77.9    77.5    77.9      78    77.6    75.7
    75.7    76.4   76.12    75.7      76    74.9   76.51    77.5   78.53   78.75
   78.75   78.47   76.93   76.91   77.67   77.67   78.15   78.16   78.16   77.87
   77.99   77.68    78.8    79.2    78.6    78.7    78.2    79.4   77.99    77.4
    79.4    79.2    80.8    79.8      82    81.5    81.2    82.1    82.1    82.8
  1585.3  1705.3  1895.3  1955.3  2135.3  2595.3  2635.3  2655.3  2945.3  3055.3
  3095.3  3165.3  3255.3  3715.3  3815.3  3915.3  4083.1  4125.2  4255.2  4405.2
  4465.2  4535.2  4543.1  4555.2  4601.7  4701.7  4749.5  4759.4  4906.9 4948.09
  4948.2  4959.2  4968.1 4968.21  4968.3  5040.1    5041  5042.7 5042.81  5082.7
  5108.5  5189.2    5213  5309.8  5719.8  5948.8  6028.8  6228.8  6278.1  6298.8
  6458.8  6488.8  6648.8  7068.8  7518.8  7708.8  8108.8  8298.8  8418.8  8569.1
    82.6    82.1    79.3      79    78.7    80.4    78.2    78.5    77.4    77.9
    78.9      79    78.6    78.7    77.9    77.5   77.91   78.25   78.07    77.8
   77.58   77.27   77.24   77.25   77.28   77.83    78.1   78.16   78.56   78.97
   82.07   82.18   82.27   82.27   82.27   82.27   82.27   82.27   79.17   78.91
   78.75   78.62   78.81   79.21   78.61   78.71   78.21   79.41      78   77.99
    79.4    79.2    80.8    79.8      82    81.5    81.2    82.1    82.1    82.8
   82.42   81.92   79.12   78.82   78.52   80.22   78.02   78.32   77.22   77.72
   78.72   78.82   78.42   78.52   77.72   77.32   77.72   77.82   77.42   75.52
   75.52   76.22   75.94   75.52   75.82   74.72   76.33   77.32   78.35   78.57
   78.57   78.29   76.75   76.73   77.49   77.49   77.97   77.98   77.98   77.69
   77.81    77.5   78.62   79.02   78.42   78.52   78.02   79.22   77.81   77.22
   79.22   79.02   80.62   79.62   81.82   81.32   81.02   81.92   81.92   82.62
Pier Skew, UpSta & Num, DnSta & Num=  ,4982.4, 2 ,4982.4, 2 , 0 , 0 , 0 ,,
     1.5     1.5
   70.09   78.67
     1.5     1.5
   69.91   78.49
Pier Skew, UpSta & Num, DnSta & Num=  ,5011.2, 2 ,5011.2, 2 , 0 , 0 , 0 ,,
     1.5     1.5
   67.08   78.67
     1.5     1.5
    66.9   78.49
Abutment Skew #Up #Dn= , 2 , 2
  4968.1  4970.6
   77.67    76.5
  4968.1  4970.6
   77.49   76.32
Abutment Skew #Up #Dn= , 2 , 2
  5037.1 5040.19
   76.08   77.67
  5037.1 5040.19
    75.9   77.49
BR Coef= 1 , 1 , 0 ,1.25, 0 ,,,.8,0,2,0,
WSPro=,,,, 1 ,,,, 0 ,,,, 0 ,,,,-1 ,-1 ,-1 , 0 , 0 , 0 , 0 , 0
BR U #Sta/Elev= 118
  1585.3    82.6  1705.3    82.1  1895.3    79.3  1955.3      79  2135.3    78.7
  2495.3    80.1  2575.1   80.34  2595.3    80.4  2635.3    78.2  2655.3    78.5
  2694.5   78.39  2765.3    78.2  2840.9   77.82  2865.3    77.7  2945.3    77.4
  3055.3    77.9  3095.3    78.9  3165.3      79  3215.3    78.9  3255.3    78.6
  3408.6   78.68  3455.3    78.7  3495.3    78.8  3575.3    78.7  3715.3    78.7
  3815.3    77.9  3915.3    77.5  4003.1   77.71  4083.1    77.9  4113.1   77.97
  4125.2      78  4133.1   77.98  4255.2    77.6  4405.2    75.7  4423.1    75.7
  4465.2    75.7  4535.2    76.4  4543.1   76.12  4555.2    75.7  4601.7      76
  4631.1   75.65  4651.7    75.4  4671.1   75.21  4701.7    74.9  4749.5   76.51
  4759.4    77.5  4766.7   77.56  4819.5   78.03    4845   78.15  4892.7   78.38
  4906.9   78.53    4925   78.73 4948.09   78.75  4948.2   78.75 4948.31   78.75
  4951.8   78.75  4959.2   78.47  4968.1   76.93 4968.21   76.91  4968.3    76.9
  4970.5   76.52  4970.6    76.5  4982.4   71.51  4985.1      70  4987.1   68.44
  4992.2   67.18  4998.1   67.35  5004.9   67.68  5011.2   68.13  5012.9   68.62
    5037   76.05  5037.1   76.08 5039.99   77.61  5040.1   77.67    5041   78.15
  5042.5   78.16 5042.59   78.16  5042.7   78.16 5042.81   78.16  5069.8   78.25
  5082.7   77.87  5108.5   77.99    5127   78.07  5158.5   77.87  5189.2   77.68
    5213    78.8  5269.8      79  5309.8    79.2  5609.8    78.9  5669.8    78.8
  5719.8    78.6  5785.9   78.63  5905.9   78.68  5915.9   78.69  5935.9   78.69
  5948.8    78.7  6028.8    78.2  6205.9   79.26  6228.8    79.4  6278.1   77.99
  6298.8    77.4  6303.1   77.45  6454.1   79.34  6458.8    79.4  6488.8    79.2
  6605.3   80.37  6648.8    80.8  6728.8    80.7  6848.8    80.4  7068.8    79.8
  7348.8    81.1  7518.8      82  7708.8    81.5  7808.8    81.6  8108.8    81.2
  8298.8    82.1  8418.8    82.1  8569.1    82.8
BR U #Mann= 10
  1585.3      .2  1585.3      .1  2575.1     .14  2694.5      .1  2840.9     .14
  3408.6      .1  4959.2    .035    5041      .1  6605.3     .14  8569.1      .2
BR U Banks=4959.2,5041
BR D #Sta/Elev= 118
  1585.3   82.42  1705.3   81.92  1895.3   79.12  1955.3   78.82  2135.3   78.52
  2495.3   79.92  2575.1   80.16  2595.3   80.22  2635.3   78.02  2655.3   78.32
  2694.5   78.21  2765.3   78.02  2840.9   77.64  2865.3   77.52  2945.3   77.22
  3055.3   77.72  3095.3   78.72  3165.3   78.82  3215.3   78.72  3255.3   78.42
  3408.6    78.5  3455.3   78.52  3495.3   78.62  3575.3   78.52  3715.3   78.52
  3815.3   77.72  3915.3   77.32  4003.1   77.53  4083.1   77.72  4113.1   77.79
  4125.2   77.82  4133.1    77.8  4255.2   77.42  4405.2   75.52  4423.1   75.52
  4465.2   75.52  4535.2   76.22  4543.1   75.94  4555.2   75.52  4601.7   75.82
  4631.1   75.47  4651.7   75.22  4671.1   75.03  4701.7   74.72  4749.5   76.33
  4759.4   77.32  4766.7   77.38  4819.5   77.85    4845   77.97  4892.7    78.2
  4906.9   78.35    4925   78.55 4948.09   78.57  4948.2   78.57 4948.31   78.57
  4951.8   78.57  4959.2   78.29  4968.1   76.75 4968.21   76.73  4968.3   76.72
  4970.5   76.34  4970.6   76.32  4982.4   71.33  4985.1   69.82  4987.1   68.26
  4992.2      67  4998.1   67.17  5004.9    67.5  5011.2   67.95  5012.9   68.44
    5037   75.87  5037.1    75.9 5039.99   77.43  5040.1   77.49    5041   77.97
  5042.5   77.98 5042.59   77.98  5042.7   77.98 5042.81   77.98  5069.8   78.07
  5082.7   77.69  5108.5   77.81    5127   77.89  5158.5   77.69  5189.2    77.5
    5213   78.62  5269.8   78.82  5309.8   79.02  5609.8   78.72  5669.8   78.62
  5719.8   78.42  5785.9   78.45  5905.9    78.5  5915.9   78.51  5935.9   78.51
  5948.8   78.52  6028.8   78.02  6205.9   79.08  6228.8   79.22  6278.1   77.81
  6298.8   77.22  6303.1   77.27  6454.1   79.16  6458.8   79.22  6488.8   79.02
  6605.3   80.19  6648.8   80.62  6728.8   80.52  6848.8   80.22  7068.8   79.62
  7348.8   80.92  7518.8   81.82  7708.8   81.32  7808.8   81.42  8108.8   81.02
  8298.8   81.92  8418.8   81.92  8569.1   82.62
BR D #Mann= 10
  1585.3      .2  1585.3      .1  2575.1     .14  2694.5      .1  2840.9     .14
  3408.6      .1  4959.2    .035    5041      .1  6605.3     .14  8569.1      .2
BR D Banks=4959.2,5041
BC Design=,, 0 ,, 0 ,,,,,,

Type RM Length L Ch R = 1 ,80971.3 ,276.3,276.3,276.3
BEGIN DESCRIPTION:
Downstream Section of Bridge/Culvert/Weir
END DESCRIPTION:
XS GIS Cut Line= 6
      3104034.19      13896382.4      3104153.15     13893843.04
      3104158.99     13893369.43      3104191.11     13892755.49
      3104251.36     13891697.04      3103238.53     13889639.78
#Sta/Elev= 30
  1585.3   82.39  1955.3   78.79  2575.1   80.13  2595.3   80.19  2635.3   77.99
  2694.5   78.18  2840.9   77.61  3408.6   78.47  4133.1   77.77  4405.2   75.49
  4535.2   76.19  4701.7   74.69  4759.4   77.29  4959.2   78.26  4970.6   76.29
  4987.1   68.23  4992.2   66.97  5011.2   67.92    5041   77.94  5189.2   77.47
    5213   78.59  5309.8   78.99  6028.8   77.99  6228.8   79.19  6298.8   77.19
  6605.3   80.16  7068.8   79.59  7518.8   81.79  8108.8   80.99  8569.1   82.59
#Mann= 10 , 1 , 0
  1585.3      .2       0  1585.3      .1       0  2575.1     .14       0
  2694.5      .1       0  2840.9     .14       0  3408.6      .1       0
  4959.2    .035       0    5041      .1       0  6605.3     .14       0
  8569.1      .2       0
#XS Ineff= 2 , 0
       0    4245    82.2    6621       0    82.2
Permanent Ineff=
       F       F
Bank Sta=4959.2,5041
XS Rating Curve= 0
Exp/Cntr=.5,.3

Type RM Length L Ch R = 1 ,80695.0 ,623.5,632.7,47.3
BEGIN DESCRIPTION:
Cross Section 80695.0-Interpolated
END DESCRIPTION:
XS GIS Cut Line= 6
      3104225.37     13896386.64      3104512.21     13893079.49
      3104343.48     13892657.65      3104304.39     13892274.43
      3104304.39     13891680.33      3103590.22     13889102.33
#Sta/Elev= 30
  1403.8   82.51  1713.8   79.73  2628.5   79.34  3263.8   78.53  3474.2    79.8
  3786.1    80.7  3896.1   78.36  3916.1   76.78  4496.1   80.13  4686.1   77.35
  4753.5   78.73  4963.5   77.34  4973.5   75.68 4990.45   68.14 5001.46   66.23
 5009.56   67.73 5025.57    74.7  5043.5   77.68  5467.8   79.43  5567.8   76.88
  5578.9   77.83  6162.2   77.34  6472.2   79.19  6782.2   77.73  6972.2   80.11
  7542.2   80.85  7742.2   79.39  8182.2   81.85  8612.2   81.47  8832.2   82.64
#Mann= 6 , 1 , 0
  1403.8      .2       0  1403.8      .1       0  2628.5     .14       0
  3474.2      .1       0  4963.5    .035       0  5043.5      .1       0
#XS Ineff= 2 , 0
       0    4396    81.6    6470       0    81.6
Permanent Ineff=
       F       F
Bank Sta=4963.5,5043.5
XS Rating Curve= 0
Exp/Cntr=.5,.3

Type RM Length L Ch R = 1 ,80062.3 ,48,48,48
BEGIN DESCRIPTION:
Upstream Section of Bridge/Culvert/Weir
END DESCRIPTION:
XS GIS Cut Line= 6
      3104524.92      13896404.1      3104814.94     13892669.64
      3104805.95     13892400.37      3104539.84     13892326.11
      3104422.26     13892214.71      3104418.05     13887828.04
#Sta/Elev= 30
     943    82.6    1153   79.81    1183   76.46    1203   80.06    1263   81.28
    1893   79.55    1933   76.93    1983   78.98  2194.2    78.9    3032   78.43
    3973   79.04    4243   76.72    4563   78.43    4673   76.19  4792.2   77.03
 4876.97   79.08 4982.16   78.16 4990.45   66.43 5001.46   64.52 5009.56   66.02
 5012.01   69.11 5025.57   72.99 5029.94   78.14  6003.5   78.53  6553.5   77.26
    6800   78.62  7683.5   77.84  7723.5   78.98    9573   81.98  9789.2   82.74
#Mann= 8 , 1 , 0
     943      .2       0     943      .1       0  2194.2     .14       0
    3032      .1       0 4982.16    .035       0 5029.94      .1       0
    6800     .12       0    9573      .2       0
#XS Ineff= 2 , 0
       0    4416    81.7    6450       0    81.7
Permanent Ineff=
       F       F
Bank Sta=4982.16,5029.94
XS Rating Curve= 0
Exp/Cntr=.5,.3

Type RM Length L Ch R = 3 ,80038.3 ,,,
BEGIN DESCRIPTION:
TURNEY DRIVE, SKEW ANGLE OF 25 DEGREES
Structure ID: P18-40
END DESCRIPTION:
Bridge Culvert--1,0,-1,-1, 0
Deck Dist Width WeirC Skew NumUp NumDn MinLoCord MaxHiCord MaxSubmerge Is_Ogee
10,28,2.6,0, 60, 60, , , .95, 0, 1,1,,
     943    1093    1133    1153    1173    1183    1193    1203    1213    1223
    1263    1393    1693    1783    1893    1933    1983    2493    2543    2613
    2973    3303    3353    3603    3973    4093    4243    4433    4563  4599.3
    4673  4792.2 4876.97 4900.72 4982.16 4983.26 5028.65 5029.94 5054.69    5145
  5206.9  5256.9  5296.9  5346.9  5376.9    5560  6003.5  6183.5  6553.5  6613.5
  6783.5  6843.5  7683.5  7723.5  7963.5  8503.5  8863.5  9313.5  9403.5  9789.2
   82.57   81.25   79.89   79.78   77.01   76.43   78.94   80.03   80.46   80.23
   81.25   80.17   79.69   80.23   79.52    76.9   78.95   78.95   78.47   78.74
   78.18   79.42   78.31   78.32   79.01   77.25   76.69   78.23    78.4    78.8
   78.71   78.58   79.06   78.47   78.36   78.37   78.42   78.42   78.57   77.94
   78.13   78.19    78.4    78.6    78.6      79    78.5   77.34   77.23   78.18
   78.82      78   77.81   78.95   78.78   79.71   81.26   80.75   81.35   82.71
   82.57   81.25   79.89   79.78   77.01   76.43   78.94   80.03   80.46   80.23
   81.25   80.17   79.69   80.23   79.52    76.9   78.95   78.95   78.47   78.74
   78.18   79.42   78.31   78.32   79.01   77.25   76.69   78.23    78.4   77.66
   76.16      77   79.05   78.34   78.13   76.57   76.62   78.11   78.56   77.93
   78.12   77.73   78.35   77.42   77.77   77.98    78.5   77.34   77.23   78.18
   78.82      78   77.81   78.95   78.78   79.71   81.26   80.75   81.35   82.71
     943    1093    1133    1153    1173    1183    1193    1203    1213    1223
    1263    1393    1693    1783    1893    1933    1983    2493    2543    2613
    2973    3303    3353    3603    3973    4093    4243    4433    4563  4599.3
    4673  4792.2 4876.97 4900.72 4982.16 4983.26 5028.65 5029.94 5054.69    5145
  5206.9  5256.9  5296.9  5346.9  5376.9    5560  6003.5  6183.5  6553.5  6613.5
  6783.5  6843.5  7683.5  7723.5  7963.5  8503.5  8863.5  9313.5  9403.5  9789.2
   82.57   81.25   79.89   79.78   77.01   76.43   78.94   80.03   80.46   80.23
   81.25   80.17   79.69   80.23   79.52    76.9   78.95   78.95   78.47   78.74
   78.18   79.42   78.31   78.32   79.01   77.25   76.69   78.23    78.4    78.8
   78.71   78.58   79.06   78.47   78.36   78.37   78.42   78.42   78.57   77.94
   78.13   78.19    78.4    78.6    78.6      79    78.5   77.34   77.23   78.18
   78.82      78   77.81   78.95   78.78   79.71   81.26   80.75   81.35   82.71
   82.48   81.16    79.8   79.69   76.92   76.34   78.85   79.94   80.37   80.14
   81.16   80.08    79.6   80.14   79.43   76.81   78.86   78.86   78.38   78.65
   78.09   79.33   78.22   78.23   78.92   77.16    76.6   78.14   78.31   77.57
   76.07   76.91   78.96   78.25   78.04   76.48   76.53   78.02   78.47   77.84
   78.03   77.64   78.26   77.33   77.68   77.89   78.41   77.25   77.14   78.09
   78.73   77.91   77.72   78.86   78.69   79.62   81.17   80.66   81.26   82.62
Pier Skew, UpSta & Num, DnSta & Num=  ,4997.5, 2 ,4997.5, 2 , 0 , 0 , 0 ,,
       1       1
   64.52   77.61
       1       1
   64.43   77.52
Pier Skew, UpSta & Num, DnSta & Num=  ,5012, 2 ,5012, 2 , 0 , 0 , 0 ,,
       1       1
   67.45   77.66
       1       1
   67.36   77.57
BR Coef= 1 , 1 , 0 ,1.25, 0 ,,,.8,0,2,0,
WSPro=,,,, 1 ,,,, 0 ,,,, 0 ,,,,-1 ,-1 ,-1 , 0 , 0 , 0 , 0 , 0
BR U #Sta/Elev= 107
     943   82.57    1093   81.25    1133   79.89    1153   79.78    1173   77.01
    1183   76.43    1193   78.94    1203   80.03    1213   80.46    1223   80.23
    1263   81.25    1393   80.17    1553   79.95    1693   79.69    1783   80.23
    1893   79.52    1933    76.9    1983   78.95    2063   78.81  2194.2   78.87
    2333   78.93    2493   78.95    2543   78.47    2613   78.74    2973   78.18
    3032    78.4    3303   79.42    3353   78.31    3603   78.32    3783   78.85
    3973   79.01    4013   78.42    4093   77.25    4243   76.69    4433   78.23
    4563    78.4  4599.3   77.66    4673   76.16  4768.3   76.98  4772.2   77.01
  4792.2      77 4876.97   79.05  4885.8   78.79 4900.72   78.34 4943.66   78.41
  4943.8   78.41  4975.5   78.18 4977.99   78.16  4978.1   78.16 4978.21   78.16
 4982.16   78.13 4983.17    76.7 4983.26   76.57  4983.8   75.81 4990.45    66.4
 4997.45   65.67 5001.46   64.49 5009.56   65.99 5012.01   69.08  5016.6   70.39
 5025.57   72.96  5028.3   76.18 5028.65   76.59 5028.76   76.72 5029.09   77.11
  5029.2   77.24 5029.31   77.37 5029.94   78.11 5054.69   78.56 5095.19   78.07
 5122.85   78.05 5129.77   77.88  5134.9    77.9    5145   77.93  5199.3    78.1
  5206.9   78.12  5239.3   77.87  5256.9   77.73  5296.9   78.35  5334.3   77.65
  5346.9   77.42  5376.9   77.77  5419.3   77.82  5469.3   77.88    5560   77.98
  6003.5    78.5  6103.5   77.68  6183.5   77.34  6553.5   77.23  6613.5   78.18
  6783.5   78.82    6800   78.59  6843.5      78  7123.5   77.82  7393.5   78.03
  7683.5   77.81  7723.5   78.95  7963.5   78.78  8203.5   79.33  8503.5   79.71
  8723.5   80.81  8863.5   81.26  9313.5   80.75  9363.5   80.93  9403.5   81.35
    9573   81.95  9789.2   82.71
BR U #Mann= 8
     943      .2     943      .1  2194.2     .14    3032      .1 4982.16    .035
 5029.94      .1    6800     .12    9573      .2
BR U Banks=4982.16,5029.94
BR D #Sta/Elev= 107
     943   82.48    1093   81.16    1133    79.8    1153   79.69    1173   76.92
    1183   76.34    1193   78.85    1203   79.94    1213   80.37    1223   80.14
    1263   81.16    1393   80.08    1553   79.86    1693    79.6    1783   80.14
    1893   79.43    1933   76.81    1983   78.86    2063   78.72  2194.2   78.78
    2333   78.84    2493   78.86    2543   78.38    2613   78.65    2973   78.09
    3032   78.31    3303   79.33    3353   78.22    3603   78.23    3783   78.76
    3973   78.92    4013   78.33    4093   77.16    4243    76.6    4433   78.14
    4563   78.31  4599.3   77.57    4673   76.07  4768.3   76.89  4772.2   76.92
  4792.2   76.91 4876.97   78.96  4885.8    78.7 4900.72   78.25 4943.66   78.32
  4943.8   78.32  4975.5   78.09 4977.99   78.07  4978.1   78.07 4978.21   78.07
 4982.16   78.04 4983.17   76.61 4983.26   76.48  4983.8   75.72 4990.45   66.31
 4997.45   65.58 5001.46    64.4 5009.56    65.9 5012.01   68.99  5016.6    70.3
 5025.57   72.87  5028.3   76.09 5028.65    76.5 5028.76   76.63 5029.09   77.02
  5029.2   77.15 5029.31   77.28 5029.94   78.02 5054.69   78.47 5095.19   77.98
 5122.85   77.96 5129.77   77.79  5134.9   77.81    5145   77.84  5199.3   78.01
  5206.9   78.03  5239.3   77.78  5256.9   77.64  5296.9   78.26  5334.3   77.56
  5346.9   77.33  5376.9   77.68  5419.3   77.73  5469.3   77.79    5560   77.89
  6003.5   78.41  6103.5   77.59  6183.5   77.25  6553.5   77.14  6613.5   78.09
  6783.5   78.73    6800    78.5  6843.5   77.91  7123.5   77.73  7393.5   77.94
  7683.5   77.72  7723.5   78.86  7963.5   78.69  8203.5   79.24  8503.5   79.62
  8723.5   80.72  8863.5   81.17  9313.5   80.66  9363.5   80.84  9403.5   81.26
    9573   81.86  9789.2   82.62
BR D #Mann= 8
     943      .2     943      .1  2194.2     .14    3032      .1 4982.16    .035
 5029.94      .1    6800     .12    9573      .2
BR D Banks=4982.16,5029.94
BC Design=,, 0 ,, 0 ,,,,,,

Type RM Length L Ch R = 1 ,80014.3 ,207,207,207
BEGIN DESCRIPTION:
Downstream Section of Bridge/Culvert/Weir
END DESCRIPTION:
XS GIS Cut Line= 6
      3104549.11     13896362.64      3104839.12     13892628.18
      3104830.13     13892358.91      3104564.02     13892284.65
      3104446.44     13892173.25      3104442.23     13887786.58
#Sta/Elev= 30
     943   82.46    1153   79.67    1183   76.32    1203   79.92    1263   81.14
    1893   79.41    1933   76.79    1983   78.84  2194.2   78.76    3032   78.29
    3973    78.9    4243   76.58    4563   78.29    4673   76.05  4792.2   76.89
 4876.97   78.94 4982.16   78.02 4990.45   66.29 5001.46   64.38 5009.56   65.88
 5012.01   68.97 5025.57   72.85 5029.94      78  6003.5   78.39  6553.5   77.12
    6800   78.48  7683.5    77.7  7723.5   78.84    9573   81.84  9789.2    82.6
#Mann= 8 , 1 , 0
     943      .2       0     943      .1       0  2194.2     .14       0
    3032      .1       0 4982.16    .035       0 5029.94      .1       0
    6800     .12       0    9573      .2       0
#XS Ineff= 2 , 0
       0    4476    81.7    6390       0    81.7
Permanent Ineff=
       F       F
Bank Sta=4982.16,5029.94
XS Rating Curve= 0
Exp/Cntr=.5,.3

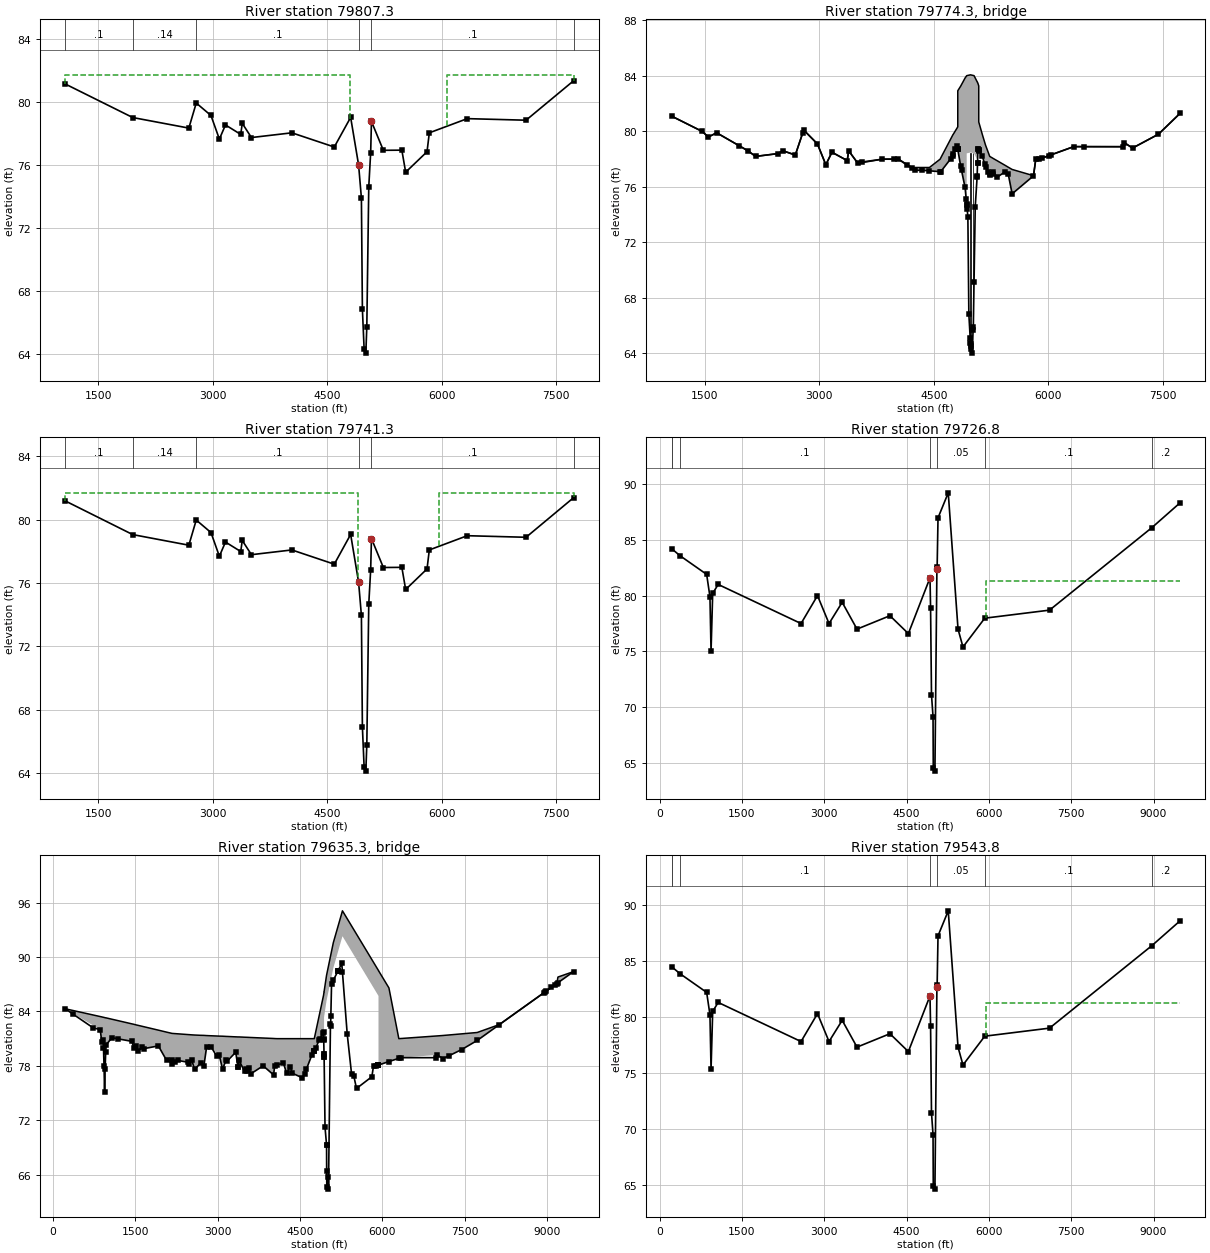
Type RM Length L Ch R = 1 ,79807.3 ,66,66,66
BEGIN DESCRIPTION:
Upstream Section of Bridge/Culvert/Weir
END DESCRIPTION:
XS GIS Cut Line= 4
      3104836.81     13896106.94      3104869.43     13892172.44
      3104870.28     13892163.13      3104877.46     13889446.33
#Sta/Elev= 30
  1066.7   81.12  1951.5   78.99  2686.7   78.32  2783.7   79.91  2976.7   79.12
  3086.7   77.62  3166.7   78.52  3366.7   77.92  3386.7   78.62  3506.7   77.72
  4036.7   78.02  4592.5   77.12 4806.99      79 4911.18   75.98 4947.86   73.88
 4960.78   66.84 4983.26   64.32 5005.92   64.04 5018.65   65.69 5044.41    74.6
 5069.33   76.77 5079.63   78.74 5235.42   76.91  5477.8   76.92  5527.8   75.52
  5807.8   76.82  5837.8   78.02  6335.3   78.92  7105.3   78.82  7727.5   81.32
#Mann= 6 , 1 , 0
  1066.7      .1       0  1951.5     .14       0  2783.7      .1       0
 4911.18    .035       0 5079.63      .1       0  7727.5      .2       0
#XS Ineff= 2 , 0
       0    4798    81.7    6070       0    81.7
Permanent Ineff=
       F       F
Bank Sta=4911.18,5079.63
XS Rating Curve= 0
Exp/Cntr=.5,.3

Type RM Length L Ch R = 3 ,79774.3 ,,,
BEGIN DESCRIPTION:
INTERSTATE 45 SOUTH FRONTAGE ROAD, SKEW ANGLE OF 25 DEGREES
Structure ID: P18-39
END DESCRIPTION:
Bridge Culvert--1,0,-1,-1, 0
Deck Dist Width WeirC Skew NumUp NumDn MinLoCord MaxHiCord MaxSubmerge Is_Ogee
10,46,2.6,0, 57, 57, , , .95, 0, 1,1,,
  1066.7  1466.7  1546.7  1656.7  2066.7  2166.7  2456.7  2526.7  2686.7  2796.7
  2976.7  3086.7  3166.7  3366.7  3386.7  3506.7  3826.7  4036.7    4214  4252.5
    4444    4584  4592.5 4752.84 4754.76 4806.99 4815.49  4815.6 4854.04 4911.18
 4932.57 4932.66 4982.53  5028.8 5074.24 5074.35 5079.63  5090.5 5090.61 5137.32
 5179.54  5234.2 5274.73 5277.37  5331.2  5437.8  5477.8  5527.8  5807.8  5837.8
  5885.3  6335.3  6985.3  6995.3  7105.3  7445.3  7727.5
    81.1      80    79.6    79.9    78.6    78.2    78.4    78.6    78.3    80.1
    79.1    77.6    78.5    77.9    78.6    77.7      78   78.01    77.4    77.4
    77.4      78   78.09   79.77   79.78   80.25   80.33   82.93   83.27   83.85
   84.02   84.02   84.08   84.02   83.53   83.53   83.47   83.28   80.68   79.78
   79.01    78.2   78.07   78.06   77.89   77.55   77.42   77.26   76.81   78.01
   78.01   78.91    78.9    79.2    78.8    79.8    81.3
    81.1      80    79.6    79.9    78.6    78.2    78.4    78.6    78.3    80.1
    79.1    77.6    78.5    77.9    78.6    77.7      78      78   77.34    77.2
   77.16    77.1    77.1   78.24   78.34   78.98   78.71   78.71   77.48   75.96
   74.74   78.42   78.48   78.42   77.93   77.71   78.72   78.63   78.62   78.22
   77.43    76.9   76.94   77.11    76.7    77.1    76.9    75.5    76.8      78
      78    78.9    78.9    79.2    78.8    79.8    81.3
  1066.7  1466.7  1546.7  1656.7  2066.7  2166.7  2456.7  2526.7  2686.7  2796.7
  2976.7  3086.7  3166.7  3366.7  3386.7  3506.7  3826.7  4036.7    4214  4252.5
    4444    4584  4592.5 4752.84 4754.76 4806.99 4815.49  4815.6 4854.04 4911.18
 4932.57 4932.66 4982.53  5028.8 5074.24 5074.35 5079.63  5090.5 5090.61 5137.32
 5179.54  5234.2 5274.73 5277.37  5331.2  5437.8  5477.8  5527.8  5807.8  5837.8
  5885.3  6335.3  6985.3  6995.3  7105.3  7445.3  7727.5
    81.1      80    79.6    79.9    78.6    78.2    78.4    78.6    78.3    80.1
    79.1    77.6    78.5    77.9    78.6    77.7      78   78.01    77.4    77.4
    77.4      78   78.09   79.77   79.78   80.25   80.33   82.93   83.27   83.85
   84.02   84.02   84.08   84.02   83.53   83.53   83.47   83.28   80.68   79.78
   79.01    78.2   78.07   78.06   77.89   77.55   77.42   77.26   76.81   78.01
   78.01   78.91    78.9    79.2    78.8    79.8    81.3
   81.08   79.98   79.58   79.88   78.58   78.18   78.38   78.58   78.28   80.08
   79.08   77.58   78.48   77.88   78.58   77.68   77.98   77.98   77.32   77.18
   77.14   77.08   77.08   78.22   78.32   78.96   78.69   78.69   77.46   75.94
   74.72    78.4   78.46    78.4   77.91   77.69    78.7   78.61    78.6    78.2
   77.41   76.88   76.92   77.09   76.68   77.08   76.88   75.48   76.78   77.98
   77.98   78.88   78.88   79.18   78.78   79.78   81.28
Pier Skew, UpSta & Num, DnSta & Num=  ,4982.1, 2 ,4982.1, 2 , 0 , 0 , 0 ,,
     2.5     2.5
    63.3   79.48
     2.5     2.5
   63.28   79.46
Pier Skew, UpSta & Num, DnSta & Num=  ,5018.7, 2 ,5018.7, 2 , 0 , 0 , 0 ,,
     2.5     2.5
   64.89   79.43
     2.5     2.5
   64.87   79.41
Abutment Skew #Up #Dn= , 2 , 2
 4932.46 4938.85
   78.42   74.38
 4932.46 4938.85
    78.4   74.36
Abutment Skew #Up #Dn= , 2 , 2
 5069.43 5074.44
   76.77   77.93
 5069.43 5074.44
   76.75   77.91
BR Coef= 1 , 1 , 0 ,1.25, 0 ,,,.8,0,2,0,
WSPro=,,,, 1 ,,,, 0 ,,,, 0 ,,,,-1 ,-1 ,-1 , 0 , 0 , 0 , 0 , 0
BR U #Sta/Elev= 90
  1066.7    81.1  1466.7      80  1546.7    79.6  1656.7    79.9  1951.5   78.97
  2066.7    78.6  2166.7    78.2  2456.7    78.4  2526.7    78.6  2686.7    78.3
  2783.7   79.89  2796.7    80.1  2976.7    79.1  3086.7    77.6  3166.7    78.5
  3366.7    77.9  3386.7    78.6  3506.7    77.7  3566.7    77.8  3826.7      78
    3974      78  4036.7      78    4144    77.6    4214   77.34  4252.5    77.2
  4352.5    77.2    4444   77.16    4584    77.1  4592.5    77.1    4723   78.03
 4752.84   78.24 4754.76   78.34  4784.3    78.7 4806.99   78.98 4815.49   78.71
  4815.6   78.71 4815.71    78.7 4854.04   77.48  4864.5    77.2 4911.18   75.96
    4926   75.11 4932.57   74.74 4932.66   74.73 4938.85   74.38 4947.86   73.86
 4960.78   66.82  4978.6   65.08 4982.07   64.74 4982.53   64.54 4983.26    64.3
  4988.9   64.69 5005.92   64.02 5017.38   65.89 5018.65   65.67  5028.8   69.18
 5044.41   74.58 5069.33   76.75 5069.43   76.77 5074.24   77.69 5074.35   77.71
 5079.63   78.72  5081.7    78.7 5090.39   78.63  5090.5   78.63 5090.61   78.62
 5137.32   78.22    5169   77.63 5179.54   77.43 5213.94   77.08  5234.2    76.9
 5235.42   76.89 5274.73   76.94 5277.37   77.11  5331.2    76.7  5437.8    77.1
  5477.8    76.9  5527.8    75.5  5807.8    76.8  5837.8      78  5885.3      78
  5923.2   78.08  6013.2   78.26  6043.2   78.32  6335.3    78.9  6465.3    78.9
  6985.3    78.9  6995.3    79.2  7105.3    78.8  7445.3    79.8  7727.5    81.3
BR U #Mann= 6
  1066.7      .1  1951.5     .14  2783.7      .1 4911.18    .035 5079.63      .1
  7727.5      .2
BR U Banks=4911.18,5079.63
BR D #Sta/Elev= 90
  1066.7   81.08  1466.7   79.98  1546.7   79.58  1656.7   79.88  1951.5   78.95
  2066.7   78.58  2166.7   78.18  2456.7   78.38  2526.7   78.58  2686.7   78.28
  2783.7   79.87  2796.7   80.08  2976.7   79.08  3086.7   77.58  3166.7   78.48
  3366.7   77.88  3386.7   78.58  3506.7   77.68  3566.7   77.78  3826.7   77.98
    3974   77.98  4036.7   77.98    4144   77.58    4214   77.32  4252.5   77.18
  4352.5   77.18    4444   77.14    4584   77.08  4592.5   77.08    4723   78.01
 4752.84   78.22 4754.76   78.32  4784.3   78.68 4806.99   78.96 4815.49   78.69
  4815.6   78.69 4815.71   78.68 4854.04   77.46  4864.5   77.18 4911.18   75.94
    4926   75.09 4932.57   74.72 4932.66   74.71 4938.85   74.36 4947.86   73.84
 4960.78    66.8  4978.6   65.06 4982.07   64.72 4982.53   64.52 4983.26   64.28
  4988.9   64.67 5005.92      64 5017.38   65.87 5018.65   65.65  5028.8   69.16
 5044.41   74.56 5069.33   76.73 5069.43   76.75 5074.24   77.67 5074.35   77.69
 5079.63    78.7  5081.7   78.68 5090.39   78.61  5090.5   78.61 5090.61    78.6
 5137.32    78.2    5169   77.61 5179.54   77.41 5213.94   77.06  5234.2   76.88
 5235.42   76.87 5274.73   76.92 5277.37   77.09  5331.2   76.68  5437.8   77.08
  5477.8   76.88  5527.8   75.48  5807.8   76.78  5837.8   77.98  5885.3   77.98
  5923.2   78.06  6013.2   78.24  6043.2    78.3  6335.3   78.88  6465.3   78.88
  6985.3   78.88  6995.3   79.18  7105.3   78.78  7445.3   79.78  7727.5   81.28
BR D #Mann= 6
  1066.7      .1  1951.5     .14  2783.7      .1 4911.18    .035 5079.63      .1
  7727.5      .2
BR D Banks=4911.18,5079.63
BC Design=,, 0 ,, 0 ,,,,,,

Type RM Length L Ch R = 1 ,79741.3 ,14.5,14.5,14.5
BEGIN DESCRIPTION:
Downstream Section of Bridge/Culvert/Weir
END DESCRIPTION:
XS GIS Cut Line= 4
      3104897.94     13896082.07      3104930.57     13892147.56
      3104931.42     13892138.25      3104938.59     13889421.45
#Sta/Elev= 30
  1066.7   81.19  1951.5   79.06  2686.7   78.39  2783.7   79.98  2976.7   79.19
  3086.7   77.69  3166.7   78.59  3366.7   77.99  3386.7   78.69  3506.7   77.79
  4036.7   78.09  4592.5   77.19 4806.99   79.07 4911.18   76.05 4947.86   73.95
 4960.78   66.91 4983.26   64.39 5005.92   64.11 5018.65   65.76 5044.41   74.67
 5069.33   76.84 5079.63   78.81 5235.42   76.98  5477.8   76.99  5527.8   75.59
  5807.8   76.89  5837.8   78.09  6335.3   78.99  7105.3   78.89  7727.5   81.39
#Mann= 6 , 1 , 0
  1066.7      .1       0  1951.5     .14       0  2783.7      .1       0
 4911.18    .035       0 5079.63      .1       0  7727.5      .2       0
#XS Ineff= 2 , 0
       0    4900    81.7    5960       0    81.7
Permanent Ineff=
       F       F
Bank Sta=4911.18,5079.63
XS Rating Curve= 0
Exp/Cntr=.5,.3

Type RM Length L Ch R = 1 ,79726.8 ,183,183,183
BEGIN DESCRIPTION:
Upstream Section of Bridge/Culvert/Weir
END DESCRIPTION:
XS GIS Cut Line= 3
      3104912.23     13896903.11      3104937.42     13892122.73
      3104971.42     13887639.61
#Sta/Elev= 30
   219.2   84.19   368.8   83.57   856.7   81.89   916.7   79.89   936.7   74.99
   966.7   80.19  1066.7   80.99  2576.7   77.49  2876.7   79.99  3086.7   77.49
  3326.7   79.39  3596.7   76.99  4196.7   78.19  4532.5   76.59 4926.93   81.58
 4937.47   78.87 4954.14    71.1 4982.26   69.16 4986.71   64.54 5016.84   64.28
 5053.05   82.54 5056.24   82.34 5073.07   86.95  5259.4   89.19  5437.8   76.99
  5527.8   75.39    5925   77.97  7105.3   78.69  8971.9   86.08  9482.9   88.29
#Mann= 7 , 1 , 0
   219.2      .2       0   219.2     .07       0   368.8      .1       0
 4926.93    .035       0 5056.24     .05       0    5925      .1       0
  8971.9      .2       0
#XS Ineff= 2 , 0
       0    4926      81    5940       0    81.3
Permanent Ineff=
       F       F
Bank Sta=4926.93,5056.24
XS Rating Curve= 0
Exp/Cntr=.5,.3

Type RM Length L Ch R = 3 ,79635.3 ,,,
BEGIN DESCRIPTION:
INTERSTATE 45, SKEW ANGLE OF 25 DEGREES
Structure ID: P18-38
END DESCRIPTION:
Bridge Culvert--1,0,-1,-1, 0
Deck Dist Width WeirC Skew NumUp NumDn MinLoCord MaxHiCord MaxSubmerge Is_Ogee
10,163,2.6,0, 60, 60, , , .95, 0, 1,1,,
   219.2   856.7   886.7   906.7   916.7   926.7   936.7   946.7   956.7   966.7
  1066.7  1436.7  1466.7  1516.7  1546.7  1916.7  2066.7  2166.7  2526.7  2576.7
  2686.7  2746.7  2796.7  3026.7  3086.7  3146.7  3326.7  3366.7  3386.7  3486.7
  3566.7  3596.7  3826.7  4016.7  4036.7  4079.2  4196.7  4252.5  4322.5  4352.5
  4532.5 4758.01 4926.93 4936.21  4936.3  4981.8  5105.5  5271.8 5928.11 5928.27
 5928.38  6118.7  6299.2  6995.3  7105.3  7727.5  8128.7  9178.7  9198.7  9482.9
    84.3   83.44    83.4   83.37   83.36   83.34   83.33   83.31    83.3   83.29
   83.15   82.63   82.59   82.51   82.47   81.94   81.72   81.58   81.42    81.4
   81.37   81.36   81.34   81.28   81.27   81.25    81.2   81.19   81.19   81.16
   81.14   81.13   81.07   81.02   81.01      81      81      81      81      81
      81      81   85.78   86.16   86.16   87.99    91.6   95.11   88.52   88.51
   88.51    86.6      81    81.3   81.35   81.68   82.55   87.09    87.8    88.4
    84.3      82    80.6    80.8      80      78    75.1    77.7    79.5    80.3
    81.1    80.7      80    80.2    79.6    80.2    78.6    78.2    78.6    77.6
    78.3      78    80.1    79.2    77.6    78.6    79.5    77.9    78.6    77.4
    77.8    77.1      78      77      78   78.08    78.3    77.2    77.9    77.2
    76.7   79.66   81.69    79.3   83.36   85.19    88.8   92.31   85.72   85.71
   78.09   78.47   78.83    79.2    78.8    80.8   82.54   87.08   87.17    88.4
   219.2   856.7   886.7   906.7   916.7   926.7   936.7   946.7   956.7   966.7
  1066.7  1436.7  1466.7  1516.7  1546.7  1916.7  2066.7  2166.7  2526.7  2576.7
  2686.7  2746.7  2796.7  3026.7  3086.7  3146.7  3326.7  3366.7  3386.7  3486.7
  3566.7  3596.7  3826.7  4016.7  4036.7  4079.2  4196.7  4252.5  4322.5  4352.5
  4532.5 4758.01 4926.93 4936.21  4936.3  4981.8  5105.5  5271.8 5928.11 5928.27
 5928.38  6118.7  6299.2  6995.3  7105.3  7727.5  8128.7  9178.7  9198.7  9482.9
    84.3   83.44    83.4   83.37   83.36   83.34   83.33   83.31    83.3   83.29
   83.15   82.63   82.59   82.51   82.47   81.94   81.72   81.58   81.42    81.4
   81.37   81.36   81.34   81.28   81.27   81.25    81.2   81.19   81.19   81.16
   81.14   81.13   81.07   81.02   81.01      81      81      81      81      81
      81      81   85.78   86.16   86.16   87.99    91.6   95.11   88.52   88.51
   88.51    86.6      81    81.3   81.35   81.68   82.55   87.09    87.8    88.4
   84.11   81.81   80.41   80.61   79.81   77.81   74.91   77.51   79.31   80.11
   80.91   80.51   79.81   80.01   79.41   80.01   78.41   78.01   78.41   77.41
   78.11   77.81   79.91   79.01   77.41   78.41   79.31   77.71   78.41   77.21
   77.61   76.91   77.81   76.81   77.81   77.89   78.11   77.01   77.71   77.01
   76.51   79.47    81.5   79.11   83.17      85   88.61   92.12   85.53   85.52
    77.9   78.28   78.64   79.01   78.61   80.61   82.35   86.89   86.98   88.21
Abutment Skew #Up #Dn= , 2 , 2
  4936.1 4937.57
   83.36   78.93
  4936.1 4937.57
   83.17   78.74
BR Coef= 1 , 1 , 0 ,1.25, 0 ,,,.8,0,2,0,
WSPro=,,,, 1 ,,,, 0 ,,,, 0 ,,,,-1 ,-1 ,-1 , 0 , 0 , 0 , 0 , 0
BR U #Sta/Elev= 120
   219.2    84.3   368.8   83.68   726.7    82.2   856.7      82   886.7    80.6
   906.7    80.8   916.7      80   926.7      78   936.7    75.1   946.7    77.7
   956.7    79.5   966.7    80.3  1066.7    81.1  1179.2   80.98  1436.7    80.7
  1466.7      80  1516.7    80.2  1546.7    79.6  1626.7    80.1  1656.7    79.9
  1916.7    80.2  2066.7    78.6  2156.7    78.6  2166.7    78.2  2219.2   78.41
  2266.7    78.6  2456.7    78.4  2466.7    78.2  2526.7    78.6  2576.7    77.6
  2686.7    78.3  2746.7      78  2796.7    80.1  2876.7    80.1  2976.7    79.1
  3026.7    79.2  3086.7    77.6  3146.7    78.6  3166.7    78.5  3326.7    79.5
  3366.7    77.9  3376.7    77.9  3386.7    78.6  3486.7    77.4  3506.7    77.7
  3526.7    77.4  3566.7    77.8  3596.7    77.1  3826.7      78  4016.7      77
  4036.7      78  4079.2   78.08  4196.7    78.3  4252.5    77.2  4322.5    77.9
  4352.5    77.2  4532.5    76.7  4592.5    77.1  4612.5    77.6 4715.72   79.22
 4757.79   79.66  4757.9   79.66 4758.01   79.66 4783.42   79.93  4844.9   80.81
 4855.77   80.96  4919.3   81.61 4926.93   81.69  4929.9   80.93    4930    80.9
 4936.21    79.3  4936.3   79.28 4937.47   78.98 4937.57   78.93 4954.14   71.21
  4981.8    69.3 4982.26   69.27 4983.89   66.44 4986.71   64.65  5016.2    65.7
 5016.84   64.39 5053.05   82.65 5056.24   82.45  5060.2   83.53 5073.07   87.06
  5105.5   87.45 5189.29   88.46  5189.4   88.46 5189.51   88.46  5259.4    89.3
  5271.8   88.32  5358.6    81.5  5437.8    77.1  5477.8    76.9  5527.8    75.5
  5807.8    76.8  5837.8      78  5885.3      78    5925   78.08 5928.11   78.09
 5928.27   78.09 5928.38   78.09  6118.7   78.47  6299.2   78.83  6335.3    78.9
  6985.3    78.9  6995.3    79.2  7105.3    78.8  7219.2   79.13  7445.3    79.8
  7727.5    80.8  8128.7   82.54  8948.7   86.09  8971.9   86.19  8978.7   86.22
  9078.7   86.65  9148.7   86.95  9178.7   87.08  9198.7   87.17  9482.9    88.4
BR U #Mann= 7
   219.2      .2   219.2     .07   368.8      .1 4926.93    .035 5056.24     .05
    5925      .1  8971.9      .2
BR U Banks=4926.93,5056.24
BR D #Sta/Elev= 120
   219.2   84.11   368.8   83.49   726.7   82.01   856.7   81.81   886.7   80.41
   906.7   80.61   916.7   79.81   926.7   77.81   936.7   74.91   946.7   77.51
   956.7   79.31   966.7   80.11  1066.7   80.91  1179.2   80.79  1436.7   80.51
  1466.7   79.81  1516.7   80.01  1546.7   79.41  1626.7   79.91  1656.7   79.71
  1916.7   80.01  2066.7   78.41  2156.7   78.41  2166.7   78.01  2219.2   78.22
  2266.7   78.41  2456.7   78.21  2466.7   78.01  2526.7   78.41  2576.7   77.41
  2686.7   78.11  2746.7   77.81  2796.7   79.91  2876.7   79.91  2976.7   78.91
  3026.7   79.01  3086.7   77.41  3146.7   78.41  3166.7   78.31  3326.7   79.31
  3366.7   77.71  3376.7   77.71  3386.7   78.41  3486.7   77.21  3506.7   77.51
  3526.7   77.21  3566.7   77.61  3596.7   76.91  3826.7   77.81  4016.7   76.81
  4036.7   77.81  4079.2   77.89  4196.7   78.11  4252.5   77.01  4322.5   77.71
  4352.5   77.01  4532.5   76.51  4592.5   76.91  4612.5   77.41 4715.72   79.03
 4757.79   79.47  4757.9   79.47 4758.01   79.47 4783.42   79.74  4844.9   80.62
 4855.77   80.77  4919.3   81.42 4926.93    81.5  4929.9   80.74    4930   80.71
 4936.21   79.11  4936.3   79.09 4937.47   78.79 4937.57   78.74 4954.14   71.02
  4981.8   69.11 4982.26   69.08 4983.89   66.25 4986.71   64.46  5016.2   65.51
 5016.84    64.2 5053.05   82.46 5056.24   82.26  5060.2   83.34 5073.07   86.87
  5105.5   87.26 5189.29   88.27  5189.4   88.27 5189.51   88.27  5259.4   89.11
  5271.8   88.13  5358.6   81.31  5437.8   76.91  5477.8   76.71  5527.8   75.31
  5807.8   76.61  5837.8   77.81  5885.3   77.81    5925   77.89 5928.11    77.9
 5928.27    77.9 5928.38    77.9  6118.7   78.28  6299.2   78.64  6335.3   78.71
  6985.3   78.71  6995.3   79.01  7105.3   78.61  7219.2   78.94  7445.3   79.61
  7727.5   80.61  8128.7   82.35  8948.7    85.9  8971.9      86  8978.7   86.03
  9078.7   86.46  9148.7   86.76  9178.7   86.89  9198.7   86.98  9482.9   88.21
BR D #Mann= 7
   219.2      .2   219.2     .07   368.8      .1 4926.93    .035 5056.24     .05
    5925      .1  8971.9      .2
BR D Banks=4926.93,5056.24
BC Design=,, 0 ,, 0 ,,,,,,

Type RM Length L Ch R = 1 ,79543.8 ,3.5,3.5,3.5
BEGIN DESCRIPTION:
Downstream Section of Bridge/Culvert/Weir
END DESCRIPTION:
XS GIS Cut Line= 3
      3105089.15     13896856.32      3105114.34     13892075.95
      3105148.34     13887592.82
#Sta/Elev= 30
   219.2   84.52   368.8    83.9   856.7   82.22   916.7   80.22   936.7   75.32
   966.7   80.52  1066.7   81.32  2576.7   77.82  2876.7   80.32  3086.7   77.82
  3326.7   79.72  3596.7   77.32  4196.7   78.52  4532.5   76.92 4926.93   81.91
 4937.47    79.2 4954.14   71.43 4982.26   69.49 4986.71   64.87 5016.84   64.61
 5053.05   82.87 5056.24   82.67 5073.07   87.28  5259.4   89.52  5437.8   77.32
  5527.8   75.72    5925    78.3  7105.3   79.02  8971.9   86.41  9482.9   88.62
#Mann= 7 , 1 , 0
   219.2      .2       0   219.2     .07       0   368.8      .1       0
 4926.93    .035       0 5056.24     .05       0    5925      .1       0
  8971.9      .2       0
#XS Ineff= 2 , 0
       0    4926      81    5940       0    81.3
Permanent Ineff=
       F       F
Bank Sta=4926.93,5056.24
XS Rating Curve= 0
Exp/Cntr=.5,.3