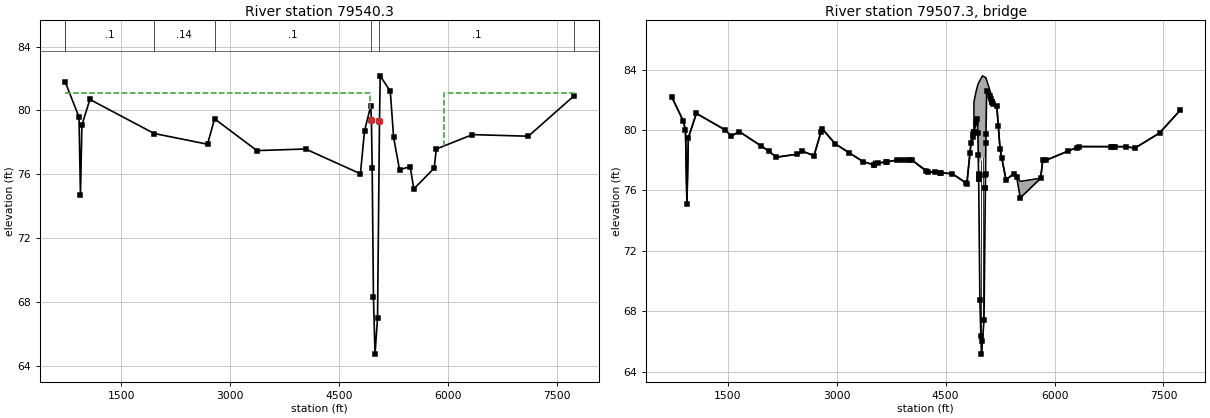
HEC-RAS study P118-00-00.PRJ: P118-00-00

--- P118-00-00.g01 (geometry) --- (continued)

Type RM Length L Ch R = 1 ,79540.3 ,66,66,66
BEGIN DESCRIPTION:
Upstream Section of Bridge/Culvert/Weir
END DESCRIPTION:
XS GIS Cut Line= 3
      3105094.92     13896340.84      3105115.39     13892085.59
      3105188.85     13889341.08
#Sta/Elev= 30
   726.7   81.79   916.7   79.59   936.7   74.69   956.7   79.09  1066.7   80.69
  1951.5   78.56  2686.7   77.89  2783.7   79.48  3366.7   77.49  4036.7   77.59
 4792.25   76.04 4848.67   78.71 4934.48   80.29 4943.94   79.39  4954.4   76.37
 4971.88   68.34 4993.45   64.75 5028.12      67 5055.15   79.32 5064.88   82.17
 5203.93    81.2 5249.43   78.32  5331.2   76.29  5477.8   76.49  5527.8   75.09
  5807.8   76.39  5837.8   77.59  6335.3   78.49  7105.3   78.39  7727.5   80.89
#Mann= 7 , 1 , 0
   726.7      .2       0   726.7      .1       0  1951.5     .14       0
  2783.7      .1       0 4943.94    .035       0 5055.15      .1       0
  7727.5      .2       0
#XS Ineff= 2 , 0
       0    4918    81.1    5948       0    81.1
Permanent Ineff=
       F       F
Bank Sta=4943.94,5055.15
XS Rating Curve= 0
Exp/Cntr=.5,.3

Type RM Length L Ch R = 3 ,79507.3 ,,,
BEGIN DESCRIPTION:
INTERSTATE 45 NORTH FRONTAGE ROAD, SKEW ANGLE OF 25 DEGREES
Structure ID: P18-37,,,,
END DESCRIPTION:
Bridge Culvert--1,0,-1,-1, 0
Deck Dist Width WeirC Skew NumUp NumDn MinLoCord MaxHiCord MaxSubmerge Is_Ogee
10,46,2.6,0, 56, 56, , , .95, 0, 1,1,,
   726.7   886.7   916.7   936.7   956.7  1066.7  1466.7  1546.7  1656.7  2066.7
  2166.7  2456.7  2526.7  2686.7  2796.7  2976.7  3366.7  3506.7    3509  3566.7
  3826.7  4036.7  4252.5  4592.5 4792.25 4848.67 4889.39  4889.5  4922.9 4934.48
 4943.94 4953.41  4953.5  5006.7 5048.76 5048.87 5055.15 5064.88 5112.84  5140.6
 5140.71 5151.15 5203.93 5249.43  5331.2  5437.8  5477.8  5527.8  5807.8  5837.8
  5885.3  6335.3  6985.3  7105.3  7445.3  7727.5
    82.2    80.6      80    75.1    79.5    81.1      80    79.6    79.9    78.6
    78.2    78.4    78.6    78.3    80.1    79.1    77.9    77.7   77.94   77.81
   78.01   78.01   77.25   77.11   76.46   79.13   79.89   81.85   82.64   82.84
      83   83.13   83.13   83.59   83.48   83.48   83.45    83.3   82.58   82.13
   81.87   81.73   81.62   78.74   76.71   77.11   76.91    76.6   76.81   78.01
   78.01   78.91    78.9    78.8    79.8    81.3
    82.2    80.6      80    75.1    79.5    81.1      80    79.6    79.9    78.6
    78.2    78.4    78.6    78.3    80.1    79.1    77.9    77.7    77.7    77.8
      78      78    77.2    77.1   76.45   79.12   79.88   79.89   80.49    80.7
    79.8   77.07   77.76   78.22   78.11   77.08   79.73   82.58   82.23   81.86
   81.86   81.72   81.61   78.73    76.7    77.1    76.9    75.5    76.8      78
      78    78.9    78.9    78.8    79.8    81.3
   726.7   886.7   916.7   936.7   956.7  1066.7  1466.7  1546.7  1656.7  2066.7
  2166.7  2456.7  2526.7  2686.7  2796.7  2976.7  3366.7  3506.7    3509  3566.7
  3826.7  4036.7  4252.5  4592.5 4792.25 4848.67 4889.39  4889.5  4922.9 4934.48
 4943.94 4953.41  4953.5  5006.7 5048.76 5048.87 5055.15 5064.88 5112.84  5140.6
 5140.71 5151.15 5203.93 5249.43  5331.2  5437.8  5477.8  5527.8  5807.8  5837.8
  5885.3  6335.3  6985.3  7105.3  7445.3  7727.5
    82.2    80.6      80    75.1    79.5    81.1      80    79.6    79.9    78.6
    78.2    78.4    78.6    78.3    80.1    79.1    77.9    77.7   77.94   77.81
   78.01   78.01   77.25   77.11   76.46   79.13   79.89   81.85   82.64   82.84
      83   83.13   83.13   83.59   83.48   83.48   83.45    83.3   82.58   82.13
   81.87   81.73   81.62   78.74   76.71   77.11   76.91    76.6   76.81   78.01
   78.01   78.91    78.9    78.8    79.8    81.3
   82.14   80.54   79.94   75.04   79.44   81.04   79.94   79.54   79.84   78.54
   78.14   78.34   78.54   78.24   80.04   79.04   77.84   77.64   77.64   77.74
   77.94   77.94   77.14   77.04   76.39   79.06   79.82   79.83   80.43   80.64
   79.74   77.01    77.7   78.16   78.05   77.02   79.67   82.52   82.17    81.8
    81.8   81.66   81.55   78.67   76.64   77.04   76.84   75.44   76.74   77.94
   77.94   78.84   78.84   78.74   79.74   81.24
Pier Skew, UpSta & Num, DnSta & Num=  ,4984.9, 2 ,4984.9, 2 , 0 , 0 , 0 ,,
       2       2
   65.21   79.04
       2       2
   65.15   78.98
Pier Skew, UpSta & Num, DnSta & Num=  ,5017.5, 2 ,5017.5, 2 , 0 , 0 , 0 ,,
       2       2
   65.65    79.2
       2       2
   65.59   79.14
Abutment Skew #Up #Dn= , 2 , 2
  4953.3  4954.5
   77.76   76.73
  4953.3  4954.5
    77.7   76.67
Abutment Skew #Up #Dn= , 2 , 2
 5046.77 5048.96
   76.19   78.11
 5046.77 5048.96
   76.13   78.05
BR Coef= 1 , 1 , 0 ,1.25, 0 ,,,.8,0,2,0,
WSPro=,,,, 1 ,,,, 0 ,,,, 0 ,,,,-1 ,-1 ,-1 , 0 , 0 , 0 , 0 , 0
BR U #Sta/Elev= 93
   726.7    82.2   886.7    80.6   916.7      80   936.7    75.1   956.7    79.5
  1066.7    81.1  1466.7      80  1546.7    79.6  1656.7    79.9  1951.5   78.97
  2066.7    78.6  2166.7    78.2  2456.7    78.4  2526.7    78.6  2686.7    78.3
  2783.7   79.89  2796.7    80.1  2976.7    79.1  3166.7    78.5  3366.7    77.9
  3506.7    77.7    3509    77.7  3566.7    77.8    3679   77.89    3689   77.89
  3826.7      78    3899      78    3969      78    4009      78  4036.7      78
    4229   77.29  4252.5    77.2  4352.5    77.2    4429   77.17    4439   77.16
  4592.5    77.1  4774.6   76.51 4792.25   76.45  4835.4   78.49 4848.67   79.12
  4872.2   79.56 4883.07   79.77 4889.39   79.88  4889.5   79.89 4889.61   79.89
  4922.9   80.49 4934.48    80.7 4943.94    79.8  4948.9   78.37 4953.41   77.07
  4953.5   77.04  4954.4   76.78  4954.5   76.73 4971.88   68.75 4984.89   66.35
 4993.45   65.16  5006.7   66.02 5028.12   67.41 5046.67   76.15 5046.77   76.19
 5048.76   77.03 5048.87   77.08  5053.7   79.12 5055.15   79.73 5064.88   82.58
 5112.84   82.23  5126.4   82.05 5140.49   81.86  5140.6   81.86 5140.71   81.86
 5151.15   81.72 5203.93   81.61  5224.8   80.29 5249.43   78.73  5271.9   78.17
  5331.2    76.7  5437.8    77.1  5477.8    76.9  5527.8    75.5  5807.8    76.8
  5837.8      78  5885.3      78  6183.6    78.6  6303.6   78.84  6335.3    78.9
  6783.6    78.9  6793.6    78.9  6813.6    78.9  6836.6    78.9  6985.3    78.9
  7105.3    78.8  7445.3    79.8  7727.5    81.3
BR U #Mann= 7
   726.7      .2   726.7      .1  1951.5     .14  2783.7      .1 4943.94    .035
 5055.15      .1  7727.5      .2
BR U Banks=4943.94,5055.15
BR D #Sta/Elev= 93
   726.7   82.14   886.7   80.54   916.7   79.94   936.7   75.04   956.7   79.44
  1066.7   81.04  1466.7   79.94  1546.7   79.54  1656.7   79.84  1951.5   78.91
  2066.7   78.54  2166.7   78.14  2456.7   78.34  2526.7   78.54  2686.7   78.24
  2783.7   79.83  2796.7   80.04  2976.7   79.04  3166.7   78.44  3366.7   77.84
  3506.7   77.64    3509   77.64  3566.7   77.74    3679   77.83    3689   77.83
  3826.7   77.94    3899   77.94    3969   77.94    4009   77.94  4036.7   77.94
    4229   77.23  4252.5   77.14  4352.5   77.14    4429   77.11    4439    77.1
  4592.5   77.04  4774.6   76.45 4792.25   76.39  4835.4   78.43 4848.67   79.06
  4872.2    79.5 4883.07   79.71 4889.39   79.82  4889.5   79.83 4889.61   79.83
  4922.9   80.43 4934.48   80.64 4943.94   79.74  4948.9   78.31 4953.41   77.01
  4953.5   76.98  4954.4   76.72  4954.5   76.67 4971.88   68.69 4984.89   66.29
 4993.45    65.1  5006.7   65.96 5028.12   67.35 5046.67   76.09 5046.77   76.13
 5048.76   76.97 5048.87   77.02  5053.7   79.06 5055.15   79.67 5064.88   82.52
 5112.84   82.17  5126.4   81.99 5140.49    81.8  5140.6    81.8 5140.71    81.8
 5151.15   81.66 5203.93   81.55  5224.8   80.23 5249.43   78.67  5271.9   78.11
  5331.2   76.64  5437.8   77.04  5477.8   76.84  5527.8   75.44  5807.8   76.74
  5837.8   77.94  5885.3   77.94  6183.6   78.54  6303.6   78.78  6335.3   78.84
  6783.6   78.84  6793.6   78.84  6813.6   78.84  6836.6   78.84  6985.3   78.84
  7105.3   78.74  7445.3   79.74  7727.5   81.24
BR D #Mann= 7
   726.7      .2   726.7      .1  1951.5     .14  2783.7      .1 4943.94    .035
 5055.15      .1  7727.5      .2
BR D Banks=4943.94,5055.15
BC Design=,, 0 ,, 0 ,,,,,,