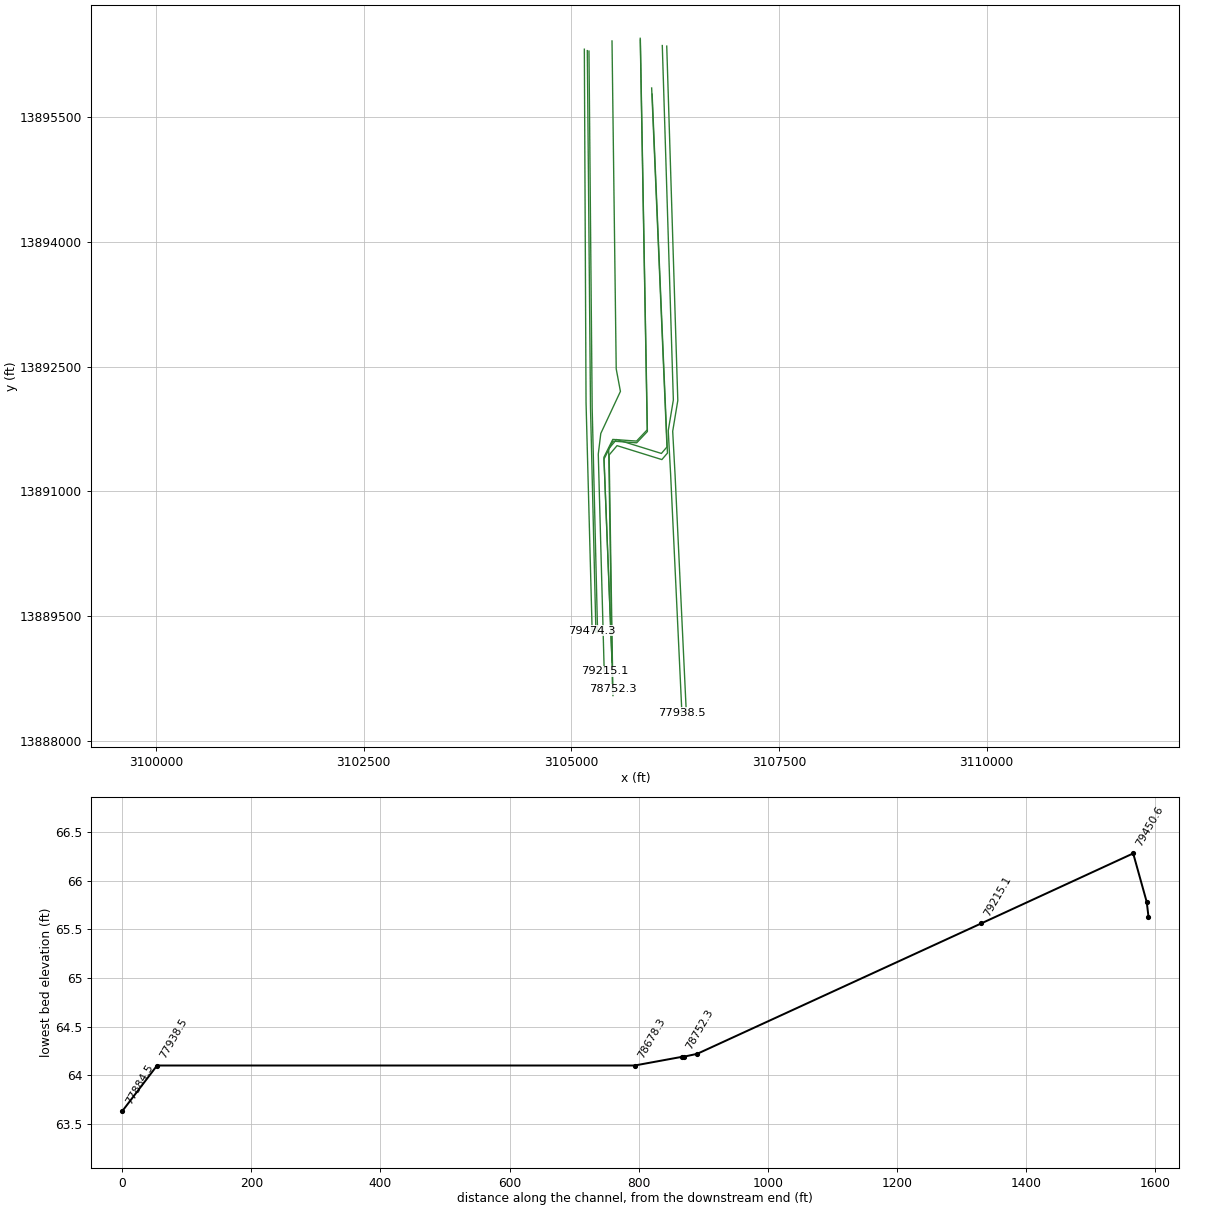
HEC-RAS study P118-00-00.PRJ: P118-00-00

--- P118-00-00.g01 (geometry) --- (continued)

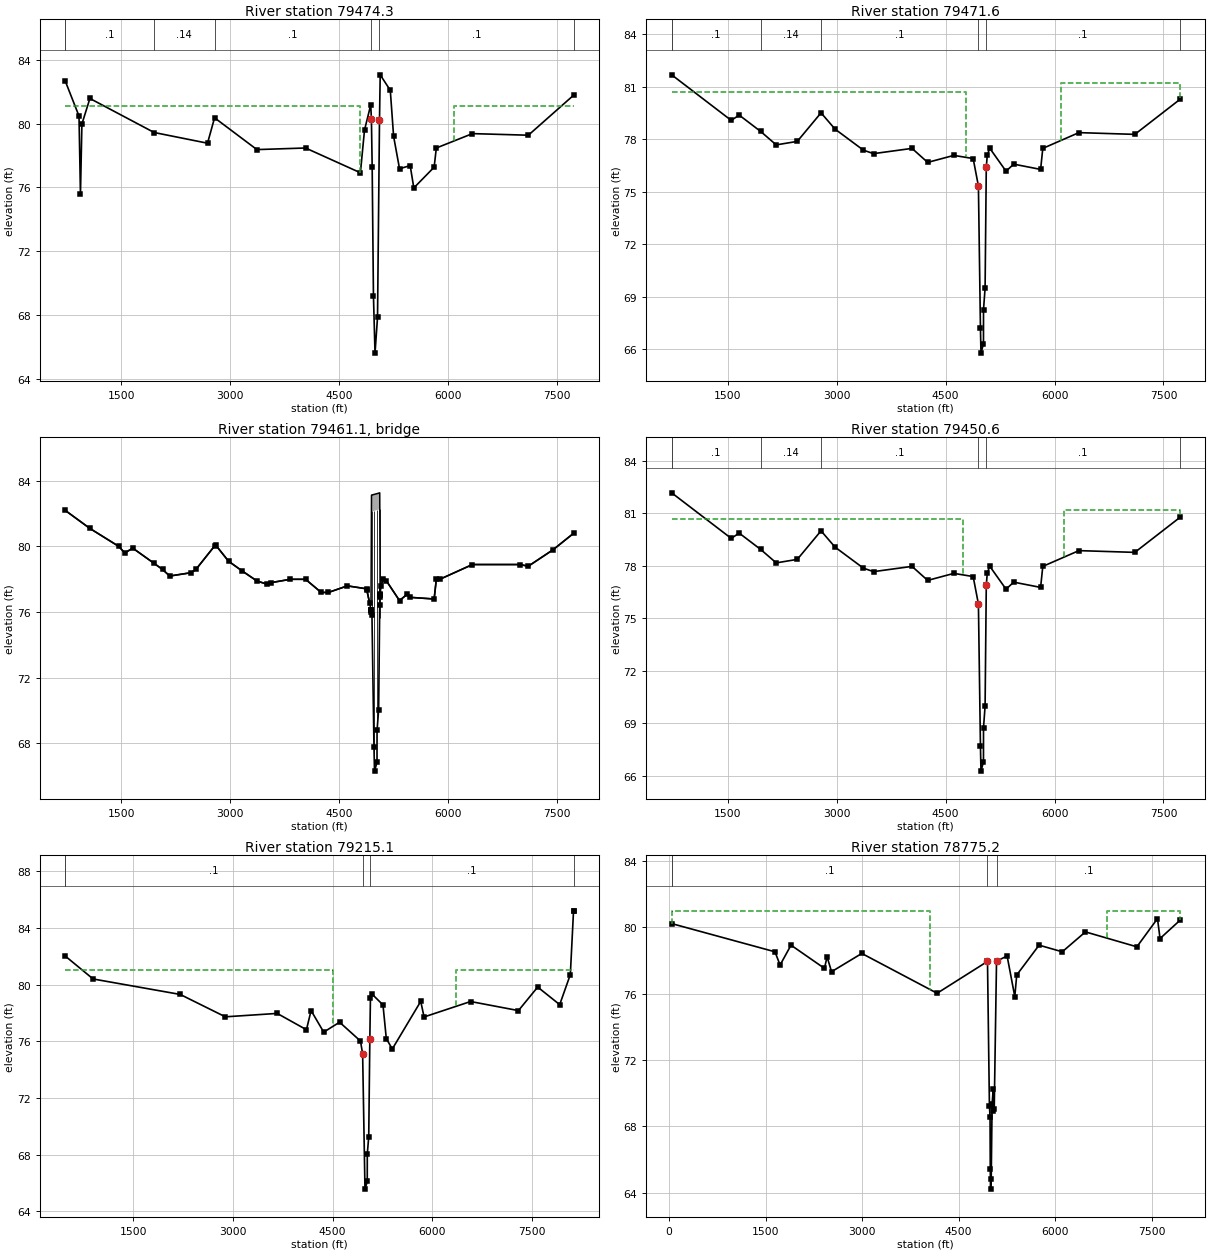
Type RM Length L Ch R = 1 ,79474.3 ,2.7,2.7,2.7
BEGIN DESCRIPTION:
Downstream Section of Bridge/Culvert/Weir
END DESCRIPTION:
XS GIS Cut Line= 3
      3105157.81     13896320.83      3105178.29     13892065.57
      3105251.74     13889321.06
#Sta/Elev= 30
   726.7   82.67   916.7   80.47   936.7   75.57   956.7   79.97  1066.7   81.57
  1951.5   79.44  2686.7   78.77  2783.7   80.36  3366.7   78.37  4036.7   78.47
 4792.25   76.92 4848.67   79.59 4934.48   81.17 4943.94   80.27  4954.4   77.25
 4971.88   69.22 4993.45   65.63 5028.12   67.88 5055.15    80.2 5064.88   83.05
 5203.93   82.08 5249.43    79.2  5331.2   77.17  5477.8   77.37  5527.8   75.97
  5807.8   77.27  5837.8   78.47  6335.3   79.37  7105.3   79.27  7727.5   81.77
#Mann= 7 , 1 , 0
   726.7      .2       0   726.7      .1       0  1951.5     .14       0
  2783.7      .1       0 4943.94    .035       0 5055.15      .1       0
  7727.5      .2       0
#XS Ineff= 2 , 0
       0    4786    81.1    6080       0    81.1
Permanent Ineff=
       F       F
Bank Sta=4943.94,5055.15
XS Rating Curve= 0
Exp/Cntr=.5,.3

Type RM Length L Ch R = 1 ,79471.6 ,21,21,21
BEGIN DESCRIPTION:
Upstream Section of Bridge/Culvert/Weir
END DESCRIPTION:
XS GIS Cut Line= 3
       3105193.4      13896304.1      3105231.97     13892006.56
      3105297.19     13889304.26
#Sta/Elev= 30
   726.7   81.67  1546.7   79.07  1656.7   79.37  1951.5   78.44  2166.7   77.67
  2456.7   77.87  2783.7    79.5  2976.7   78.57  3366.7   77.37  3506.7   77.17
  4036.7   77.47  4252.5   76.67  4612.5   77.07 4878.92   76.89 4951.22   75.32
 4979.12   67.23 4986.52   65.78 5020.92   66.32 5021.42   68.26 5043.12   69.49
 5059.62   76.39 5073.02   77.08 5107.22   77.48  5331.2   76.17  5437.8   76.57
  5807.8   76.27  5837.8   77.47  6335.3   78.37  7105.3   78.27  7727.5   80.27
#Mann= 7 , 1 , 0
   726.7      .2       0   726.7      .1       0  1951.5     .14       0
  2783.7      .1       0 4951.22    .035       0 5059.62      .1       0
  7727.5      .2       0
#XS Ineff= 2 , 0
       0    4780    80.7    6086       0    81.2
Permanent Ineff=
       F       F
Bank Sta=4951.22,5059.62
XS Rating Curve= 0
Exp/Cntr=.5,.3

Type RM Length L Ch R = 3 ,79461.1 ,,,
BEGIN DESCRIPTION:
12" PIPELINE
END DESCRIPTION:
Bridge Culvert--1,0,-1,-1, 0
Deck Dist Width WeirC Skew NumUp NumDn MinLoCord MaxHiCord MaxSubmerge Is_Ogee
10,1,2.6,0, 54, 54, , , .95, 0, 1,1,,
   726.7  1066.7  1466.7  1546.7  1656.7  1951.5  2066.7  2166.7  2456.7  2526.7
  2783.7  2796.7  2976.7  3166.7  3366.7  3506.7  3566.7  3826.7  4036.7  4252.5
  4352.5  4612.5 4878.92 4881.42 4920.32 4938.62 4938.73 4938.82 4945.02 4951.22
 4979.12 4986.52 5020.92 5021.42 5043.12 5058.42 5059.62 5062.51 5062.62 5062.72
 5073.02 5107.22  5151.2  5331.2  5437.8  5477.8  5807.8  5837.8  5885.3  6335.3
  6985.3  7105.3  7445.3  7727.5
    82.2    81.1      80    79.6    79.9   78.97    78.6    78.2    78.4    78.6
   80.03    80.1    79.1    78.5    77.9    77.7    77.8      78      78    77.2
    77.2    77.6   77.42   77.33   76.53   76.63   76.74   76.83   83.13   83.14
   83.17   83.18   83.22   83.22   83.25   83.27   81.95   78.78   78.66   77.08
   77.61   78.01    77.9    76.7    77.1    76.9    76.8      78      78    78.9
    78.9    78.8    79.8    80.8
    82.2    81.1      80    79.6    79.9   78.97    78.6    78.2    78.4    78.6
   80.03    80.1    79.1    78.5    77.9    77.7    77.8      78      78    77.2
    77.2    77.6   77.42   77.33   76.53   76.13   76.12   76.12   82.13   82.14
   82.17   82.18   82.22   82.22   82.25   82.27   80.95   77.78   77.07   77.08
   77.61   78.01    77.9    76.7    77.1    76.9    76.8      78      78    78.9
    78.9    78.8    79.8    80.8
   726.7  1066.7  1466.7  1546.7  1656.7  1951.5  2066.7  2166.7  2456.7  2526.7
  2783.7  2796.7  2976.7  3166.7  3366.7  3506.7  3566.7  3826.7  4036.7  4252.5
  4352.5  4612.5 4878.92 4881.42 4920.32 4938.62 4938.73 4938.82 4945.02 4951.22
 4979.12 4986.52 5020.92 5021.42 5043.12 5058.42 5059.62 5062.51 5062.62 5062.72
 5073.02 5107.22  5151.2  5331.2  5437.8  5477.8  5807.8  5837.8  5885.3  6335.3
  6985.3  7105.3  7445.3  7727.5
    82.2    81.1      80    79.6    79.9   78.97    78.6    78.2    78.4    78.6
   80.03    80.1    79.1    78.5    77.9    77.7    77.8      78      78    77.2
    77.2    77.6   77.42   77.33   76.53   76.63   76.74   76.83   83.13   83.14
   83.17   83.18   83.22   83.22   83.25   83.27   81.95   78.78   78.66   77.08
   77.61   78.01    77.9    76.7    77.1    76.9    76.8      78      78    78.9
    78.9    78.8    79.8    80.8
    82.2    81.1      80    79.6    79.9   78.97    78.6    78.2    78.4    78.6
   80.03    80.1    79.1    78.5    77.9    77.7    77.8      78      78    77.2
    77.2    77.6   77.42   77.33   76.53   76.13   76.12   76.12   82.13   82.14
   82.17   82.18   82.22   82.22   82.25   82.27   80.95   77.78   77.07   77.08
   77.61   78.01    77.9    76.7    77.1    76.9    76.8      78      78    78.9
    78.9    78.8    79.8    80.8
Pier Skew, UpSta & Num, DnSta & Num=  ,4951.8, 2 ,4951.8, 2 , 0 , 0 , 0 ,,
     1.5     1.5
   74.46   83.14
     1.5     1.5
   74.46   83.14
Pier Skew, UpSta & Num, DnSta & Num=  ,4985.4, 2 ,4985.4, 2 , 0 , 0 , 0 ,,
     1.5     1.5
   65.38   83.18
     1.5     1.5
   65.38   83.18
Pier Skew, UpSta & Num, DnSta & Num=  ,5021.5, 2 ,5021.5, 2 , 0 , 0 , 0 ,,
     1.5     1.5
   65.85   83.22
     1.5     1.5
   65.85   83.22
Pier Skew, UpSta & Num, DnSta & Num=  ,5056.5, 2 ,5056.5, 2 , 0 , 0 , 0 ,,
     1.5     1.5
   74.31   83.27
     1.5     1.5
   74.31   83.27
BR Coef= 1 , 1 , 0 ,1.25, 0 ,,,.8,0,2,0,
WSPro=,,,, 1 ,,,, 0 ,,,, 0 ,,,,-1 ,-1 ,-1 , 0 , 0 , 0 , 0 , 0
BR U #Sta/Elev= 54
   726.7    82.2  1066.7    81.1  1466.7      80  1546.7    79.6  1656.7    79.9
  1951.5   78.97  2066.7    78.6  2166.7    78.2  2456.7    78.4  2526.7    78.6
  2783.7   80.03  2796.7    80.1  2976.7    79.1  3166.7    78.5  3366.7    77.9
  3506.7    77.7  3566.7    77.8  3826.7      78  4036.7      78  4252.5    77.2
  4352.5    77.2  4612.5    77.6 4878.92   77.42 4881.42   77.33 4920.32   76.53
 4938.62   76.13 4938.73   76.12 4938.82   76.12 4945.02   75.99 4951.22   75.85
 4979.12   67.76 4986.52   66.31 5020.92   66.85 5021.42   68.79 5043.12   70.02
 5058.42   76.42 5059.62   76.92 5062.51   77.07 5062.62   77.07 5062.72   77.08
 5073.02   77.61 5107.22   78.01  5151.2    77.9  5331.2    76.7  5437.8    77.1
  5477.8    76.9  5807.8    76.8  5837.8      78  5885.3      78  6335.3    78.9
  6985.3    78.9  7105.3    78.8  7445.3    79.8  7727.5    80.8
BR U #Mann= 7
   726.7      .2   726.7      .1  1951.5     .14  2783.7      .1 4951.22    .045
 5059.62      .1  7727.5      .2
BR U Banks=4951.22,5059.62
BR D #Sta/Elev= 54
   726.7    82.2  1066.7    81.1  1466.7      80  1546.7    79.6  1656.7    79.9
  1951.5   78.97  2066.7    78.6  2166.7    78.2  2456.7    78.4  2526.7    78.6
  2783.7   80.03  2796.7    80.1  2976.7    79.1  3166.7    78.5  3366.7    77.9
  3506.7    77.7  3566.7    77.8  3826.7      78  4036.7      78  4252.5    77.2
  4352.5    77.2  4612.5    77.6 4878.92   77.42 4881.42   77.33 4920.32   76.53
 4938.62   76.13 4938.73   76.12 4938.82   76.12 4945.02   75.99 4951.22   75.85
 4979.12   67.76 4986.52   66.31 5020.92   66.85 5021.42   68.79 5043.12   70.02
 5058.42   76.42 5059.62   76.92 5062.51   77.07 5062.62   77.07 5062.72   77.08
 5073.02   77.61 5107.22   78.01  5151.2    77.9  5331.2    76.7  5437.8    77.1
  5477.8    76.9  5807.8    76.8  5837.8      78  5885.3      78  6335.3    78.9
  6985.3    78.9  7105.3    78.8  7445.3    79.8  7727.5    80.8
BR D #Mann= 7
   726.7      .2   726.7      .1  1951.5     .14  2783.7      .1 4951.22    .045
 5059.62      .1  7727.5      .2
BR D Banks=4951.22,5059.62
BC Design=,, 0 ,, 0 ,,,,,,

Type RM Length L Ch R = 1 ,79450.6 ,235.5,235.5,235.5
BEGIN DESCRIPTION:
Downstream Section of Bridge/Culvert/Weir
END DESCRIPTION:
XS GIS Cut Line= 3
      3105213.52     13896298.09      3105252.09     13892000.54
      3105317.31     13889298.25
#Sta/Elev= 30
   726.7   82.17  1546.7   79.57  1656.7   79.87  1951.5   78.94  2166.7   78.17
  2456.7   78.37  2783.7      80  2976.7   79.07  3366.7   77.87  3506.7   77.67
  4036.7   77.97  4252.5   77.17  4612.5   77.57 4878.92   77.39 4951.22   75.82
 4979.12   67.73 4986.52   66.28 5020.92   66.82 5021.42   68.76 5043.12   69.99
 5059.62   76.89 5073.02   77.58 5107.22   77.98  5331.2   76.67  5437.8   77.07
  5807.8   76.77  5837.8   77.97  6335.3   78.87  7105.3   78.77  7727.5   80.77
#Mann= 7 , 1 , 0
   726.7      .2       0   726.7      .1       0  1951.5     .14       0
  2783.7      .1       0 4951.22    .035       0 5059.62      .1       0
  7727.5      .2       0
#XS Ineff= 2 , 0
       0    4738    80.7    6128       0    81.2
Permanent Ineff=
       F       F
Bank Sta=4951.22,5059.62
XS Rating Curve= 0
Exp/Cntr=.5,.3

Type RM Length L Ch R = 1 ,79215.1 ,478.3,439.9,68.9
BEGIN DESCRIPTION:
Cross Section 79215.1-Interpolated
END DESCRIPTION:
XS GIS Cut Line= 6
      3105490.86     13896420.39      3105541.48     13892472.05
       3105592.1     13892202.08      3105355.88     13891695.88
      3105325.52     13891447.38      3105396.97     13888831.35
#Sta/Elev= 30
   475.6   82.01   895.6   80.39  2205.6    79.3  2885.6   77.72  3665.6   77.96
  4105.6   76.81  4175.6   78.16  4365.6   76.64  4604.3   77.34  4918.9   76.01
 4951.22    75.1 4986.52   65.56 5020.92    66.1 5021.42   68.04 5043.12   69.27
 5059.62   76.17  5068.9   79.08  5088.9   79.34  5257.5   78.56  5307.5   76.18
  5397.5   75.45  5825.7   78.81  5875.7   77.71  6575.7    78.8  7295.7   78.16
  7585.7   79.82  7916.7   78.58  8076.7    80.7  8124.8   85.19  8124.9    85.2
#Mann= 5 , 1 , 0
   475.6      .2       0   475.6      .1       0 4951.22    .035       0
 5059.62      .1       0  8124.8      .2       0
#XS Ineff= 2 , 0
       0    4506      81    6360       0      81
Permanent Ineff=
       F       F
Bank Sta=4951.22,5059.62
XS Rating Curve= 0
Exp/Cntr=.5,.3

Type RM Length L Ch R = 1 ,78775.2 ,21,21,21
BEGIN DESCRIPTION:
Upstream Section of Bridge/Culvert/Weir
END DESCRIPTION:
XS GIS Cut Line= 6
      3105830.49     13896451.79      3105914.97     13891740.13
      3105786.16     13891604.13      3105500.26     13891624.24
      3105393.12     13891409.19      3105490.06     13888961.92
#Sta/Elev= 30
    41.7   80.23  1646.7   78.53  1725.9   77.73  1895.9   78.93  2415.9   77.53
  2455.9   78.23  2525.9   77.33  2995.9   78.43  4165.9   76.03 4948.74   77.95
 4978.64   69.26 4988.54   68.55 4991.84   65.44 4995.94   64.22 5006.74   64.85
 5020.04   69.33 5037.64   70.23 5038.94   68.96 5053.44   69.07 5089.04   77.96
 5253.44   78.28  5372.9   75.83  5402.9   77.13  5750.4   78.93  6110.4   78.53
  6470.4   79.73  7269.8   78.83  7589.8   80.53  7629.8   79.33  7939.8   80.43
#Mann= 4 , 1 , 0
    41.7      .2       0    41.7      .1       0 4948.74    .035       0
 5089.04      .1       0
#XS Ineff= 2 , 0
       0    4056      81    6810       0      81
Permanent Ineff=
       F       F
Bank Sta=4948.74,5089.04
XS Rating Curve= 0
Exp/Cntr=.5,.3

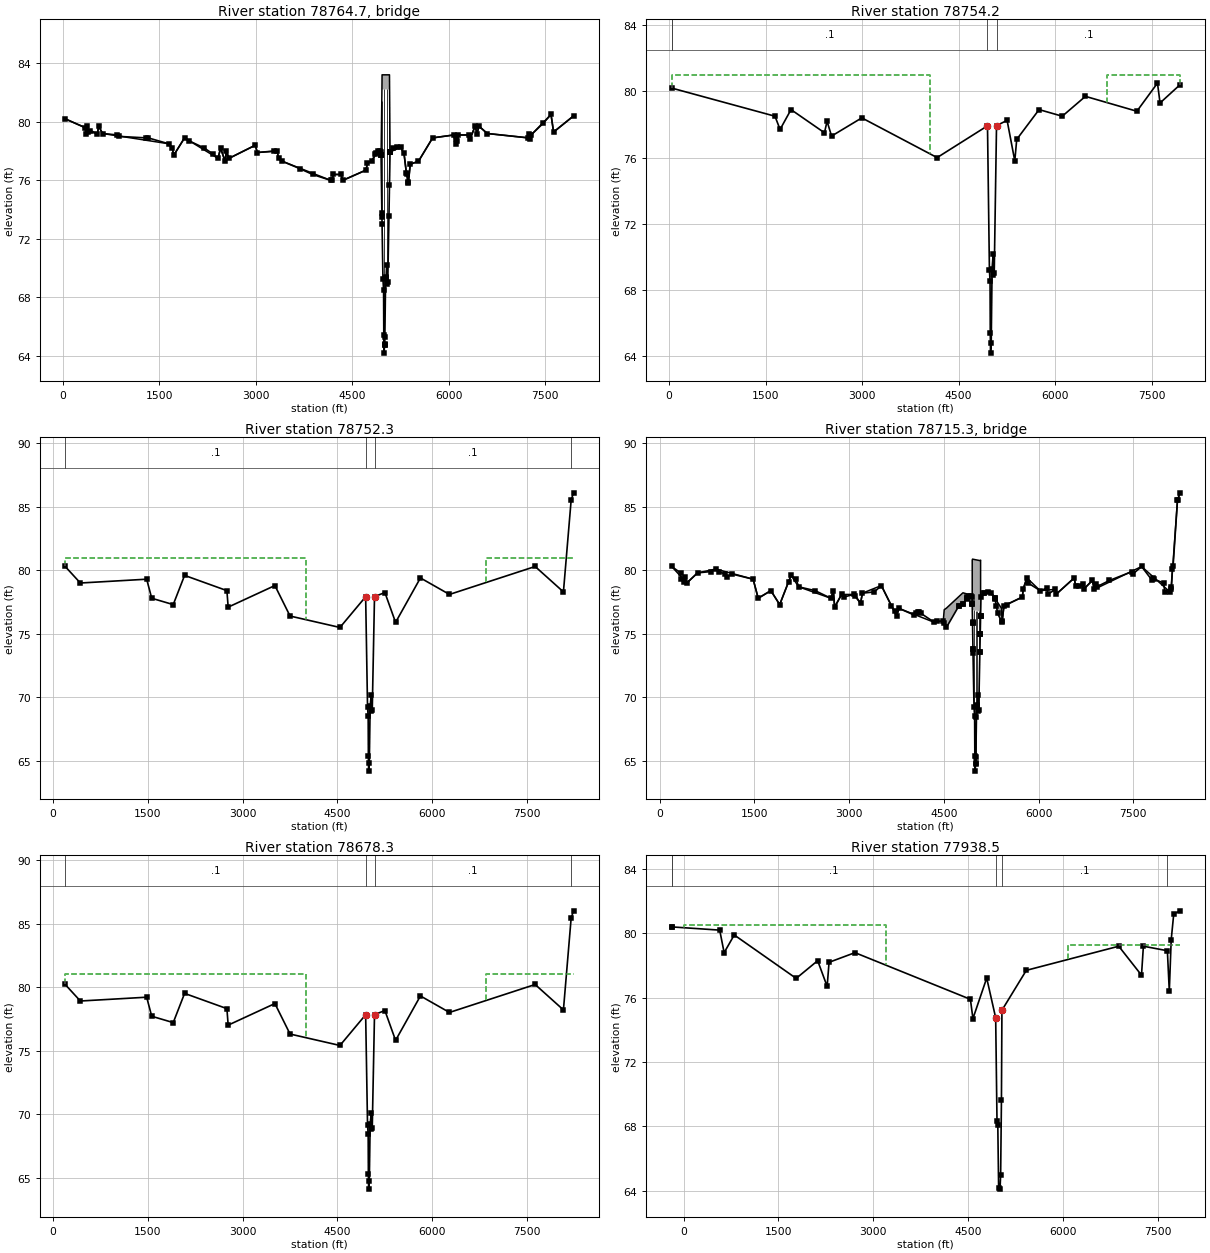
Type RM Length L Ch R = 3 ,78764.7 ,,,
BEGIN DESCRIPTION:
12" PIPELINE
END DESCRIPTION:
Bridge Culvert--1,0,-1,-1, 0
Deck Dist Width WeirC Skew NumUp NumDn MinLoCord MaxHiCord MaxSubmerge Is_Ogee
10,1,2.6,0, 60, 60, , , .95, 0, 1,1,,
    41.7   351.7   361.7   381.7   401.7   541.7   561.7   621.7  1646.7  1705.9
  1725.9  1895.9  2415.9  2455.9  2525.9  2545.9  2585.9  2995.9  3025.9  3335.9
  3355.9  3415.9  4165.9  4185.9  4205.9  4325.9  4355.9  4715.9 4738.44 4803.44
 4903.64 4948.74 4949.44 4961.74 4964.84 5080.14 5089.04 5253.44 5305.74  5342.9
  5372.9  5402.9  5530.4  5750.4  6080.4  6110.4  6150.4  6320.4  6330.4  6410.4
  6440.4  6470.4  6599.8  7239.8  7249.8  7269.8  7279.8  7589.8  7629.8  7939.8
    80.2    79.6    79.2    79.7    79.3    79.2    79.7    79.2    78.5    78.2
    77.7    78.9    77.5    78.2    77.3      78    77.5    78.4    77.9      78
    77.5    77.3      76      76    76.4    76.4      76    76.7   77.19   77.31
   78.01   77.92   77.71   81.77   83.21   83.21   77.94   78.25   77.84    76.5
    75.8    77.1    77.3    78.9    79.1    78.5    79.1    79.1    78.8    79.7
    79.2    79.7    79.2    78.9    79.2    78.8    79.1    80.5    79.3    80.4
    80.2    79.6    79.2    79.7    79.3    79.2    79.7    79.2    78.5    78.2
    77.7    78.9    77.5    78.2    77.3      78    77.5    78.4    77.9      78
    77.5    77.3      76      76    76.4    76.4      76    76.7   77.19   77.31
   78.01   77.92    77.7   80.77   82.21   82.21   77.93   78.25   77.84    76.5
    75.8    77.1    77.3    78.9    79.1    78.5    79.1    79.1    78.8    79.7
    79.2    79.7    79.2    78.9    79.2    78.8    79.1    80.5    79.3    80.4
    41.7   351.7   361.7   381.7   401.7   541.7   561.7   621.7  1646.7  1705.9
  1725.9  1895.9  2415.9  2455.9  2525.9  2545.9  2585.9  2995.9  3025.9  3335.9
  3355.9  3415.9  4165.9  4185.9  4205.9  4325.9  4355.9  4715.9 4738.44 4803.44
 4903.64 4948.74 4949.44 4961.74 4964.84 5080.14 5089.04 5253.44 5305.74  5342.9
  5372.9  5402.9  5530.4  5750.4  6080.4  6110.4  6150.4  6320.4  6330.4  6410.4
  6440.4  6470.4  6599.8  7239.8  7249.8  7269.8  7279.8  7589.8  7629.8  7939.8
    80.2    79.6    79.2    79.7    79.3    79.2    79.7    79.2    78.5    78.2
    77.7    78.9    77.5    78.2    77.3      78    77.5    78.4    77.9      78
    77.5    77.3      76      76    76.4    76.4      76    76.7   77.19   77.31
   78.01   77.92   77.71   81.77   83.21   83.21   77.94   78.25   77.84    76.5
    75.8    77.1    77.3    78.9    79.1    78.5    79.1    79.1    78.8    79.7
    79.2    79.7    79.2    78.9    79.2    78.8    79.1    80.5    79.3    80.4
    80.2    79.6    79.2    79.7    79.3    79.2    79.7    79.2    78.5    78.2
    77.7    78.9    77.5    78.2    77.3      78    77.5    78.4    77.9      78
    77.5    77.3      76      76    76.4    76.4      76    76.7   77.19   77.31
   78.01   77.92    77.7   80.77   82.21   82.21   77.93   78.25   77.84    76.5
    75.8    77.1    77.3    78.9    79.1    78.5    79.1    79.1    78.8    79.7
    79.2    79.7    79.2    78.9    79.2    78.8    79.1    80.5    79.3    80.4
Pier Skew, UpSta & Num, DnSta & Num=  ,4963.1, 2 ,4963.1, 2 , 0 , 0 , 0 ,,
     1.5     1.5
   72.27   82.77
     1.5     1.5
   72.27   82.77
Pier Skew, UpSta & Num, DnSta & Num=  ,4998.2, 2 ,4998.2, 2 , 0 , 0 , 0 ,,
     1.5     1.5
    63.3   83.21
     1.5     1.5
    63.3   83.21
Pier Skew, UpSta & Num, DnSta & Num=  ,5037.6, 2 ,5037.6, 2 , 0 , 0 , 0 ,,
     1.6     1.6
   68.42   83.21
     1.6     1.6
   68.42   83.21
Pier Skew, UpSta & Num, DnSta & Num=  ,5075.4, 2 ,5075.4, 2 , 0 , 0 , 0 ,,
     1.5     1.5
   73.27   83.21
     1.5     1.5
   73.27   83.21
BR Coef= 1 , 1 , 0 ,1.25, 0 ,,,.8,0,2,0,
WSPro=,,,, 1 ,,,, 0 ,,,, 0 ,,,,-1 ,-1 ,-1 , 0 , 0 , 0 , 0 , 0
BR U #Sta/Elev= 101
    41.7    80.2   351.7    79.6   361.7    79.2   381.7    79.7   401.7    79.3
   431.7    79.4   541.7    79.2   561.7    79.7   621.7    79.2   851.7    79.1
   881.7      79  1301.7    78.9  1331.7    78.9  1646.7    78.5  1705.9    78.2
  1725.9    77.7  1895.9    78.9  1965.9    78.7  2205.9    78.2  2335.9    77.8
  2415.9    77.5  2455.9    78.2  2525.9    77.3  2545.9      78  2585.9    77.5
  2995.9    78.4  3025.9    77.9  3285.9      78  3335.9      78  3355.9    77.5
  3415.9    77.3  3685.9    76.8  3885.9    76.4  4165.9      76  4185.9      76
  4205.9    76.4  4325.9    76.4  4355.9      76  4715.9    76.7 4738.44   77.19
 4803.44   77.31 4859.84   77.78 4870.64   77.87 4903.64   78.01 4925.04   78.01
 4948.74   77.92 4949.24   77.76 4949.35   77.73 4949.44    77.7 4961.74   73.77
 4963.14   73.48 4964.84   73.01 4978.64   69.23 4988.54   68.52 4991.84   65.41
 4995.94   64.19 5003.44   64.72 5003.54   64.73 5006.74   64.82 5008.14   65.31
 5020.04    69.3 5028.54   69.38 5037.64    70.2 5038.94   68.93 5053.44   69.04
 5071.84   73.55 5080.14   75.66 5089.04   77.93 5089.83   77.93 5089.94   77.93
 5090.04   77.94 5141.94    78.2 5197.64   78.27 5253.44   78.25 5305.74   77.84
  5342.9    76.5  5352.9    76.4  5362.9    75.9  5372.9    75.8  5402.9    77.1
  5530.4    77.3  5750.4    78.9  6080.4    79.1  6110.4    78.5  6120.4    78.8
  6130.4    78.7  6150.4    79.1  6320.4    79.1  6330.4    78.8  6410.4    79.7
  6440.4    79.2  6470.4    79.7  6599.8    79.2  7239.8    78.9  7249.8    79.2
  7269.8    78.8  7279.8    79.1  7469.8    79.9  7589.8    80.5  7629.8    79.3
  7939.8    80.4
BR U #Mann= 4
    41.7      .2    41.7      .1 4948.74    .045 5089.04      .1
BR U Banks=4948.74,5089.04
BR D #Sta/Elev= 101
    41.7    80.2   351.7    79.6   361.7    79.2   381.7    79.7   401.7    79.3
   431.7    79.4   541.7    79.2   561.7    79.7   621.7    79.2   851.7    79.1
   881.7      79  1301.7    78.9  1331.7    78.9  1646.7    78.5  1705.9    78.2
  1725.9    77.7  1895.9    78.9  1965.9    78.7  2205.9    78.2  2335.9    77.8
  2415.9    77.5  2455.9    78.2  2525.9    77.3  2545.9      78  2585.9    77.5
  2995.9    78.4  3025.9    77.9  3285.9      78  3335.9      78  3355.9    77.5
  3415.9    77.3  3685.9    76.8  3885.9    76.4  4165.9      76  4185.9      76
  4205.9    76.4  4325.9    76.4  4355.9      76  4715.9    76.7 4738.44   77.19
 4803.44   77.31 4859.84   77.78 4870.64   77.87 4903.64   78.01 4925.04   78.01
 4948.74   77.92 4949.24   77.76 4949.35   77.73 4949.44    77.7 4961.74   73.77
 4963.14   73.48 4964.84   73.01 4978.64   69.23 4988.54   68.52 4991.84   65.41
 4995.94   64.19 5003.44   64.72 5003.54   64.73 5006.74   64.82 5008.14   65.31
 5020.04    69.3 5028.54   69.38 5037.64    70.2 5038.94   68.93 5053.44   69.04
 5071.84   73.55 5080.14   75.66 5089.04   77.93 5089.83   77.93 5089.94   77.93
 5090.04   77.94 5141.94    78.2 5197.64   78.27 5253.44   78.25 5305.74   77.84
  5342.9    76.5  5352.9    76.4  5362.9    75.9  5372.9    75.8  5402.9    77.1
  5530.4    77.3  5750.4    78.9  6080.4    79.1  6110.4    78.5  6120.4    78.8
  6130.4    78.7  6150.4    79.1  6320.4    79.1  6330.4    78.8  6410.4    79.7
  6440.4    79.2  6470.4    79.7  6599.8    79.2  7239.8    78.9  7249.8    79.2
  7269.8    78.8  7279.8    79.1  7469.8    79.9  7589.8    80.5  7629.8    79.3
  7939.8    80.4
BR D #Mann= 4
    41.7      .2    41.7      .1 4948.74    .045 5089.04      .1
BR D Banks=4948.74,5089.04
BC Design=,, 0 ,, 0 ,,,,,,

Type RM Length L Ch R = 1 ,78754.2 ,1.9,1.9,1.9
BEGIN DESCRIPTION:
Downstream Section of Bridge/Culvert/Weir
END DESCRIPTION:
XS GIS Cut Line= 6
      3105832.14     13896430.86      3105916.61     13891719.19
       3105787.8     13891583.19       3105501.9      13891603.3
      3105394.76     13891388.25      3105491.71     13888940.98
#Sta/Elev= 30
    41.7    80.2  1646.7    78.5  1725.9    77.7  1895.9    78.9  2415.9    77.5
  2455.9    78.2  2525.9    77.3  2995.9    78.4  4165.9      76 4948.74   77.92
 4978.64   69.23 4988.54   68.52 4991.84   65.41 4995.94   64.19 5006.74   64.82
 5020.04    69.3 5037.64    70.2 5038.94   68.93 5053.44   69.04 5089.04   77.93
 5253.44   78.25  5372.9    75.8  5402.9    77.1  5750.4    78.9  6110.4    78.5
  6470.4    79.7  7269.8    78.8  7589.8    80.5  7629.8    79.3  7939.8    80.4
#Mann= 4 , 1 , 0
    41.7      .2       0    41.7      .1       0 4948.74    .035       0
 5089.04      .1       0
#XS Ineff= 2 , 0
       0    4056      81    6810       0      81
Permanent Ineff=
       F       F
Bank Sta=4948.74,5089.04
XS Rating Curve= 0
Exp/Cntr=.5,.3

Type RM Length L Ch R = 1 ,78752.3 ,74,74,74
BEGIN DESCRIPTION:
Upstream Section of Bridge/Culvert/Weir
END DESCRIPTION:
XS GIS Cut Line= 6
      3105967.99     13895854.01      3106152.35      13891533.5
      3106085.25     13891455.22      3105545.69     13891622.96
      3105450.63     13891511.14      3105496.45      13888614.7
#Sta/Elev= 30
     191    80.3     431      79    1481    79.3    1561    77.8  1901.6    77.3
  2081.6    79.6  2751.6    78.4  2771.6    77.1  3511.6    78.8  3751.6    76.4
  4541.6    75.5  4948.7   77.92  4978.6   69.23  4988.5   68.52  4991.8   65.41
  4995.9   64.19  5006.7   64.82    5020    69.3  5037.6    70.2  5038.9   68.93
  5053.4   69.04    5089   77.93  5253.4   78.25  5422.7    75.9    5816    79.4
    6276    78.1  7632.8    80.3  8080.7    78.3    8203   85.53  8240.7    86.1
#Mann= 4 , 1 , 0
     191      .1       0  4948.7    .035       0    5089      .1       0
    8203      .2       0
#XS Ineff= 2 , 0
       0    4006      81    6860       0      81
Permanent Ineff=
       F       F
Bank Sta=4948.7,5089
XS Rating Curve= 0
Exp/Cntr=.5,.3

Type RM Length L Ch R = 3 ,78715.3 ,,,
BEGIN DESCRIPTION:
WEST MOUNT HOUSTON ROAD
Structure ID: P18-35
END DESCRIPTION:
Bridge Culvert--1,0,-1,-1, 0
Deck Dist Width WeirC Skew NumUp NumDn MinLoCord MaxHiCord MaxSubmerge Is_Ogee
10,54,2.6,0, 60, 60, , , .95, 0, 1,1,,
     191     431     601     891    1481    1561  1761.6  1901.6  2081.6  2201.6
  2711.6  2751.6  2771.6  2881.6  3071.6  3181.6  3211.6  3511.6  3751.6  3791.6
  4351.6  4491.6  4506.9  4541.6  4803.2  4903.6  4948.7 4950.29  4950.4    4955
 4955.11  4955.2 5077.29  5077.4    5083 5083.11    5089  5197.6  5305.7  5352.7
  5414.9  5422.7  5452.7    5746    5756    5816    6026    6266    6276    6566
    6586  6702.8  6712.8  6852.8  6882.8  7632.8  8080.7  8100.7  8200.7  8240.7
    80.3      79    79.8    80.1    79.3    77.8    78.4    77.3    79.6    78.7
    77.8    78.4    77.1    78.1    78.1    77.4    78.2    78.8    76.4      77
    75.9      76    76.9   77.02   78.23   78.09   77.93    77.8    80.8   80.88
   80.88   80.88   80.76   80.76    80.8    77.8   77.94   78.28   77.94   77.47
      77    75.9    77.2    77.9    78.5    79.4    78.4    78.5    78.1    79.4
    78.8    78.9    78.5    79.2    78.5    80.3    78.3    78.5    85.5    86.1
    80.3      79    79.8    80.1    79.3    77.8    78.4    77.3    79.6    78.7
    77.8    78.4    77.1    78.1    78.1    77.4    78.2    78.8    76.4      77
    75.9      76   75.85    75.5   77.31   78.01   77.92   77.41   77.38   75.91
   75.87   76.88   76.76   74.99   76.41   76.44   77.93   78.27   77.84    76.6
   75.98    75.9    77.2    77.9    78.5    79.4    78.4    78.5    78.1    79.4
    78.8    78.9    78.5    79.2    78.5    80.3    78.3    78.5    85.5    86.1
     191     431     601     891    1481    1561  1761.6  1901.6  2081.6  2201.6
  2711.6  2751.6  2771.6  2881.6  3071.6  3181.6  3211.6  3511.6  3751.6  3791.6
  4351.6  4491.6  4506.9  4541.6  4803.2  4903.6  4948.7 4950.29  4950.4    4955
 4955.11  4955.2 5077.29  5077.4    5083 5083.11    5089  5197.6  5305.7  5352.7
  5414.9  5422.7  5452.7    5746    5756    5816    6026    6266    6276    6566
    6586  6702.8  6712.8  6852.8  6882.8  7632.8  8080.7  8100.7  8200.7  8240.7
    80.3      79    79.8    80.1    79.3    77.8    78.4    77.3    79.6    78.7
    77.8    78.4    77.1    78.1    78.1    77.4    78.2    78.8    76.4      77
    75.9      76    76.9   77.02   78.23   78.09   77.93    77.8    80.8   80.88
   80.88   80.88   80.76   80.76    80.8    77.8   77.94   78.28   77.94   77.47
      77    75.9    77.2    77.9    78.5    79.4    78.4    78.5    78.1    79.4
    78.8    78.9    78.5    79.2    78.5    80.3    78.3    78.5    85.5    86.1
   80.21   78.91   79.71   80.01   79.21   77.71   78.31   77.21   79.51   78.61
   77.71   78.31   77.01   78.01   78.01   77.31   78.11   78.71   76.31   76.91
   75.81   75.91   75.76   75.41   77.22   77.92   77.83   77.32   77.29   75.82
   75.78   76.79   76.67    74.9   76.32   76.35   77.84   78.18   77.75   76.51
   75.89   75.81   77.11   77.81   78.41   79.31   78.31   78.41   78.01   79.31
   78.71   78.81   78.41   79.11   78.41   80.21   78.21   78.41   85.41   86.01
Pier Skew, UpSta & Num, DnSta & Num=  ,4978.7, 2 ,4978.7, 2 , 0 , 0 , 0 ,,
     1.6     1.6
   68.17    77.8
     1.6     1.6
   68.08   77.71
Pier Skew, UpSta & Num, DnSta & Num=  ,5003.4, 2 ,5003.4, 2 , 0 , 0 , 0 ,,
     1.6     1.6
   63.67   77.72
     1.6     1.6
   63.58   77.63
Pier Skew, UpSta & Num, DnSta & Num=  ,5028.5, 2 ,5028.5, 2 , 0 , 0 , 0 ,,
     1.6     1.6
   68.37   77.69
     1.6     1.6
   68.28    77.6
Pier Skew, UpSta & Num, DnSta & Num=  ,5053.4, 2 ,5053.4, 2 , 0 , 0 , 0 ,,
     1.6     1.6
   68.03   77.72
     1.6     1.6
   67.94   77.63
Abutment Skew #Up #Dn= , 2 , 2
    4955  4961.7
   76.88   73.77
    4955  4961.7
   76.79   73.68
Abutment Skew #Up #Dn= , 2 , 2
  5071.8 5077.49
   73.58   76.76
  5071.8 5077.49
   73.49   76.67
BR Coef= 1 , 1 , 0 ,1.25, 0 ,,,.8,0,2,0,
WSPro=,,,, 1 ,,,, 0 ,,,, 0 ,,,,-1 ,-1 ,-1 , 0 , 0 , 0 , 0 , 0
BR U #Sta/Elev= 136
     191    80.3     331    79.8     341    79.3     391    79.1     401    79.5
     431      79     601    79.8     811    79.9     891    80.1     941    79.9
    1031    79.7    1061    79.5    1151    79.7    1481    79.3    1561    77.8
  1761.6    78.4  1901.6    77.3  2041.6    79.1  2081.6    79.6  2161.6    79.3
  2201.6    78.7  2461.6    78.4  2711.6    77.8  2751.6    78.4  2771.6    77.1
  2881.6    78.1  2921.6    77.9  3071.6    78.1  3101.6      78  3181.6    77.4
  3211.6    78.2  3401.6    78.3  3511.6    78.8  3671.6    77.2  3721.6    76.8
  3751.6    76.4  3791.6      77  4021.6    76.5  4061.6    76.6  4091.6    76.7
  4111.6    76.7  4141.6    76.6  4351.6    75.9  4391.6      76  4491.6      76
  4506.9   75.85  4541.6    75.5  4738.4   77.19  4744.4    77.2  4803.2   77.31
  4803.4   77.31  4859.8   77.78  4861.5   77.79  4870.6   77.87  4903.6   78.01
    4925   78.01  4948.7   77.92 4950.29   77.41  4950.4   77.38 4950.51   77.34
    4955   75.91 4955.11   75.87  4955.2   75.85  4961.6    73.8  4961.7   73.77
  4963.1   73.48  4978.6   69.23  4988.5   68.52  4991.8   65.41  4995.9   64.19
  5003.5   64.73  5006.7   64.82  5008.1   65.31  5017.4   68.43    5020    69.3
  5028.5   69.38  5037.6    70.2  5038.9   68.93  5053.4   69.04  5071.7   73.55
  5071.8   73.58 5077.29   74.97  5077.4   74.99  5077.5   75.02 5082.89   76.38
    5083   76.41 5083.11   76.44    5089   77.93  5141.9    78.2  5142.8    78.2
  5197.6   78.27  5253.4   78.25  5305.7   77.84  5306.1   77.83  5308.9   77.76
  5332.7    77.2  5352.7    76.6  5414.9   75.98  5422.7    75.9  5452.7    77.2
    5496    77.3    5746    77.9    5756    78.5    5816    79.4    5836      79
    6026    78.4    6136    78.6    6146    78.1    6266    78.5    6276    78.1
    6566    79.4    6586    78.8  6642.8    78.8  6702.8    78.9  6712.8    78.5
  6852.8    79.2  6882.8    78.5  6912.8    78.9  6922.8    78.7  7122.8    79.2
  7482.8    79.9  7492.8    79.7  7632.8    80.3  7800.7    79.2  7810.7    79.4
  7830.7    79.3  7980.7      79  8000.7    78.3  8080.7    78.3  8090.7    78.7
  8100.7    78.5  8120.7    80.1  8130.7    80.3  8200.7    85.5    8203   85.53
  8240.7    86.1
BR U #Mann= 4
     191      .1  4948.7    .035    5089      .1    8203      .2
BR U Banks=4948.7,5089
BR D #Sta/Elev= 136
     191   80.21     331   79.71     341   79.21     391   79.01     401   79.41
     431   78.91     601   79.71     811   79.81     891   80.01     941   79.81
    1031   79.61    1061   79.41    1151   79.61    1481   79.21    1561   77.71
  1761.6   78.31  1901.6   77.21  2041.6   79.01  2081.6   79.51  2161.6   79.21
  2201.6   78.61  2461.6   78.31  2711.6   77.71  2751.6   78.31  2771.6   77.01
  2881.6   78.01  2921.6   77.81  3071.6   78.01  3101.6   77.91  3181.6   77.31
  3211.6   78.11  3401.6   78.21  3511.6   78.71  3671.6   77.11  3721.6   76.71
  3751.6   76.31  3791.6   76.91  4021.6   76.41  4061.6   76.51  4091.6   76.61
  4111.6   76.61  4141.6   76.51  4351.6   75.81  4391.6   75.91  4491.6   75.91
  4506.9   75.76  4541.6   75.41  4738.4    77.1  4744.4   77.11  4803.2   77.22
  4803.4   77.22  4859.8   77.69  4861.5    77.7  4870.6   77.78  4903.6   77.92
    4925   77.92  4948.7   77.83 4950.29   77.32  4950.4   77.29 4950.51   77.25
    4955   75.82 4955.11   75.78  4955.2   75.76  4961.6   73.71  4961.7   73.68
  4963.1   73.39  4978.6   69.14  4988.5   68.43  4991.8   65.32  4995.9    64.1
  5003.5   64.64  5006.7   64.73  5008.1   65.22  5017.4   68.34    5020   69.21
  5028.5   69.29  5037.6   70.11  5038.9   68.84  5053.4   68.95  5071.7   73.46
  5071.8   73.49 5077.29   74.88  5077.4    74.9  5077.5   74.93 5082.89   76.29
    5083   76.32 5083.11   76.35    5089   77.84  5141.9   78.11  5142.8   78.11
  5197.6   78.18  5253.4   78.16  5305.7   77.75  5306.1   77.74  5308.9   77.67
  5332.7   77.11  5352.7   76.51  5414.9   75.89  5422.7   75.81  5452.7   77.11
    5496   77.21    5746   77.81    5756   78.41    5816   79.31    5836   78.91
    6026   78.31    6136   78.51    6146   78.01    6266   78.41    6276   78.01
    6566   79.31    6586   78.71  6642.8   78.71  6702.8   78.81  6712.8   78.41
  6852.8   79.11  6882.8   78.41  6912.8   78.81  6922.8   78.61  7122.8   79.11
  7482.8   79.81  7492.8   79.61  7632.8   80.21  7800.7   79.11  7810.7   79.31
  7830.7   79.21  7980.7   78.91  8000.7   78.21  8080.7   78.21  8090.7   78.61
  8100.7   78.41  8120.7   80.01  8130.7   80.21  8200.7   85.41    8203   85.44
  8240.7   86.01
BR D #Mann= 4
     191      .1  4948.7    .035    5089      .1    8203      .2
BR D Banks=4948.7,5089
BC Design=,, 0 ,, 0 ,,,,,,

Type RM Length L Ch R = 1 ,78678.3 ,739.8,739.8,739.8
BEGIN DESCRIPTION:
Downstream Section of Bridge/Culvert/Weir
END DESCRIPTION:
XS GIS Cut Line= 6
      3105973.79     13895780.23      3106158.15     13891459.72
      3106091.05     13891381.44      3105551.49     13891549.18
      3105456.43     13891437.36      3105502.26     13888540.92
#Sta/Elev= 30
     191   80.21     431   78.91    1481   79.21    1561   77.71  1901.6   77.21
  2081.6   79.51  2751.6   78.31  2771.6   77.01  3511.6   78.71  3751.6   76.31
  4541.6   75.41  4948.7   77.83  4978.6   69.14  4988.5   68.43  4991.8   65.32
  4995.9    64.1  5006.7   64.73    5020   69.21  5037.6   70.11  5038.9   68.84
  5053.4   68.95    5089   77.84  5253.4   78.16  5422.7   75.81    5816   79.31
    6276   78.01  7632.8   80.21  8080.7   78.21    8203   85.44  8240.7   86.01
#Mann= 4 , 1 , 0
     191      .1       0  4948.7    .035       0    5089      .1       0
    8203      .2       0
#XS Ineff= 2 , 0
       0    4006      81    6860       0      81
Permanent Ineff=
       F       F
Bank Sta=4948.7,5089
XS Rating Curve= 0
Exp/Cntr=.5,.3

Type RM Length L Ch R = 1 ,77938.5 ,54,54,54
BEGIN DESCRIPTION:
Upstream Section of Bridge/Culvert/Weir
END DESCRIPTION:
XS GIS Cut Line= 5
      3106095.98     13896365.01      3106229.18     13892099.54
      3106167.68     13891728.67      3106196.63     13891197.11
      3106331.99     13888333.43
#Sta/Elev= 30
  -187.7    80.4  -182.8    80.4   572.3    80.2   642.3    78.8   802.3    79.9
  1782.3    77.2  2122.3    78.3  2272.3    76.7  2302.3    78.2  2712.3    78.8
  4538.7    75.9  4578.7    74.7  4796.7   77.22  4938.6   74.75  4959.6   68.33
  4972.3   68.07  4985.5   64.14  5007.4    64.1  5017.2   64.98  5029.8   69.62
  5037.6   75.22  5423.4    77.7  6885.8    79.2  7245.8    77.4  7275.8    79.2
  7655.2   78.92  7685.8    76.4  7715.8    79.6  7755.8    81.2    7855    81.4
#Mann= 5 , 1 , 0
  -187.7      .2       0  -182.8      .1       0  4938.6    .035       0
  5037.6      .1       0  7655.2      .2       0
#XS Ineff= 2 , 0
       0    3203    80.5    6090       0    79.3
Permanent Ineff=
       F       F
Bank Sta=4938.6,5037.6
XS Rating Curve= 0
Exp/Cntr=.5,.3

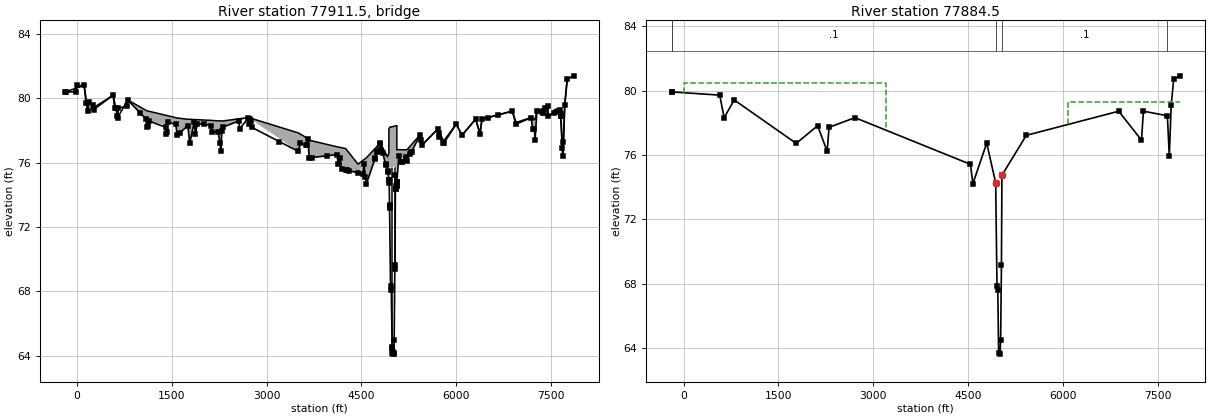
Type RM Length L Ch R = 3 ,77911.5 ,,,
BEGIN DESCRIPTION:
SWEETWATER LANE
Structure ID: P18-34
END DESCRIPTION:
Bridge Culvert--1,0,-1,-1, 0
Deck Dist Width WeirC Skew NumUp NumDn MinLoCord MaxHiCord MaxSubmerge Is_Ogee
10,34,2.6,0, 60, 60, , , .95, 0, 1,1,,
  -187.7   112.3   172.3   572.3   642.3   802.3  1102.3  1562.3  1582.3  1752.3
  1782.3  1852.3  1872.3  2122.3  2232.3  2272.3  2302.3  2712.3  3502.3  3652.3
  3672.3  4112.3  4248.5  4445.2  4538.7  4578.7  4796.7  4911.6 4933.39  4933.5
  4938.6 4944.01  4944.1 5053.89    5054  5059.6 5059.71  5091.6  5217.6  5423.4
  5459.7  5709.7  5799.7  5999.7  6089.7  6305.8  6375.8  6405.8  6885.8  6945.8
  7185.8  7245.8  7275.8  7445.8  7455.8  7645.8  7685.8  7715.8  7755.8    7855
    80.4    80.8    79.2    80.2    78.8    79.9   79.23    78.8   78.78    78.7
    78.7   78.68   78.68   78.63    78.6    78.6   78.59   78.81   77.85    77.5
    77.4   76.99   76.88   75.91   76.19   76.31   77.23   76.36   76.59   78.09
   78.14    78.2    78.2    78.3    78.3    78.3    76.8   76.81    76.8   77.71
   77.11   78.11   77.34   78.41   77.71   78.71   77.81   78.71   79.21    78.5
   78.81   78.68   79.21   79.51   78.91   79.31    76.4    79.6    81.2    81.4
    80.4    80.8    79.2    80.2    78.8    79.9    78.2    78.4    77.7    78.3
    77.2    78.5    77.8    78.3    77.9    76.7    78.2    78.8    76.7    77.5
    76.3    76.5   75.55   75.37    75.9    74.7   77.22   75.51   74.92   74.92
   74.75   73.33    75.7    75.8   74.55   74.83   74.83   76.41    76.1    77.7
    77.1    78.1    77.2    78.4    77.7    78.7    77.8    78.7    79.2    78.4
    78.8    77.4    79.2    79.5    78.9    79.3    76.4    79.6    81.2    81.4
  -187.7   112.3   172.3   572.3   642.3   802.3  1102.3  1562.3  1582.3  1752.3
  1782.3  1852.3  1872.3  2122.3  2232.3  2272.3  2302.3  2712.3  3502.3  3652.3
  3672.3  4112.3  4248.5  4445.2  4538.7  4578.7  4796.7  4911.6 4933.39  4933.5
  4938.6 4944.01  4944.1 5053.89    5054  5059.6 5059.71  5091.6  5217.6  5423.4
  5459.7  5709.7  5799.7  5999.7  6089.7  6305.8  6375.8  6405.8  6885.8  6945.8
  7185.8  7245.8  7275.8  7445.8  7455.8  7645.8  7685.8  7715.8  7755.8    7855
    80.4    80.8    79.2    80.2    78.8    79.9   79.23    78.8   78.78    78.7
    78.7   78.68   78.68   78.63    78.6    78.6   78.59   78.81   77.85    77.5
    77.4   76.99   76.88   75.91   76.19   76.31   77.23   76.36   76.59   78.09
   78.14    78.2    78.2    78.3    78.3    78.3    76.8   76.81    76.8   77.71
   77.11   78.11   77.34   78.41   77.71   78.71   77.81   78.71   79.21    78.5
   78.81   78.68   79.21   79.51   78.91   79.31    76.4    79.6    81.2    81.4
    80.3    80.7    79.1    80.1    78.7    79.8    78.1    78.3    77.6    78.2
    77.1    78.4    77.7    78.2    77.8    76.6    78.1    78.7    76.6    77.4
    76.2    76.4   75.45   75.27    75.8    74.6   77.12   75.41   74.82   74.82
   74.65   73.23    75.6    75.7   74.45   74.73   74.73   76.31      76    77.6
      77      78    77.1    78.3    77.6    78.6    77.7    78.6    79.1    78.3
    78.7    77.3    79.1    79.4    78.8    79.2    76.3    79.5    81.1    81.3
Pier Skew, UpSta & Num, DnSta & Num=  ,4963.8, 2 ,4963.8, 2 , 0 , 0 , 0 ,,
     1.2     1.2
   67.23   76.73
     1.2     1.2
   67.13   76.63
Pier Skew, UpSta & Num, DnSta & Num=  ,4985.5, 2 ,4985.5, 2 , 0 , 0 , 0 ,,
     1.2     1.2
   63.23   76.76
     1.2     1.2
   63.13   76.66
Pier Skew, UpSta & Num, DnSta & Num=  ,5007.4, 2 ,5007.4, 2 , 0 , 0 , 0 ,,
     1.2     1.2
   63.11   76.78
     1.2     1.2
   63.01   76.68
Pier Skew, UpSta & Num, DnSta & Num=  ,5029.8, 2 ,5029.8, 2 , 0 , 0 , 0 ,,
     1.2     1.2
   68.56   76.79
     1.2     1.2
   68.46   76.69
Abutment Skew #Up #Dn= , 2 , 2
  5050.5 5054.09
   74.38    75.8
  5050.5 5054.09
   74.28    75.7
BR Coef= 1 , 1 , 0 ,1.25, 0 ,,,.8,0,2,0,
WSPro=,,,, 1 ,,,, 0 ,,,, 0 ,,,,-1 ,-1 ,-1 , 0 , 0 , 0 , 0 , 0
BR U #Sta/Elev= 164
  -187.7    80.4  -182.8    80.4   -17.7    80.4    -7.7    80.8   112.3    80.8
   142.3    79.7   172.3    79.2   192.3    79.8   252.3    79.6   262.3    79.3
   572.3    80.2   592.3    79.4   622.3    79.4   632.3    78.9   642.3    78.8
   652.3    79.4   792.3    79.5   802.3    79.9   991.2   79.12  1092.3    78.7
  1102.3    78.2  1122.3    78.3  1132.3    78.6  1402.3    78.2  1412.3    77.8
  1422.3    77.9  1432.3    78.5  1562.3    78.4  1582.3    77.7  1631.2   77.87
  1752.3    78.3  1782.3    77.2  1852.3    78.5  1872.3    77.8  1902.3    78.4
  2012.3    78.4  2122.3    78.3  2132.3    77.9  2232.3    77.9  2262.3    77.2
  2272.3    76.7  2292.3      78  2302.3    78.2  2562.3    78.6  2572.3    78.1
  2712.3    78.8  2722.3    78.4  2742.3    78.7  2752.3    78.6  2762.3    78.2
  3200.9   77.31  3502.3    76.7  3532.3    77.2  3620.9   77.11  3632.3    77.1
  3652.3    77.5  3672.3    76.3  3720.9   76.32  3950.9   76.43  4112.3    76.5
  4132.3    75.9  4162.3    76.3  4192.3    75.6  4248.5   75.55  4278.5   75.52
  4298.5    75.5  4445.2   75.37  4518.7    75.3  4538.7    75.9  4558.7    75.1
  4578.7    74.7  4713.7   76.23  4717.9   76.29  4744.7   76.67  4751.6   76.68
  4766.8   76.71  4789.4   76.79  4796.7   77.22  4800.4   77.16  4834.4   76.63
  4880.4   75.91  4884.9   75.84  4911.6   75.51  4917.5   75.44 4933.39   74.92
  4933.5   74.92 4933.61   74.91  4938.6   74.75  4943.9   73.36 4944.01   73.33
  4944.1   73.31  4944.4   73.23  4944.5    73.2  4959.6   68.33  4972.3   68.07
  4982.8   64.56  4985.5   64.14  4986.7    64.5  4997.7   64.22  5004.8   64.13
  5007.4    64.1  5013.3   64.16  5017.2   64.98  5027.4   69.38  5029.8   69.62
  5037.6   75.22  5050.4   74.39  5050.5   74.38 5053.89   74.55    5054   74.55
  5054.1   74.56 5059.49   74.82  5059.6   74.83 5059.71   74.83  5091.6   76.41
  5147.4   76.03  5148.8   76.02  5197.3   76.33  5208.9    76.2  5217.6    76.1
  5262.5   76.51  5290.7   76.66  5293.5   76.68  5423.4    77.7  5440.1   77.42
  5459.7    77.1  5709.7    78.1  5720.1   77.84  5729.7    77.6  5790.1   77.25
  5799.7    77.2  5999.7    78.4  6089.7    77.7  6305.8    78.7  6375.8    77.8
  6405.8    78.7  6503.2    78.8  6653.2   78.96  6885.8    79.2  6945.8    78.4
  7185.8    78.8  7205.8    78.1  7235.8    78.1  7245.8    77.4  7275.8    79.2
  7353.2   79.13  7373.2   79.11  7385.8    79.1  7395.8    79.4  7445.8    79.5
  7455.8    78.9  7543.2   79.08  7583.2   79.17  7603.2   79.21  7645.8    79.3
  7653.2      79  7655.2   78.92  7655.8    78.9  7675.8    76.9  7685.8    76.4
  7695.8    77.3  7715.8    79.6  7755.8    81.2    7855    81.4
BR U #Mann= 5
  -187.7      .2  -182.8      .1  4938.6    .035  5037.6      .1  7655.2      .2
BR U Banks=4938.6,5037.6
BR D #Sta/Elev= 164
  -187.7    80.3  -182.8    80.3   -17.7    80.3    -7.7    80.7   112.3    80.7
   142.3    79.6   172.3    79.1   192.3    79.7   252.3    79.5   262.3    79.2
   572.3    80.1   592.3    79.3   622.3    79.3   632.3    78.8   642.3    78.7
   652.3    79.3   792.3    79.4   802.3    79.8   991.2   79.02  1092.3    78.6
  1102.3    78.1  1122.3    78.2  1132.3    78.5  1402.3    78.1  1412.3    77.7
  1422.3    77.8  1432.3    78.4  1562.3    78.3  1582.3    77.6  1631.2   77.77
  1752.3    78.2  1782.3    77.1  1852.3    78.4  1872.3    77.7  1902.3    78.3
  2012.3    78.3  2122.3    78.2  2132.3    77.8  2232.3    77.8  2262.3    77.1
  2272.3    76.6  2292.3    77.9  2302.3    78.1  2562.3    78.5  2572.3      78
  2712.3    78.7  2722.3    78.3  2742.3    78.6  2752.3    78.5  2762.3    78.1
  3200.9   77.21  3502.3    76.6  3532.3    77.1  3620.9   77.01  3632.3      77
  3652.3    77.4  3672.3    76.2  3720.9   76.22  3950.9   76.33  4112.3    76.4
  4132.3    75.8  4162.3    76.2  4192.3    75.5  4248.5   75.45  4278.5   75.42
  4298.5    75.4  4445.2   75.27  4518.7    75.2  4538.7    75.8  4558.7      75
  4578.7    74.6  4713.7   76.13  4717.9   76.19  4744.7   76.57  4751.6   76.58
  4766.8   76.61  4789.4   76.69  4796.7   77.12  4800.4   77.06  4834.4   76.53
  4880.4   75.81  4884.9   75.74  4911.6   75.41  4917.5   75.34 4933.39   74.82
  4933.5   74.82 4933.61   74.81  4938.6   74.65  4943.9   73.26 4944.01   73.23
  4944.1   73.21  4944.4   73.13  4944.5    73.1  4959.6   68.23  4972.3   67.97
  4982.8   64.46  4985.5   64.04  4986.7    64.4  4997.7   64.12  5004.8   64.03
  5007.4      64  5013.3   64.06  5017.2   64.88  5027.4   69.28  5029.8   69.52
  5037.6   75.12  5050.4   74.29  5050.5   74.28 5053.89   74.45    5054   74.45
  5054.1   74.46 5059.49   74.72  5059.6   74.73 5059.71   74.73  5091.6   76.31
  5147.4   75.93  5148.8   75.92  5197.3   76.23  5208.9    76.1  5217.6      76
  5262.5   76.41  5290.7   76.56  5293.5   76.58  5423.4    77.6  5440.1   77.32
  5459.7      77  5709.7      78  5720.1   77.74  5729.7    77.5  5790.1   77.15
  5799.7    77.1  5999.7    78.3  6089.7    77.6  6305.8    78.6  6375.8    77.7
  6405.8    78.6  6503.2    78.7  6653.2   78.86  6885.8    79.1  6945.8    78.3
  7185.8    78.7  7205.8      78  7235.8      78  7245.8    77.3  7275.8    79.1
  7353.2   79.03  7373.2   79.01  7385.8      79  7395.8    79.3  7445.8    79.4
  7455.8    78.8  7543.2   78.98  7583.2   79.07  7603.2   79.11  7645.8    79.2
  7653.2    78.9  7655.2   78.82  7655.8    78.8  7675.8    76.8  7685.8    76.3
  7695.8    77.2  7715.8    79.5  7755.8    81.1    7855    81.3
BR D #Mann= 5
  -187.7      .2  -182.8      .1  4938.6    .035  5037.6      .1  7655.2      .2
BR D Banks=4938.6,5037.6
BC Design=,, 0 ,, 0 ,,,,,,

Type RM Length L Ch R = 1 ,77884.5 ,15.1,15.1,15.1
BEGIN DESCRIPTION:
Downstream Section of Bridge/Culvert/Weir
END DESCRIPTION:
XS GIS Cut Line= 5
      3106149.55     13896358.18      3106282.74     13892092.72
      3106221.24     13891721.85      3106250.19     13891190.29
      3106385.56     13888326.61
#Sta/Elev= 30
  -187.7   79.93  -182.8   79.93   572.3   79.73   642.3   78.33   802.3   79.43
  1782.3   76.73  2122.3   77.83  2272.3   76.23  2302.3   77.73  2712.3   78.33
  4538.7   75.43  4578.7   74.23  4796.7   76.75  4938.6   74.28  4959.6   67.86
  4972.3    67.6  4985.5   63.67  5007.4   63.63  5017.2   64.51  5029.8   69.15
  5037.6   74.75  5423.4   77.23  6885.8   78.73  7245.8   76.93  7275.8   78.73
  7655.2   78.45  7685.8   75.93  7715.8   79.13  7755.8   80.73    7855   80.93
#Mann= 5 , 1 , 0
  -187.7      .2       0  -182.8      .1       0  4938.6    .035       0
  5037.6      .1       0  7655.2      .2       0
#XS Ineff= 2 , 0
       0    3203    80.5    6090       0    79.3
Permanent Ineff=
       F       F
Bank Sta=4938.6,5037.6
XS Rating Curve= 0
Exp/Cntr=.5,.3