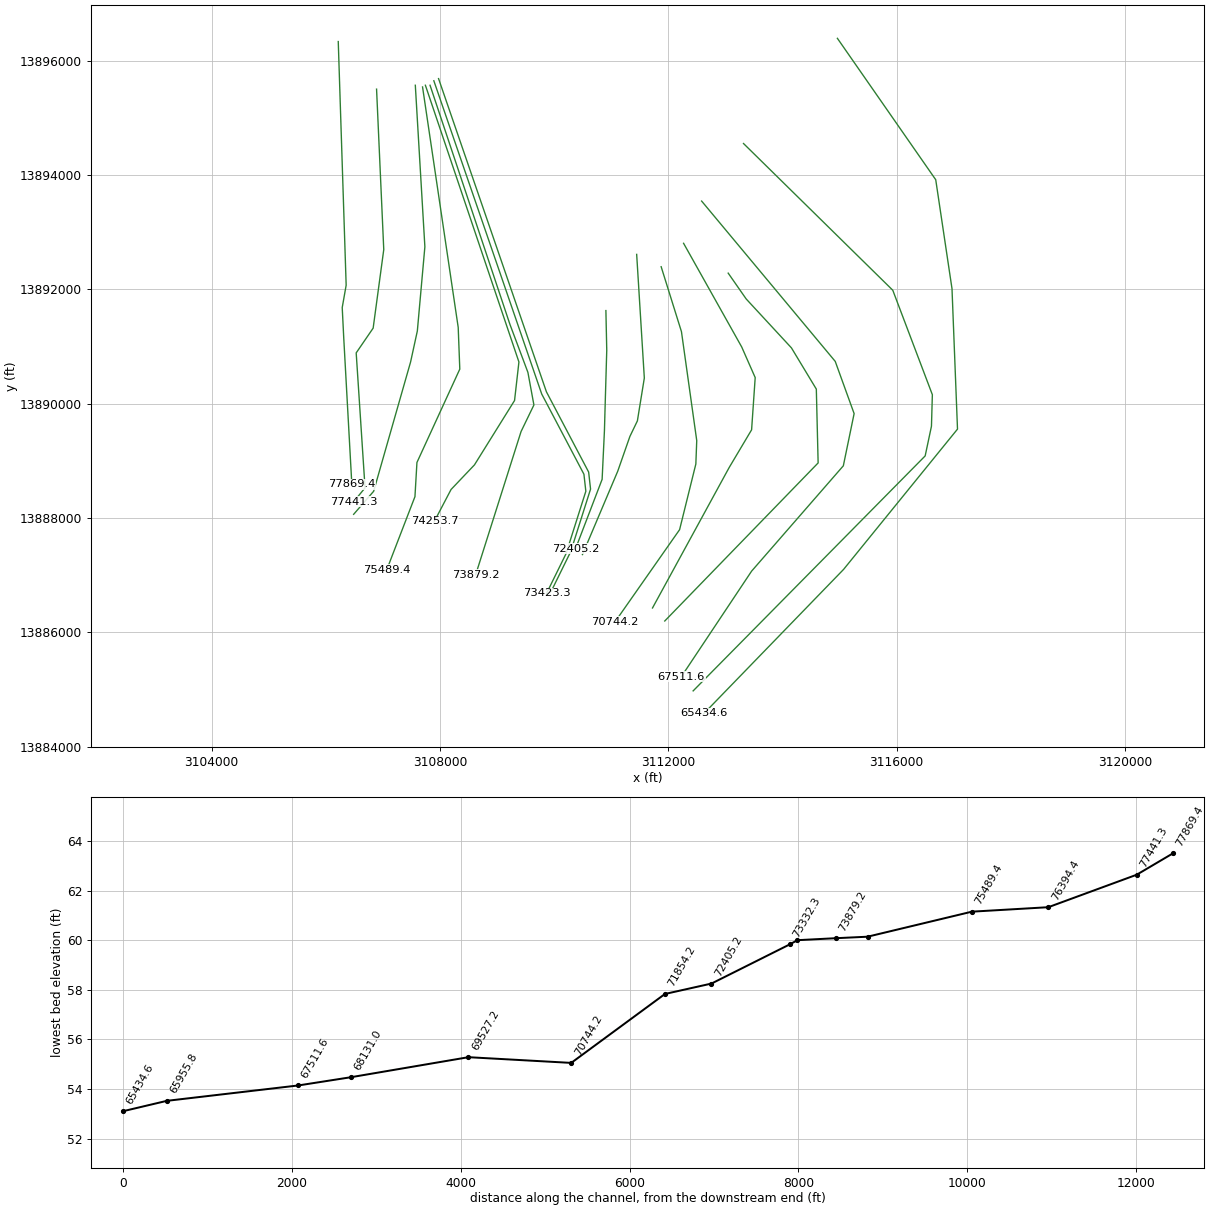
HEC-RAS study P118-00-00.PRJ: P118-00-00

--- P118-00-00.g01 (geometry) --- (continued)

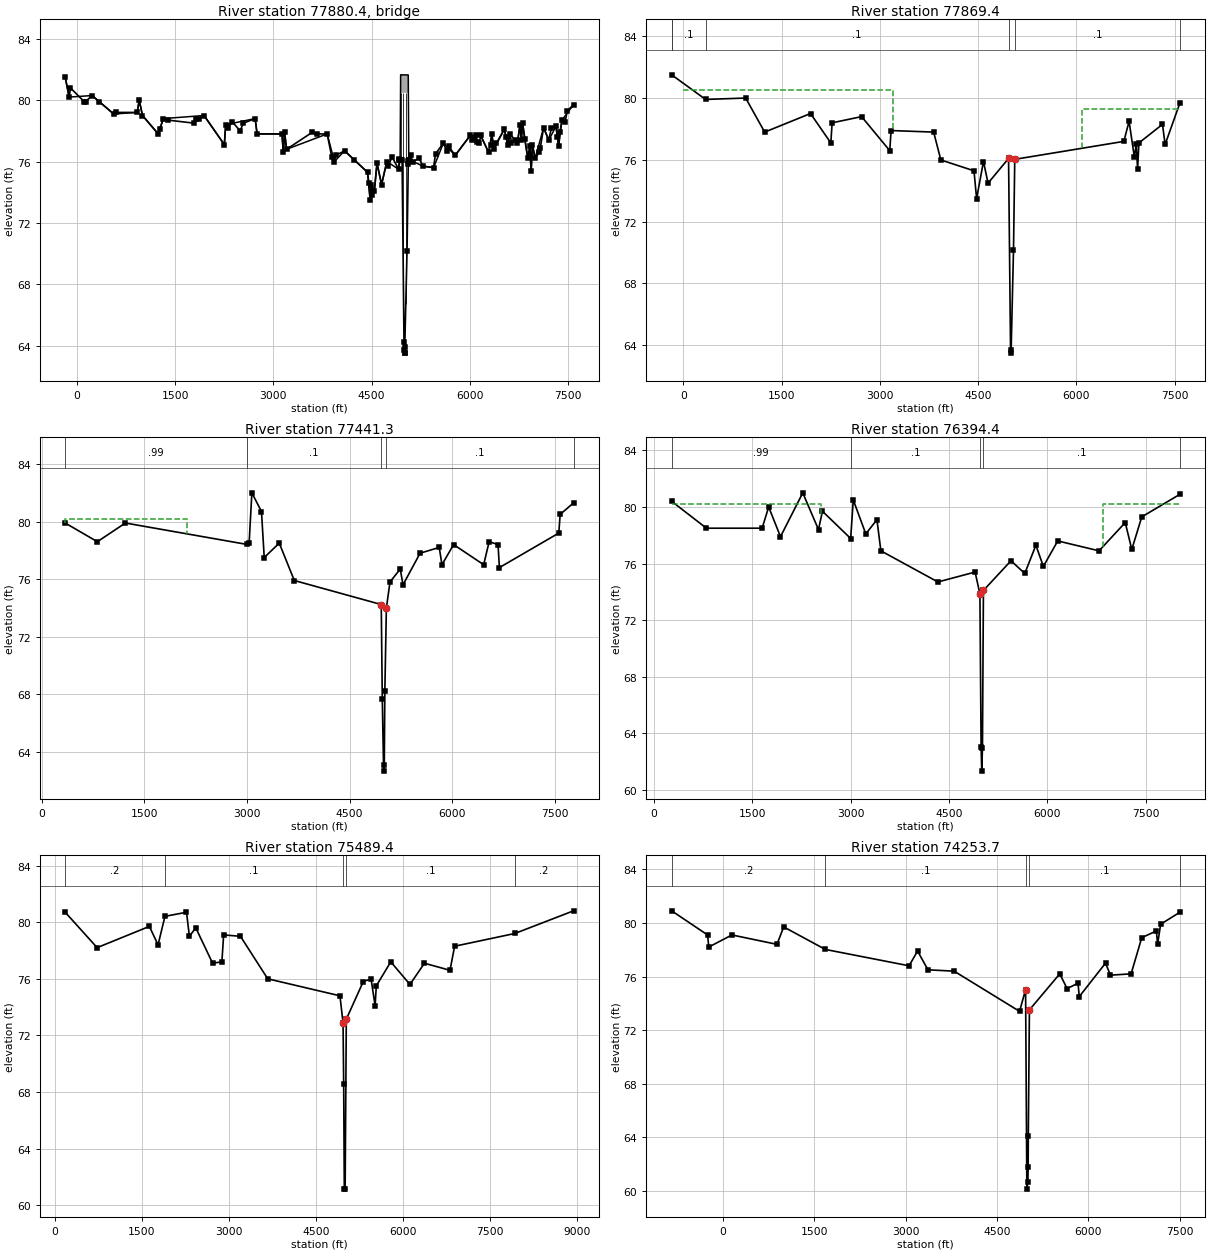
Type RM Length L Ch R = 3 ,77880.4 ,,,
BEGIN DESCRIPTION:
SERIES OF PIPELINES
END DESCRIPTION:
Bridge Culvert--1,0,-1,-1, 0
Deck Dist Width WeirC Skew NumUp NumDn MinLoCord MaxHiCord MaxSubmerge Is_Ogee
10,2,2.6,0, 60, 60, , , .95, 0, 1,1,,
  -178.8  -118.8   231.2   561.2   921.2   951.2  1001.2  1241.2  1321.2  1941.2
  2251.2  2271.2  2721.2  2751.2  3131.2  3151.2  3171.2  3201.2  3821.2  3931.2
  4087.2  4437.2  4477.2  4497.2  4541.9  4581.9  4651.9  4731.9  4911.9 4935.13
 4942.83 5059.13 5067.33  5285.4  5445.4  5595.4  5775.4  6005.4  6165.4  6285.4
  6335.4  6365.4  6525.4  6575.4  6615.4  6725.4  6765.4  6785.4  6805.4  6885.4
  6915.4  6935.4  6955.4  6995.4  7125.4  7205.4  7315.4  7355.4  7405.4  7582.8
    81.5    80.2    80.3    79.1    79.2      80      79    77.8    78.8      79
    77.1    78.4    78.8    77.8    77.8    76.6    77.9    76.8    77.8      76
    76.7    75.3    73.5    74.5    74.1    75.9    74.5      76    75.5   76.11
   81.65   81.64   76.13    75.7    75.6    77.2    76.4    77.7    77.7    76.6
    77.8    76.8    78.1    77.1    77.8    77.2    78.4    77.4    78.5    76.2
      77    75.4    77.1    76.2    78.2    77.4    78.3      77    78.7    79.7
    81.5    80.2    80.3    79.1    79.2      80      79    77.8    78.8      79
    77.1    78.4    78.8    77.8    77.8    76.6    77.9    76.8    77.8      76
    76.7    75.3    73.5    74.5    74.1    75.9    74.5      76    75.5    76.1
   80.48   80.47   76.13    75.7    75.6    77.2    76.4    77.7    77.7    76.6
    77.8    76.8    78.1    77.1    77.8    77.2    78.4    77.4    78.5    76.2
      77    75.4    77.1    76.2    78.2    77.4    78.3      77    78.7    79.7
  -178.8  -118.8   231.2   561.2   921.2   951.2  1001.2  1241.2  1321.2  1941.2
  2251.2  2271.2  2721.2  2751.2  3131.2  3151.2  3171.2  3201.2  3821.2  3931.2
  4087.2  4437.2  4477.2  4497.2  4541.9  4581.9  4651.9  4731.9  4911.9 4935.13
 4942.83 5059.13 5067.33  5285.4  5445.4  5595.4  5775.4  6005.4  6165.4  6285.4
  6335.4  6365.4  6525.4  6575.4  6615.4  6725.4  6765.4  6785.4  6805.4  6885.4
  6915.4  6935.4  6955.4  6995.4  7125.4  7205.4  7315.4  7355.4  7405.4  7582.8
    81.5    80.2    80.3    79.1    79.2      80      79    77.8    78.8      79
    77.1    78.4    78.8    77.8    77.8    76.6    77.9    76.8    77.8      76
    76.7    75.3    73.5    74.5    74.1    75.9    74.5      76    75.5   76.11
   81.65   81.64   76.13    75.7    75.6    77.2    76.4    77.7    77.7    76.6
    77.8    76.8    78.1    77.1    77.8    77.2    78.4    77.4    78.5    76.2
      77    75.4    77.1    76.2    78.2    77.4    78.3      77    78.7    79.7
    81.5    80.2    80.3    79.1    79.2      80      79    77.8    78.8      79
    77.1    78.4    78.8    77.8    77.8    76.6    77.9    76.8    77.8      76
    76.7    75.3    73.5    74.5    74.1    75.9    74.5      76    75.5    76.1
   80.48   80.47   76.13    75.7    75.6    77.2    76.4    77.7    77.7    76.6
    77.8    76.8    78.1    77.1    77.8    77.2    78.4    77.4    78.5    76.2
      77    75.4    77.1    76.2    78.2    77.4    78.3      77    78.7    79.7
Pier Skew, UpSta & Num, DnSta & Num=  ,4946.3, 2 ,4946.3, 2 , 0 , 0 , 0 ,,
     1.3     1.3
    75.1   81.48
     1.3     1.3
    75.1   81.48
Pier Skew, UpSta & Num, DnSta & Num=  ,4984, 2 ,4984, 2 , 0 , 0 , 0 ,,
     1.3     1.3
   67.12   81.48
     1.3     1.3
   67.12   81.48
Pier Skew, UpSta & Num, DnSta & Num=  ,5021.2, 2 ,5021.2, 2 , 0 , 0 , 0 ,,
     1.3     1.3
   65.59   81.47
     1.3     1.3
   65.59   81.47
Pier Skew, UpSta & Num, DnSta & Num=  ,5057.8, 2 ,5057.8, 2 , 0 , 0 , 0 ,,
     1.3     1.3
   74.27   81.47
     1.3     1.3
   74.27   81.47
BR Coef= 1 , 1 , 0 ,1.25, 0 ,,,.8,0,2,0,
WSPro=,,,, 1 ,,,, 0 ,,,, 0 ,,,,-1 ,-1 ,-1 , 0 , 0 , 0 , 0 , 0
BR U #Sta/Elev= 121
  -178.8    81.5  -118.8    80.2   -98.8    80.8   111.2    79.9   131.2    79.9
   231.2    80.3     339   79.91   561.2    79.1   591.2    79.2   921.2    79.2
   951.2      80  1001.2      79  1241.2    77.8  1261.2    78.1  1321.2    78.8
  1391.2    78.7  1791.2    78.5  1821.2    78.8  1861.2    78.8  1941.2      79
  2251.2    77.1  2271.2    78.4  2311.2    78.2  2371.2    78.6  2491.2      78
  2541.2    78.5  2721.2    78.8  2751.2    77.8  3131.2    77.8  3151.2    76.6
  3171.2    77.9  3201.2    76.8  3591.2    77.9  3671.2    77.8  3821.2    77.8
  3891.2    76.3  3931.2      76  3951.2    76.4  4087.2    76.7  4237.2    76.1
  4437.2    75.3  4457.2    74.6  4477.2    73.5  4497.2    74.5  4511.9    73.8
  4541.9    74.1  4581.9    75.9  4651.9    74.5  4731.9      76  4751.9    75.7
  4811.9    76.3  4911.9    75.5 4922.13   76.15 4923.53    76.1 4934.93    76.1
 4935.04    76.1 4935.13    76.1 4942.83    76.1 4965.13    76.1 4994.23   64.22
 4995.53    63.7 5002.03   63.55 5003.43   63.52 5005.83   63.93 5040.43   70.16
 5059.13   75.86 5059.73   76.04 5067.12   76.12 5067.23   76.12 5067.33   76.13
 5094.43   76.43 5127.63      76  5225.4    76.2  5285.4    75.7  5445.4    75.6
  5475.4    76.5  5595.4    77.2  5645.4    76.7  5675.4      77  5775.4    76.4
  6005.4    77.7  6025.4    77.4  6065.4    77.5  6095.4    77.7  6115.4    77.3
  6145.4    77.2  6165.4    77.7  6285.4    76.6  6315.4    77.1  6335.4    77.8
  6365.4    76.8  6405.4    77.2  6525.4    78.1  6555.4    77.6  6575.4    77.1
  6615.4    77.8  6635.4    77.2  6685.4    77.4  6725.4    77.2  6765.4    78.4
  6785.4    77.4  6805.4    78.5  6835.4    77.5  6885.4    76.2  6915.4      77
  6935.4    75.4  6955.4    77.1  6995.4    76.2  7055.4    76.6  7075.4    76.9
  7125.4    78.2  7205.4    77.4  7245.4    78.2  7315.4    78.3  7335.4    77.6
  7355.4      77  7375.4    77.9  7405.4    78.7  7455.4    78.6  7485.4    79.3
  7582.8    79.7
BR U #Mann= 6
  -178.8      .2  -178.8      .1     339      .1 4965.13    .045 5059.73      .1
  7582.8      .2
BR U Banks=4965.13,5059.73
BR D #Sta/Elev= 121
  -178.8    81.5  -118.8    80.2   -98.8    80.8   111.2    79.9   131.2    79.9
   231.2    80.3     339   79.91   561.2    79.1   591.2    79.2   921.2    79.2
   951.2      80  1001.2      79  1241.2    77.8  1261.2    78.1  1321.2    78.8
  1391.2    78.7  1791.2    78.5  1821.2    78.8  1861.2    78.8  1941.2      79
  2251.2    77.1  2271.2    78.4  2311.2    78.2  2371.2    78.6  2491.2      78
  2541.2    78.5  2721.2    78.8  2751.2    77.8  3131.2    77.8  3151.2    76.6
  3171.2    77.9  3201.2    76.8  3591.2    77.9  3671.2    77.8  3821.2    77.8
  3891.2    76.3  3931.2      76  3951.2    76.4  4087.2    76.7  4237.2    76.1
  4437.2    75.3  4457.2    74.6  4477.2    73.5  4497.2    74.5  4511.9    73.8
  4541.9    74.1  4581.9    75.9  4651.9    74.5  4731.9      76  4751.9    75.7
  4811.9    76.3  4911.9    75.5 4922.13   76.15 4923.53    76.1 4934.93    76.1
 4935.04    76.1 4935.13    76.1 4942.83    76.1 4965.13    76.1 4994.23   64.22
 4995.53    63.7 5002.03   63.55 5003.43   63.52 5005.83   63.93 5040.43   70.16
 5059.13   75.86 5059.73   76.04 5067.12   76.12 5067.23   76.12 5067.33   76.13
 5094.43   76.43 5127.63      76  5225.4    76.2  5285.4    75.7  5445.4    75.6
  5475.4    76.5  5595.4    77.2  5645.4    76.7  5675.4      77  5775.4    76.4
  6005.4    77.7  6025.4    77.4  6065.4    77.5  6095.4    77.7  6115.4    77.3
  6145.4    77.2  6165.4    77.7  6285.4    76.6  6315.4    77.1  6335.4    77.8
  6365.4    76.8  6405.4    77.2  6525.4    78.1  6555.4    77.6  6575.4    77.1
  6615.4    77.8  6635.4    77.2  6685.4    77.4  6725.4    77.2  6765.4    78.4
  6785.4    77.4  6805.4    78.5  6835.4    77.5  6885.4    76.2  6915.4      77
  6935.4    75.4  6955.4    77.1  6995.4    76.2  7055.4    76.6  7075.4    76.9
  7125.4    78.2  7205.4    77.4  7245.4    78.2  7315.4    78.3  7335.4    77.6
  7355.4      77  7375.4    77.9  7405.4    78.7  7455.4    78.6  7485.4    79.3
  7582.8    79.7
BR D #Mann= 6
  -178.8      .2  -178.8      .1     339      .1 4965.13    .045 5059.73      .1
  7582.8      .2
BR D Banks=4965.13,5059.73
BC Design=,, 0 ,, 0 ,,,,,,

Type RM Length L Ch R = 1 ,77869.4 ,428.1,428.1,428.1
BEGIN DESCRIPTION:
Downstream Section of Bridge/Culvert/Weir
END DESCRIPTION:
XS GIS Cut Line= 5
      3106216.96     13896339.03      3106355.57     13892074.85
      3106286.56     13891683.46      3106312.69     13891160.82
      3106454.92      13888590.3
#Sta/Elev= 30
  -178.8   81.48     339   79.89   951.2   79.98  1241.2   77.78  1941.2   78.98
  2251.2   77.08  2271.2   78.38  2721.2   78.78  3151.2   76.58  3171.2   77.88
  3821.2   77.78  3931.2   75.98  4437.2   75.28  4477.2   73.48  4581.9   75.88
  4651.9   74.48 4965.13   76.08 4995.53   63.68 5003.43    63.5 5040.43   70.14
 5059.73   76.02  6725.4   77.18  6805.4   78.48  6885.4   76.18  6915.4   76.98
  6935.4   75.38  6955.4   77.08  7315.4   78.28  7355.4   76.98  7582.8   79.68
#Mann= 6 , 1 , 0
  -178.8      .2       0  -178.8      .1       0     339      .1       0
 4965.13    .035       0 5059.73      .1       0  7582.8      .2       0
#XS Ineff= 2 , 0
       0    3203    80.5    6090       0    79.3
Permanent Ineff=
       F       F
Bank Sta=4965.13,5059.73
XS Rating Curve= 0
Exp/Cntr=.5,.3

Type RM Length L Ch R = 1 ,77441.3 ,1003.8,1046.9,1062.4
BEGIN DESCRIPTION:
Cross Section 77441.3
END DESCRIPTION:
XS GIS Cut Line= 6
      3106888.22     13895506.07      3107014.28     13892698.22
      3106828.51     13891323.46      3106531.26     13890889.98
      3106686.45     13888527.32      3106485.08      13888283.1
#Sta/Elev= 30
   340.7    79.9   810.7    78.6  1220.7    79.9    3000   78.41  3030.7    78.5
  3070.7      82  3211.4    80.7  3251.4    77.5  3471.4    78.5  3691.4    75.9
    4963   74.23  4978.2   67.68  4997.9   62.64  5007.4   63.07  5015.6   68.19
    5038   73.99    5091    75.8    5241    76.7    5281    75.6    5531    77.8
    5811    78.2    5851      77    6021    78.4    6461      77    6541    78.6
    6671    78.4    6691    76.8  7559.7    79.2  7579.7    80.5  7775.3    81.3
#Mann= 5 , 1 , 0
   340.7     .99       0    3000      .1       0    4963    .035       0
    5038      .1       0  7775.3      .2       0
#XS Ineff= 2 , 0
       0    2125    80.2               0
Permanent Ineff=
       F       F
Bank Sta=4963,5038
XS Rating Curve= 0
Exp/Cntr=.3,.1

Type RM Length L Ch R = 1 ,76394.4 ,763.5,905,920
BEGIN DESCRIPTION:
Cross Section 76394.4
END DESCRIPTION:
XS GIS Cut Line= 6
      3107567.22     13895573.97      3107734.68     13892747.38
      3107602.58     13891273.49      3107484.39     13890731.21
       3106837.2     13888468.33      3106486.63     13888064.84
#Sta/Elev= 30
     269    80.4     799    78.5    1649    78.5    1749      80    1929    77.9
    2269      81    2509    78.4    2569    79.7    3000   77.77    3039    80.5
  3230.6    78.1  3400.6    79.1  3460.6    76.9  4330.6    74.7  4898.1    75.4
  4971.4   73.86  4989.7   63.04  4999.4   61.33  5010.3   62.97  5025.2    74.1
  5445.9    76.2  5655.9    75.3  5825.9    77.3  5939.2    75.8  6159.2    77.6
  6789.2    76.9  7188.6    78.9  7288.6      77    7441    79.3  8024.1    80.9
#Mann= 5 , 1 , 0
     269     .99       0    3000      .1       0  4971.4    .035       0
  5025.2      .1       0  8024.1      .2       0
#XS Ineff= 2 , 0
       0    2550    80.2    6850       0    80.2
Permanent Ineff=
       F       F
Bank Sta=4971.4,5025.2
XS Rating Curve= 0
Exp/Cntr=.3,.1

Type RM Length L Ch R = 1 ,75489.4 ,1334.5,1235.7,1019.3
BEGIN DESCRIPTION:
Cross Section 75489.4
END DESCRIPTION:
XS GIS Cut Line= 6
      3107693.84     13895544.34      3108318.67     13891336.06
      3108346.48     13890606.07      3107595.63     13888972.28
      3107560.87     13888374.38      3107067.26     13887095.16
#Sta/Elev= 30
   182.9    80.7   732.9    78.2  1632.9    79.7  1782.9    78.4  1901.7   80.41
  2272.9    80.7  2322.9      79  2432.9    79.6  2722.9    77.1  2882.9    77.2
  2912.9    79.1  3202.9      79  3672.9      76  4917.3    74.8  4970.7   72.88
  4981.4   68.59  4992.3   61.17  5006.6   61.15  5026.9   73.15  5318.6    75.8
  5453.3      76  5523.3    74.1  5543.3    75.5  5793.3    77.2  6123.3    75.6
  6373.3    77.1  6813.3    76.6  6893.3    78.3  7930.5    79.2  8942.4    80.8
#Mann= 5 , 1 , 0
   182.9      .2       0  1901.7      .1       0  4970.7    .035       0
  5026.9      .1       0  7930.5      .2       0
#XS Ineff= 2 , 0
       0  2912.9    79.1               0
Permanent Ineff=
       F       F
Bank Sta=4970.7,5026.9
XS Rating Curve= 0
Exp/Cntr=.3,.1

Type RM Length L Ch R = 1 ,74253.7 ,242.4,374.5,429
BEGIN DESCRIPTION:
Cross Section 74253.7
END DESCRIPTION:
XS GIS Cut Line= 6
      3107743.76     13895573.97      3109382.37     13890731.21
      3109305.89     13890056.84      3108603.71     13888930.57
      3108193.53     13888499.53      3107901.53     13887943.34
#Sta/Elev= 30
  -844.3    80.9  -254.3    79.1  -234.3    78.2   145.7    79.1   885.7    78.4
   995.7    79.7    1680   78.02  3055.7    76.8  3195.7    77.9  3365.7    76.5
  3795.7    76.4  4871.3    73.4    4970   75.03    4991   60.14    5008   60.68
  5012.3   61.78  5014.7   64.14  5032.9   73.51  5531.7    76.2  5651.7    75.1
  5831.7    75.5  5851.7    74.5  6283.7      77  6363.7    76.1  6703.7    76.2
  6878.8    78.9  7118.8    79.4  7138.8    78.4  7188.8    79.9  7506.9    80.8
#Mann= 5 , 1 , 0
  -844.3      .2       0    1680      .1       0    4970    .035       0
  5032.9      .1       0  7506.9      .2       0
Bank Sta=4970,5032.9
XS Rating Curve= 0
Exp/Cntr=.3,.1

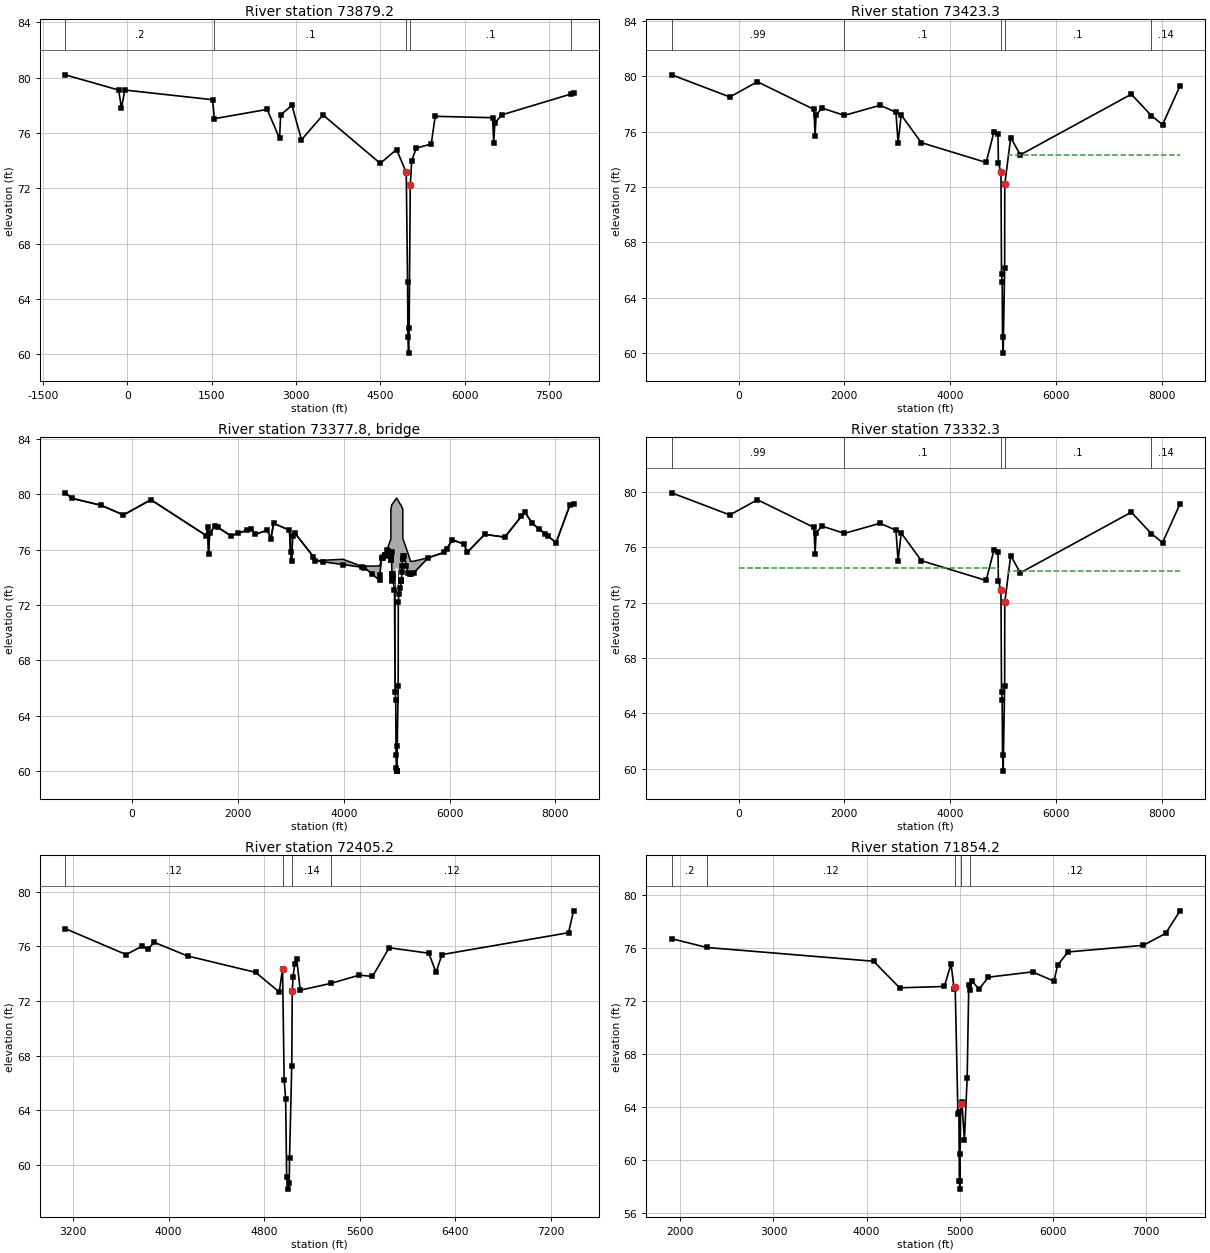
Type RM Length L Ch R = 1 ,73879.2 ,152.8,455.9,715.8
BEGIN DESCRIPTION:
Cross Section 73879.2-Interpolated
END DESCRIPTION:
XS GIS Cut Line= 6
      3107825.24     13895573.97      3109224.77     13891389.29
       3109539.9     13890548.96      3109644.94     13889978.74
      3109419.85     13889513.55      3108624.54     13887007.56
#Sta/Elev= 30
 -1102.8    80.2  -152.8    79.1  -102.8    77.8   -42.8    79.1  1517.2    78.4
  1548.9   77.03  2487.2    77.7  2707.2    75.6  2727.2    77.3  2927.2      78
  3097.2    75.5  3479.7    77.3  4497.2    73.8    4787    74.8  4959.4   73.14
  4982.8   65.23    4989   61.23  5001.2   60.08    5011   61.89  5031.1   72.27
    5057      74    5137    74.9  5403.8    75.2  5473.8    77.2  6493.8    77.1
  6513.8    75.3  6533.8    76.7  6653.8    77.3  7894.1   78.82  7932.9    78.9
#Mann= 5 , 1 , 0
 -1102.8      .2       0  1548.9      .1       0  4959.4    .035       0
  5031.1      .1       0  7894.1      .2       0
#XS Ineff= 2 , 0
       0  2927.2      78  5983.8       0    77.1
Permanent Ineff=
       F       F
Bank Sta=4959.4,5031.1
XS Rating Curve= 0
Exp/Cntr=.5,.3

Type RM Length L Ch R = 1 ,73423.3 ,91,91,91
BEGIN DESCRIPTION:
Upstream Section of Bridge/Culvert/Weir
END DESCRIPTION:
XS GIS Cut Line= 6
      3107891.73     13895652.36      3109781.54     13890170.75
      3110521.35     13888766.33      3110554.78     13888468.14
      3110207.09     13887373.83      3109866.12     13886680.95
#Sta/Elev= 30
 -1264.3    80.1  -164.3    78.5   355.7    79.6  1425.7    77.6  1445.7    75.7
  1465.7    77.2  1575.7    77.7    2000   77.17  2674.5    77.9  2974.5    77.4
  3014.5    75.2  3074.5    77.2  3454.5    75.2  4679.8   73.77  4826.8   75.97
  4903.4   75.84  4910.8   73.74  4959.4   73.06  4969.8   65.69  4982.8   65.15
    4989   61.15  5001.2      60  5029.3   66.17  5031.1   72.19  5143.8   75.57
  5324.7   74.32  7423.4    78.7    7803   77.15  8013.4    76.5  8343.4    79.3
#Mann= 5 , 1 , 0
 -1264.3     .99       0    2000      .1       0  4959.4    .035       0
  5031.1      .1       0    7803     .14       0
#XS Ineff= 2 , 0
       0 4908.12    74.5  5099.2       0    74.3
Permanent Ineff=
       F       F
Bank Sta=4959.4,5031.1
XS Rating Curve= 0
Exp/Cntr=.5,.3

Type RM Length L Ch R = 3 ,73377.8 ,,,
BEGIN DESCRIPTION:
AIRLINE DRIVE
Structure ID: P18-32
END DESCRIPTION:
Bridge Culvert--1,0,-1,-1, 0
Deck Dist Width WeirC Skew NumUp NumDn MinLoCord MaxHiCord MaxSubmerge Is_Ogee
10,71,2.6,0, 60, 60, , , .95, 0, 1,1,,
 -1264.3 -1134.3  -584.3  -164.3   355.7  1405.7  1425.7  1445.7  1465.7  1575.7
  1865.7  2255.7  2325.7  2554.5  2624.5  2674.5  2974.5  2994.5  3014.5  3034.5
  3074.5  3424.5  3454.5  3986.6  4336.6  4679.8  4681.1  4718.9  4784.3  4820.5
  4826.8  4884.5 4891.19  4891.3  4903.4 4909.11  5000.7 5088.99  5089.1  5089.2
  5103.3  5116.7 5116.81  5119.5  5143.8  5212.5  5263.1  5324.7  5594.2  5904.2
  6054.2  6274.2  6334.2  6664.2  7044.2  7423.4  7563.4  8013.4  8273.4  8343.4
    80.1    79.7    79.2    78.5    79.6      77    77.6    75.7    77.2    77.7
      77    77.5    77.1    77.4    76.8    77.9    77.4    75.8    75.2      77
    77.2    75.5    75.2    75.3    74.8   74.82   74.82   75.41   75.59   76.01
    76.1    76.7   76.82   78.92   79.14   79.24   79.72   79.15   79.15   79.15
   79.04   78.91   76.81   76.78   76.52   75.76   75.15   75.16   75.41   75.81
    76.7    76.4    75.8    77.1    76.9    78.7    77.9    76.5    79.2    79.3
    80.1    79.7    79.2    78.5    79.6      77    77.6    75.7    77.2    77.7
      77    77.5    77.1    77.4    76.8    77.9    77.4    75.8    75.2      77
    77.2    75.5    75.2   74.92   74.73   73.77   74.16    75.4   75.58   75.55
   75.97   75.22   75.44   75.44   75.84   74.22    74.7   74.13   73.82   73.82
    74.4   75.33   75.33   75.52   75.57   74.33   74.26   74.32    75.4    75.8
    76.7    76.4    75.8    77.1    76.9    78.7    77.9    76.5    79.2    79.3
 -1264.3 -1134.3  -584.3  -164.3   355.7  1405.7  1425.7  1445.7  1465.7  1575.7
  1865.7  2255.7  2325.7  2554.5  2624.5  2674.5  2974.5  2994.5  3014.5  3034.5
  3074.5  3424.5  3454.5  3986.6  4336.6  4679.8  4681.1  4718.9  4784.3  4820.5
  4826.8  4884.5 4891.19  4891.3  4903.4 4909.11  5000.7 5088.99  5089.1  5089.2
  5103.3  5116.7 5116.81  5119.5  5143.8  5212.5  5263.1  5324.7  5594.2  5904.2
  6054.2  6274.2  6334.2  6664.2  7044.2  7423.4  7563.4  8013.4  8273.4  8343.4
    80.1    79.7    79.2    78.5    79.6      77    77.6    75.7    77.2    77.7
      77    77.5    77.1    77.4    76.8    77.9    77.4    75.8    75.2      77
    77.2    75.5    75.2    75.3    74.8   74.82   74.82   75.41   75.59   76.01
    76.1    76.7   76.82   78.92   79.14   79.24   79.72   79.15   79.15   79.15
   79.04   78.91   76.81   76.78   76.52   75.76   75.15   75.16   75.41   75.81
    76.7    76.4    75.8    77.1    76.9    78.7    77.9    76.5    79.2    79.3
   79.95   79.55   79.05   78.35   79.45   76.85   77.45   75.55   77.05   77.55
   76.85   77.35   76.95   77.25   76.65   77.75   77.25   75.65   75.05   76.85
   77.05   75.35   75.05   74.77   74.58   73.62   74.01   75.25   75.43    75.4
   75.82   75.07   75.29   75.29   75.69   74.07   74.55   73.98   73.67   73.67
   74.25   75.18   75.18   75.37   75.42   74.18   74.11   74.17   75.25   75.65
   76.55   76.25   75.65   76.95   76.75   78.55   77.75   76.35   79.05   79.15
Pier Skew, UpSta & Num, DnSta & Num=  ,4969.8, 2 ,4969.8, 2 , 0 , 0 , 0 ,,
     1.3     1.3
   64.66   75.54
     1.3     1.3
   64.51   75.39
Pier Skew, UpSta & Num, DnSta & Num=  ,5029.3, 2 ,5029.3, 2 , 0 , 0 , 0 ,,
     1.3     1.3
   65.02   75.52
     1.3     1.3
   64.87   75.37
Abutment Skew #Up #Dn= , 2 , 2
    4909  4910.8
   74.22   73.74
    4909  4910.8
   74.07   73.59
Abutment Skew #Up #Dn= , 2 , 2
  5087.3 5089.19
   73.74   74.13
  5087.3 5089.19
   73.59   73.98
BR Coef= 1 , 1 , 0 ,1.25, 0 ,,,.8,0,2,0,
WSPro=,,,, 1 ,,,, 0 ,,,, 0 ,,,,-1 ,-1 ,-1 , 0 , 0 , 0 , 0 , 0
BR U #Sta/Elev= 101
 -1264.3    80.1 -1134.3    79.7  -584.3    79.2  -164.3    78.5   355.7    79.6
  1405.7      77  1425.7    77.6  1445.7    75.7  1465.7    77.2  1575.7    77.7
  1625.7    77.6  1865.7      77    2000   77.17  2175.7    77.4  2255.7    77.5
  2325.7    77.1  2554.5    77.4  2624.5    76.8  2674.5    77.9  2974.5    77.4
  2994.5    75.8  3014.5    75.2  3034.5      77  3074.5    77.2  3424.5    75.5
  3454.5    75.2    3608   75.12  3986.6   74.92  4336.6   74.73  4391.4    74.7
    4534   74.24  4679.8   73.77  4681.1   74.16  4718.9    75.4  4724.3   75.41
    4740   75.42  4748.3   75.45  4783.7   75.58  4784.3   75.58  4820.5   75.55
  4826.8   75.97  4834.5   75.87  4884.5   75.22  4885.4   75.25 4891.19   75.44
  4891.3   75.44 4891.41   75.45  4903.4   75.84    4909   74.25 4909.11   74.22
  4909.2   74.19  4910.7   73.77  4910.8   73.74  4925.1   73.99  4959.4   73.06
  4969.8   65.69  4982.8   65.15    4989   61.15  4995.8    60.2  5000.7   60.02
  5001.2      60  5005.6   60.04    5011   61.81  5029.3   66.17  5031.1   72.19
  5043.6    72.8  5067.3    73.2  5087.2   73.74  5087.3   73.74 5088.99   73.81
  5089.1   73.82  5089.2   73.82  5103.3    74.4  5109.3   74.81 5116.59   75.32
  5116.7   75.33 5116.81   75.33  5119.5   75.52  5143.8   75.57  5186.2    74.8
  5212.5   74.33  5258.2   74.26  5263.1   74.26  5324.7   74.32  5594.2    75.4
  5904.2    75.8  5948.6   76.07  6054.2    76.7  6274.2    76.4  6334.2    75.8
  6664.2    77.1  7044.2    76.9  7354.2    78.4  7423.4    78.7  7563.4    77.9
  7683.4    77.5    7803   77.15  7853.4      77  8013.4    76.5  8273.4    79.2
  8343.4    79.3
BR U #Mann= 5
 -1264.3     .99    2000      .1  4959.4    .035  5031.1      .1    7803     .14
BR U Banks=4959.4,5031.1
BR D #Sta/Elev= 101
 -1264.3   79.95 -1134.3   79.55  -584.3   79.05  -164.3   78.35   355.7   79.45
  1405.7   76.85  1425.7   77.45  1445.7   75.55  1465.7   77.05  1575.7   77.55
  1625.7   77.45  1865.7   76.85    2000   77.02  2175.7   77.25  2255.7   77.35
  2325.7   76.95  2554.5   77.25  2624.5   76.65  2674.5   77.75  2974.5   77.25
  2994.5   75.65  3014.5   75.05  3034.5   76.85  3074.5   77.05  3424.5   75.35
  3454.5   75.05    3608   74.97  3986.6   74.77  4336.6   74.58  4391.4   74.55
    4534   74.09  4679.8   73.62  4681.1   74.01  4718.9   75.25  4724.3   75.26
    4740   75.27  4748.3    75.3  4783.7   75.43  4784.3   75.43  4820.5    75.4
  4826.8   75.82  4834.5   75.72  4884.5   75.07  4885.4    75.1 4891.19   75.29
  4891.3   75.29 4891.41    75.3  4903.4   75.69    4909    74.1 4909.11   74.07
  4909.2   74.04  4910.7   73.62  4910.8   73.59  4925.1   73.84  4959.4   72.91
  4969.8   65.54  4982.8      65    4989      61  4995.8   60.05  5000.7   59.87
  5001.2   59.85  5005.6   59.89    5011   61.66  5029.3   66.02  5031.1   72.04
  5043.6   72.65  5067.3   73.05  5087.2   73.59  5087.3   73.59 5088.99   73.66
  5089.1   73.67  5089.2   73.67  5103.3   74.25  5109.3   74.66 5116.59   75.17
  5116.7   75.18 5116.81   75.18  5119.5   75.37  5143.8   75.42  5186.2   74.65
  5212.5   74.18  5258.2   74.11  5263.1   74.11  5324.7   74.17  5594.2   75.25
  5904.2   75.65  5948.6   75.92  6054.2   76.55  6274.2   76.25  6334.2   75.65
  6664.2   76.95  7044.2   76.75  7354.2   78.25  7423.4   78.55  7563.4   77.75
  7683.4   77.35    7803      77  7853.4   76.85  8013.4   76.35  8273.4   79.05
  8343.4   79.15
BR D #Mann= 5
 -1264.3     .99    2000      .1  4959.4    .035  5031.1      .1    7803     .14
BR D Banks=4959.4,5031.1
BC Design=,, 0 ,, 0 ,,,,,,

Type RM Length L Ch R = 1 ,73332.3 ,927.1,927.1,927.1
BEGIN DESCRIPTION:
Downstream Section of Bridge/Culvert/Weir
END DESCRIPTION:
XS GIS Cut Line= 6
       3107974.4      13895690.4       3109864.2     13890208.79
      3110604.01     13888804.37      3110637.44     13888506.18
      3110289.75     13887411.87      3109948.79     13886718.98
#Sta/Elev= 30
 -1264.3   79.93  -164.3   78.33   355.7   79.43  1425.7   77.43  1445.7   75.53
  1465.7   77.03  1575.7   77.53    2000      77  2674.5   77.73  2974.5   77.23
  3014.5   75.03  3074.5   77.03  3454.5   75.03  4679.8    73.6  4826.8    75.8
  4903.4   75.67  4910.8   73.57  4959.4   72.89  4969.8   65.52  4982.8   64.98
    4989   60.98  5001.2   59.83  5029.3      66  5031.1   72.02  5143.8    75.4
  5324.7   74.15  7423.4   78.53    7803   76.98  8013.4   76.33  8343.4   79.13
#Mann= 5 , 1 , 0
 -1264.3     .99       0    2000      .1       0  4959.4    .035       0
  5031.1      .1       0    7803     .14       0
#XS Ineff= 2 , 0
       0 4908.12    74.5  5099.2       0    74.3
Permanent Ineff=
       F       F
Bank Sta=4959.4,5031.1
XS Rating Curve= 0
Exp/Cntr=.5,.3

Type RM Length L Ch R = 1 ,72405.2 ,590.2,551,394.8
BEGIN DESCRIPTION:
Cross Section 72405.2
END DESCRIPTION:
XS GIS Cut Line= 6
      3110906.27     13891630.37       3110921.2     13890936.16
      3110890.81     13889892.88      3110880.68     13889528.24
      3110840.17     13888677.42      3110374.22     13887461.92
#Sta/Elev= 30
  3134.8    77.3  3644.8    75.4  3774.8      76  3829.2    75.8  3879.2    76.3
  4159.2    75.3  4729.2    74.1  4927.6   72.66  4954.7   74.38  4968.2   66.24
  4980.5   64.85  4989.1   59.16  5002.9   58.25  5010.9   58.72  5013.2   60.54
  5031.7   67.26    5036   72.75  5042.7   73.79  5056.1   74.69  5072.9    75.1
  5102.9    72.8    5358   73.29  5597.7    73.9  5707.7    73.8  5847.7    75.9
  6179.5    75.5  6239.5    74.1  6289.5    75.4  7349.5      77  7391.2    78.6
#Mann= 4 , 1 , 0
  3134.8     .12       0  4954.7    .035       0    5036     .14       0
    5358     .12       0
#XS Ineff= 2 , 0
       0  3879.2    76.3  5847.7       0    75.9
Permanent Ineff=
       F       F
Bank Sta=4954.7,5036
XS Rating Curve= 0
Exp/Cntr=.3,.1

Type RM Length L Ch R = 1 ,71854.2 ,968.9,1110,1262.6
BEGIN DESCRIPTION:
Cross Section 71854.2
END DESCRIPTION:
XS GIS Cut Line= 6
      3111445.37     13892614.03      3111579.57     13890449.97
      3111458.03     13889700.43      3111326.35     13889426.95
      3111113.64     13888819.22      3110495.77     13887360.66
#Sta/Elev= 30
  1906.6    76.7  2282.9   76.04  4074.9      75  4354.9      73  4834.2    73.1
  4907.3    74.8  4939.1   72.94  4951.2   73.07  4980.8    63.5  4991.5   63.61
    4996   58.44  4999.8   57.83  5003.9   58.43    5005   60.51  5010.1   64.25
  5023.5    64.4  5050.1   61.51  5079.7   66.19  5097.4   73.22  5107.4   72.83
    5131   73.51  5207.7    72.9  5307.7    73.8  5781.6    74.2  6011.6    73.5
  6051.6    74.7  6161.6    75.7  6971.6    76.2  7211.6    77.1  7365.6    78.8
#Mann= 5 , 1 , 0
  1906.6      .2       0  2282.9     .12       0  4951.2    .035       0
  5010.1     .14       0  5107.4     .12       0
Bank Sta=4951.2,5010.1
XS Rating Curve= 0
Exp/Cntr=.3,.1

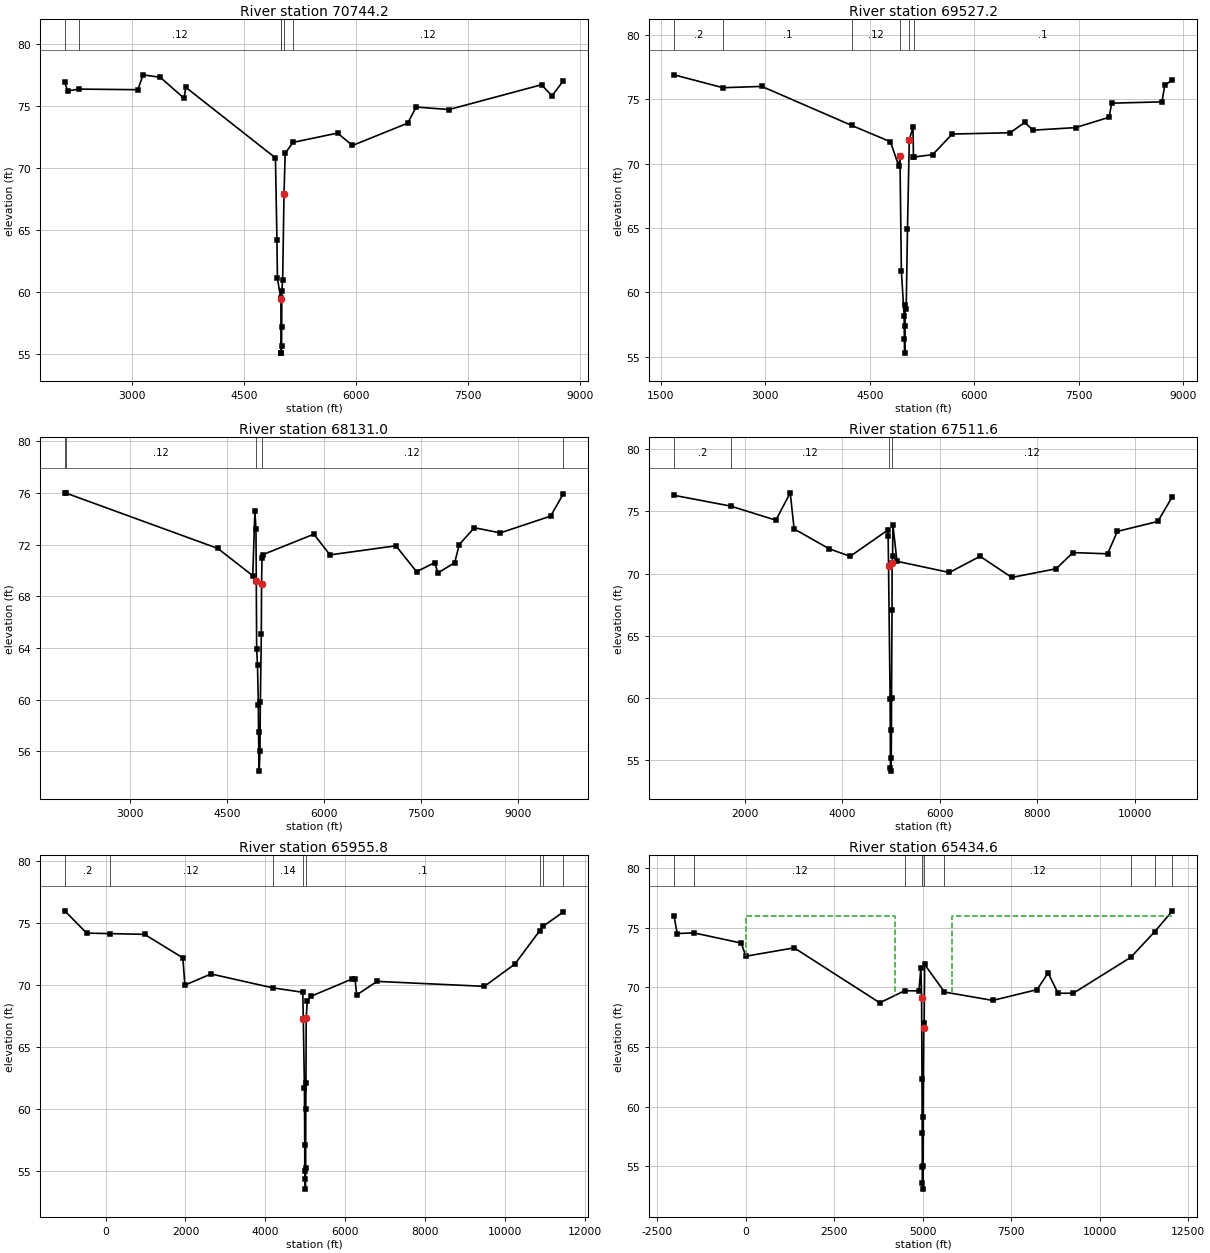
Type RM Length L Ch R = 1 ,70744.2 ,1232.3,1217,594.3
BEGIN DESCRIPTION:
Cross Section 70744.2
END DESCRIPTION:
XS GIS Cut Line= 6
      3111874.42     13892398.08      3112230.07      13891261.4
      3112497.92     13889354.93      3112482.17     13888945.27
      3112197.43     13887796.21      3111066.43     13886183.21
#Sta/Elev= 30
  2096.2    76.9  2136.2    76.2  2281.7   76.35  3076.2    76.3  3146.2    77.5
  3377.2    77.3  3697.2    75.6  3717.2    76.5  4920.5    70.8  4940.2    64.2
    4947   61.08  4990.6   59.49  4994.4    59.4  4997.6   55.08    5000   55.05
  5002.2   55.61  5003.9   57.16  5005.8   60.04    5017   60.97  5035.2    67.9
    5051   71.17  5155.1   72.05  5752.4    72.8  5952.4    71.8  6692.4    73.6
  6806.2    74.9  7246.2    74.7  8486.2    76.7  8626.2    75.8  8776.2      77
#Mann= 6 , 1 , 0
  2096.2      .2       0  2281.7     .12       0  4990.6     .14       0
  4994.4    .039       0  5035.2     .14       0  5155.1     .12       0
Bank Sta=4994.4,5035.2
XS Rating Curve= 0
Exp/Cntr=.3,.1

Type RM Length L Ch R = 1 ,69527.2 ,1287.3,1396.2,1421.1
BEGIN DESCRIPTION:
Cross Section 69527.2, SKEW ANGLE OF 30 DEGREES
END DESCRIPTION:
XS GIS Cut Line= 6
      3112267.34     13892807.92      3113285.72     13890993.55
      3113522.06     13890457.85      3113459.04       13889544.
      3113065.14     13888882.25      3111722.96     13886425.93
#Sta/Elev= 30
  1690.7    76.9  2393.3    75.9  2950.7      76  4239.7   72.97  4796.8    71.7
 4917.44   69.78 4932.92    70.6 4952.93   61.68 4992.69   58.17 4995.48   56.39
 5000.87   55.28 5005.92   57.41 5007.57   59.05 5022.27   58.71 5040.89   64.95
  5066.9   71.87  5119.8   72.82  5126.8    70.5  5128.8   70.51  5402.8    70.7
  5682.8    72.3  6512.9    72.4  6722.9    73.2  6842.9    72.6  7452.2    72.8
  7932.2    73.6  7972.2    74.7  8692.2    74.8  8732.2    76.1  8842.2    76.5
#Mann= 6 , 1 , 0
  1690.7      .2       0  2393.3      .1       0  4239.7     .12       0
 4932.92    .039       0  5066.9     .12       0  5128.8      .1       0
Bank Sta=4932.92,5066.9
XS Rating Curve= 0
Exp/Cntr=.3,.1

Type RM Length L Ch R = 1 ,68131.0 ,621.3,619.4,618.7
BEGIN DESCRIPTION:
Cross Section 68131.0
END DESCRIPTION:
XS GIS Cut Line= 6
      3113049.05     13892285.84      3113364.42     13891833.73
      3114157.07     13890977.67      3114593.03     13890256.35
      3114624.74     13888964.33      3111937.65     13886197.97
#Sta/Elev= 30
  1988.9      76    2008   75.98  4356.8    71.7  4898.8   69.59  4931.6   74.59
  4948.4   73.17  4953.1    69.2  4959.2   63.91    4972   62.67    4985    59.6
  4987.6   57.49    4998   54.47  5010.2   56.06  5016.2   59.81  5031.1   65.05
  5034.8   68.98  5041.5   70.95  5056.4   71.22  5843.7    72.8  6093.7    71.2
  7113.7    71.9  7433.7    69.9  7713.7    70.6  7763.7    69.8  8023.7    70.6
  8093.7      72  8328.1    73.3  8728.1    72.9  9508.1    74.2  9701.6    75.9
#Mann= 5 , 1 , 0
  1988.9      .2       0    2008     .12       0  4953.1    .035       0
  5034.8     .12       0  9701.6      .2       0
Bank Sta=4953.1,5034.8
XS Rating Curve= 0
Exp/Cntr=.3,.1

Type RM Length L Ch R = 1 ,67511.6 ,1594.9,1555.8,1047.3
BEGIN DESCRIPTION:
Cross Section 67511.6
END DESCRIPTION:
XS GIS Cut Line= 6
      3112583.49      13893547.1      3114924.35     13890741.46
      3115255.22     13889827.61      3115066.15     13888913.76
      3113459.04     13887070.31      3112227.61     13885223.16
#Sta/Elev= 30
   551.6    76.3    1719   75.43  2641.6    74.3  2936.2    76.5  3016.2    73.6
  3736.2      72  4166.2    71.4  4935.6    73.5  4944.5   73.01  4952.6   70.66
  4985.2   59.91  4991.9   54.37  5000.4   54.14  5008.7   55.18  5012.8   57.48
  5014.4   59.99  5023.8   67.11  5026.4   70.86  5036.2   71.39  5042.3   73.93
  5125.6      71  6200.7    70.1  6830.7    71.4  7480.7    69.7  8390.7    70.4
  8736.3    71.7  9446.3    71.6  9646.3    73.4 10476.3    74.2 10776.3    76.2
#Mann= 4 , 1 , 0
   551.6      .2       0    1719     .12       0  4952.6    .035       0
  5026.4     .12       0
Bank Sta=4952.6,5026.4
XS Rating Curve= 0
Exp/Cntr=.3,.1

Type RM Length L Ch R = 1 ,65955.8 ,871.7,521.2,373.6
BEGIN DESCRIPTION:
Cross Section 65955.8
END DESCRIPTION:
XS GIS Cut Line= 6
      3113317.24     13894554.41      3115932.73     13891986.18
        3116626.     13890158.48      3116610.24     13889607.02
      3116499.95     13889087.07       3112434.9     13884974.76
#Sta/Elev= 30
 -1024.9      76  -474.9    74.2   102.3   74.16   975.1    74.1  1935.1    72.2
  1985.1      70  2640.7    70.9  4184.9   69.78  4939.4   69.42  4951.6   67.29
  4980.9   61.69    4988   57.11  4988.7   55.01  4990.5   54.35    5007   53.52
  5011.3   55.21  5014.2   59.97  5018.9   62.06  5024.9   67.38  5052.5    68.7
  5147.1    69.1  6178.7    70.5  6248.7    70.5  6288.7    69.2  6798.7    70.3
  9488.7    69.9 10253.6    71.7 10874.1   74.39 10963.4   74.76 11462.5    75.9
#Mann= 8 , 1 , 0
 -1024.9      .2       0   102.3     .12       0  4184.9     .14       0
  4951.6    .035       0  5024.9      .1       0 10874.1     .07       0
 10963.4      .1       0 11462.5      .2       0
Bank Sta=4951.6,5024.9
XS Rating Curve= 0
Exp/Cntr=.3,.1

Type RM Length L Ch R = 1 ,65434.6 ,762.1,1160.9,2542.5
BEGIN DESCRIPTION:
Cross Section 65434.6
END DESCRIPTION:
XS GIS Cut Line= 6
      3114962.25     13896395.18      3116685.05     13893920.88
      3116970.11     13892013.84      3117066.58     13889556.24
      3115070.91     13887101.13      3112625.63     13884581.16
#Sta/Elev= 30
 -2026.9      76 -1936.9    74.5 -1458.5   74.55  -126.9    73.7     3.1    72.6
  1368.1    73.3  3786.3    68.7  4488.8   69.71  4893.7    69.7  4946.5   71.65
  4967.7   69.06  4978.7   62.34  4984.7   57.84  4986.4   54.94  4988.6    53.6
  5010.6    53.1  5013.5   55.06  5015.4   59.15  5029.4    66.6  5040.3   66.99
  5053.5   71.91  5613.8    69.6  6977.3    68.9  8227.3    69.8  8541.2    71.2
  8821.2    69.5  9251.2    69.5   10877   72.51 11551.9   74.65 12052.6    76.4
#Mann= 9 , 1 , 0
 -2026.9     .12       0 -1458.5     .12       0  4488.8     .14       0
  4967.7    .035       0  5029.4     .14       0  5613.8     .12       0
   10877     .07       0 11551.9      .1       0 12052.6      .2       0
#XS Ineff= 2 , 0
       0    4208      76    5814       0      76
Permanent Ineff=
       F       F
Bank Sta=4967.7,5029.4
XS Rating Curve= 0
Exp/Cntr=.5,.3