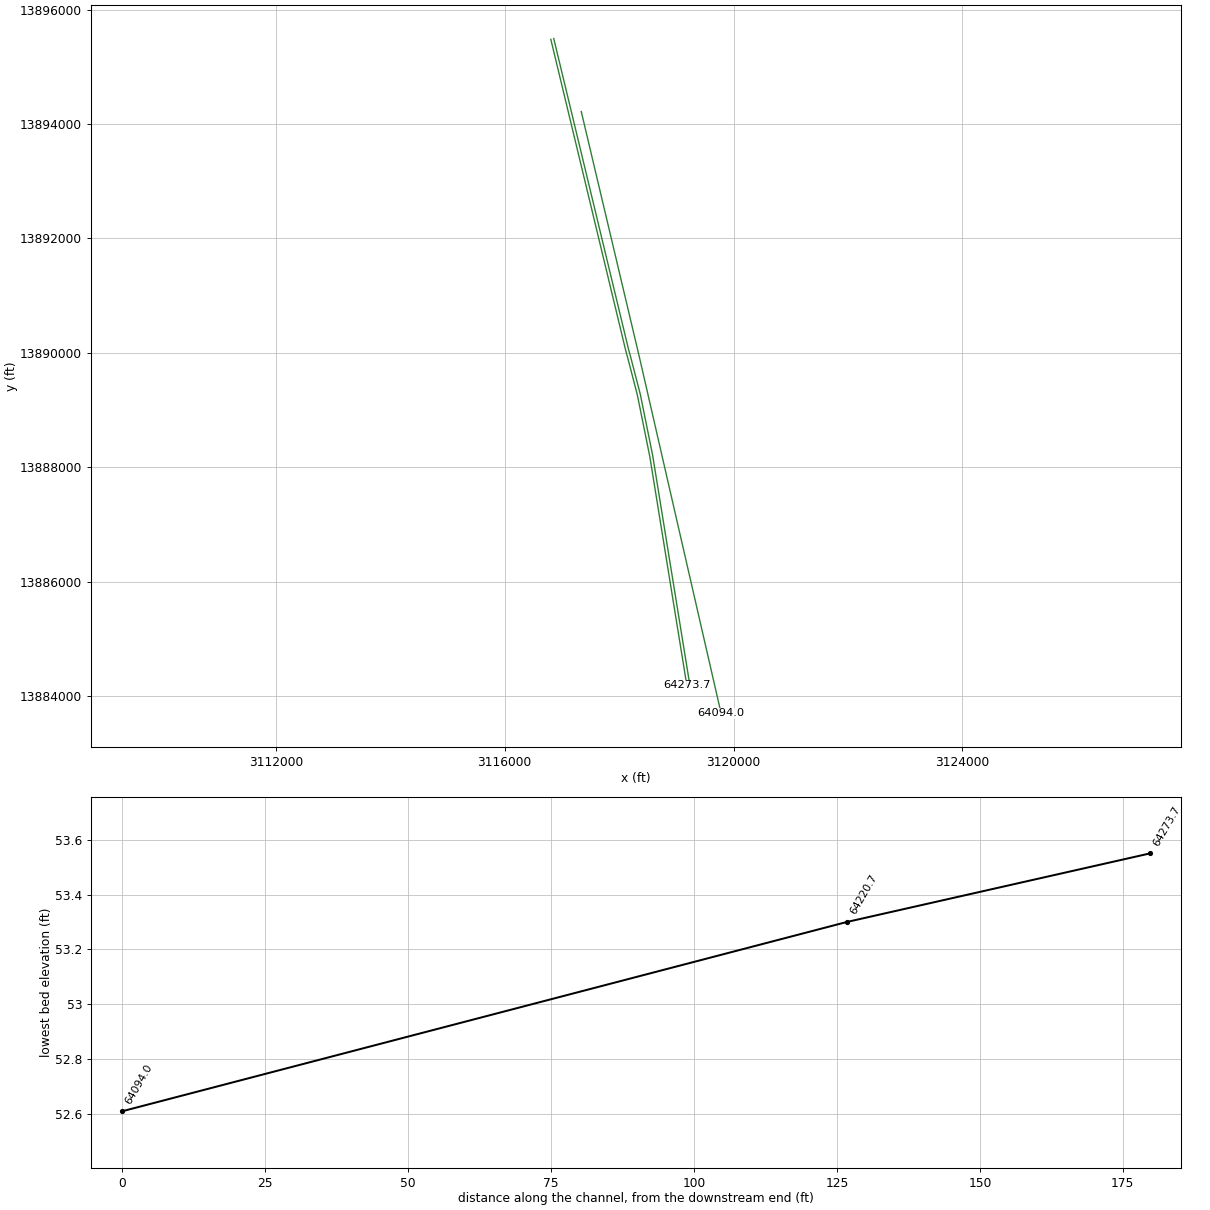
HEC-RAS study P118-00-00.PRJ: P118-00-00

--- P118-00-00.g01 (geometry) --- (continued)

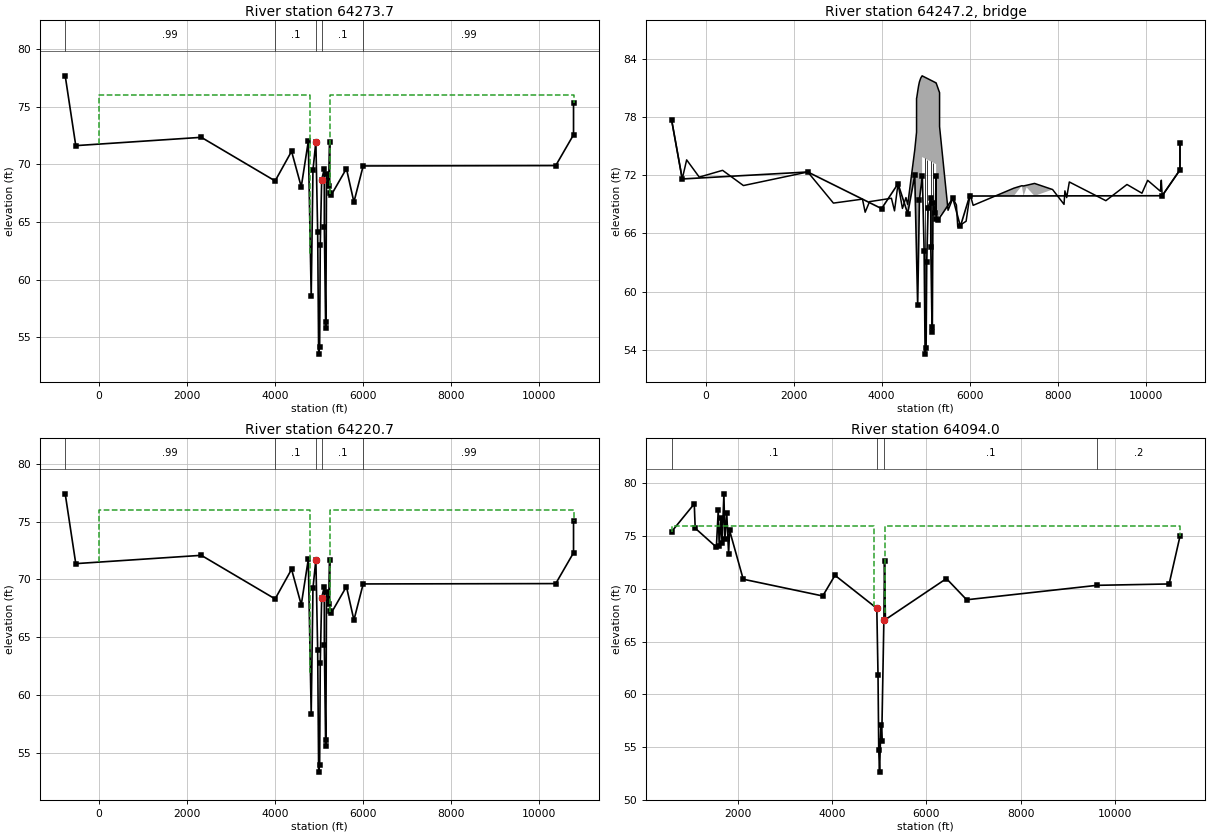
Type RM Length L Ch R = 1 ,64273.7 ,53,53,53
BEGIN DESCRIPTION:
Upstream Section of Bridge/Culvert/Weir
END DESCRIPTION:
XS GIS Cut Line= 6
      3116805.34      13895481.2      3118113.04     13890047.68
      3118150.12      13889912.2      3118318.14     13889263.61
       3118534.7     13888191.98       3119182.9     13884188.96
#Sta/Elev= 30
  -768.8   77.67  -528.8   71.62  2323.1   72.34    4000   68.56  4373.3   71.13
  4593.3   68.05  4753.3   71.99  4819.5   58.58  4859.5    69.5  4925.3   71.96
  4966.3   64.17  4988.6   53.55  5010.9   54.15  5025.3   63.03  5056.9   68.64
  5116.9   69.63  5117.7   64.58  5147.8   55.82  5152.8   56.36  5167.4   69.12
  5220.4   68.12  5238.3    71.9  5239.4    67.5  5279.4   67.37  5619.8   69.63
  5789.8   66.73    6000   69.86 10374.4   69.89 10778.7   72.56 10778.8    75.3
#Mann= 5 , 1 , 0
  -768.8     .99       0    4000      .1       0  4925.3    .035       0
  5056.9      .1       0    6000     .99       0
#XS Ineff= 2 , 0
       0    4802      76    5249       0      76
Permanent Ineff=
       F       F
Bank Sta=4925.3,5056.9
XS Rating Curve= 0
Exp/Cntr=.5,.3

Type RM Length L Ch R = 3 ,64247.2 ,,,
BEGIN DESCRIPTION:
HARDY ROAD
Structure ID: P18-31
END DESCRIPTION:
Bridge Culvert--1,0,-1,-1, 0
Deck Dist Width WeirC Skew NumUp NumDn MinLoCord MaxHiCord MaxSubmerge Is_Ogee
10,33,2.6,0, 60, 60, , , .95, 0, 1,1,,
  -768.8  -528.8  -428.8  -142.2   387.8   861.1  2323.1  2905.5  3565.5  3626.5
  3726.5  4223.3  4293.3  4373.3  4473.3  4553.3  4593.3  4753.3  4779.5 4793.99
  4794.1  4799.5  4819.5  4839.5  4859.5  4889.5  4919.5 4920.41  4920.5 5238.39
  5238.5  5239.4    5317 5317.11  5509.8  5619.8  5699.8  5729.8  5919.8  6009.8
  6079.8  7004.4  7184.4  7224.4  7294.4  7474.4  7884.4  8144.4  8164.4  8204.4
  8264.4  9094.4  9574.4  9914.4 10044.4 10334.4 10354.4 10374.4 10778.7 10778.8
   77.67   71.62   73.59   71.81   72.51   70.94   72.34   69.13   69.54   68.19
   69.28   69.63   68.33   71.14   68.58    69.7   68.99   74.61   75.79   76.44
   79.94   80.03   80.64   81.21   81.64   82.03   82.25   82.26   82.26   81.53
   81.53   81.52   80.52   77.02   68.39   69.64   68.93   66.69   67.26   70.05
    68.9   70.67   70.92    70.9   70.97   71.16   70.53      69   70.39    69.7
   71.31   69.38   71.05   70.15   71.48   70.35   71.49   69.89   72.56    75.3
   77.67   71.62   73.59   71.81   72.51   70.94   72.34   68.99   69.53   67.59
   69.27   69.62   68.32   71.13   68.57   69.69   68.05   71.99   67.52   62.37
   62.33   60.41   58.58   65.89    69.5   71.35   69.76   70.11   73.88   73.15
    71.1    67.5   67.86   67.86   68.17   69.63   68.92   66.53   67.23   70.04
   68.89   69.38   70.91   69.41   70.75   68.69   70.53      69   70.39    69.7
   71.31   69.38   71.05   70.15   71.48   70.35   71.49   69.89   72.56    75.3
  -768.8  -528.8  -428.8  -142.2   387.8   861.1  2323.1  2905.5  3565.5  3626.5
  3726.5  4223.3  4293.3  4373.3  4473.3  4553.3  4593.3  4753.3  4779.5 4793.99
  4794.1  4799.5  4819.5  4839.5  4859.5  4889.5  4919.5 4920.41  4920.5 5238.39
  5238.5  5239.4    5317 5317.11  5509.8  5619.8  5699.8  5729.8  5919.8  6009.8
  6079.8  7004.4  7184.4  7224.4  7294.4  7474.4  7884.4  8144.4  8164.4  8204.4
  8264.4  9094.4  9574.4  9914.4 10044.4 10334.4 10354.4 10374.4 10778.7 10778.8
   77.67   71.62   73.59   71.81   72.51   70.94   72.34   69.13   69.54   68.19
   69.28   69.63   68.33   71.14   68.58    69.7   68.99   74.61   75.79   76.44
   79.94   80.03   80.64   81.21   81.64   82.03   82.25   82.26   82.26   81.53
   81.53   81.52   80.52   77.02   68.39   69.64   68.93   66.69   67.26   70.05
    68.9   70.67   70.92    70.9   70.97   71.16   70.53      69   70.39    69.7
   71.31   69.38   71.05   70.15   71.48   70.35   71.49   69.89   72.56    75.3
   77.48   71.43    73.4   71.62   72.32   70.75   72.15    68.8   69.34    67.4
   69.08   69.43   68.13   70.94   68.38    69.5   67.86    71.8   67.33   62.18
   62.14   60.22   58.39    65.7   69.31   71.16   69.57   69.92   73.69   72.96
   70.91   67.31   67.67   67.67   67.98   69.44   68.73   66.34   67.04   69.85
    68.7   69.19   70.72   69.22   70.56    68.5   70.34   68.81    70.2   69.51
   71.12   69.19   70.86   69.96   71.29   70.16    71.3    69.7   72.37   75.11
Pier Skew, UpSta & Num, DnSta & Num=  ,4981, 2 ,4981, 2 , 0 , 0 , 0 ,,
     1.3     1.3
   56.76   74.67
     1.3     1.3
   56.57   74.48
Pier Skew, UpSta & Num, DnSta & Num=  ,5042, 2 ,5042, 2 , 0 , 0 , 0 ,,
     1.3     1.3
   64.99   74.55
     1.3     1.3
    64.8   74.36
Pier Skew, UpSta & Num, DnSta & Num=  ,5117.7, 2 ,5117.7, 2 , 0 , 0 , 0 ,,
     1.3     1.3
   63.38   74.33
     1.3     1.3
   63.19   74.14
Pier Skew, UpSta & Num, DnSta & Num=  ,5178.1, 2 ,5178.1, 2 , 0 , 0 , 0 ,,
     1.3     1.3
   68.67   74.15
     1.3     1.3
   68.48   73.96
Abutment Skew #Up #Dn= , 2 , 2
  4920.3  4945.3
   73.88   66.42
  4920.3  4945.3
   73.69   66.23
Abutment Skew #Up #Dn= , 2 , 2
  5220.4 5238.59
   68.12   73.15
  5220.4 5238.59
   67.93   72.96
BR Coef= 1 , 1 , 0 ,1.25, 0 ,,,.8,0,2,0,
WSPro=,,,, 1 ,,,, 0 ,,,, 0 ,,,,-1 ,-1 ,-1 , 0 , 0 , 0 , 0 , 0
BR U #Sta/Elev= 30
  -768.8   77.67  -528.8   71.62  2323.1   72.34    4000   68.56  4373.3   71.13
  4593.3   68.05  4753.3   71.99  4819.5   58.58  4859.5    69.5  4925.3   71.96
  4966.3   64.17  4988.6   53.55  5010.9   54.15  5025.3   63.03  5056.9   68.64
  5116.9   69.63  5117.7   64.58  5147.8   55.82  5152.8   56.36  5167.4   69.12
  5220.4   68.12  5238.3    71.9  5239.4    67.5  5279.4   67.37  5619.8   69.63
  5789.8   66.73    6000   69.86 10374.4   69.89 10778.7   72.56 10778.8    75.3
BR U #Mann= 5
  -768.8     .99    4000      .1  4925.3    .035  5056.9      .1    6000     .99
BR U Banks=4925.3,5056.9
BR D #Sta/Elev= 30
  -768.8   77.48  -528.8   71.43  2323.1   72.15    4000   68.37  4373.3   70.94
  4593.3   67.86  4753.3    71.8  4819.5   58.39  4859.5   69.31  4925.3   71.77
  4966.3   63.98  4988.6   53.36  5010.9   53.96  5025.3   62.84  5056.9   68.45
  5116.9   69.44  5117.7   64.39  5147.8   55.63  5152.8   56.17  5167.4   68.93
  5220.4   67.93  5238.3   71.71  5239.4   67.31  5279.4   67.18  5619.8   69.44
  5789.8   66.54    6000   69.67 10374.4    69.7 10778.7   72.37 10778.8   75.11
BR D #Mann= 5
  -768.8     .99    4000      .1  4925.3    .035  5056.9      .1    6000     .99
BR D Banks=4925.3,5056.9
BC Design=,, 0 ,, 0 ,,,,,,

Type RM Length L Ch R = 1 ,64220.7 ,126.7,126.7,126.7
BEGIN DESCRIPTION:
Downstream Section of Bridge/Culvert/Weir
END DESCRIPTION:
XS GIS Cut Line= 6
      3116856.69     13895494.32      3118164.38      13890060.8
      3118201.46     13889925.32      3118369.48     13889276.73
      3118586.04      13888205.1      3119234.25     13884202.08
#Sta/Elev= 30
  -768.8   77.42  -528.8   71.37  2323.1   72.09    4000   68.31  4373.3   70.88
  4593.3    67.8  4753.3   71.74  4819.5   58.33  4859.5   69.25  4925.3   71.71
  4966.3   63.92  4988.6    53.3  5010.9    53.9  5025.3   62.78  5056.9   68.39
  5116.9   69.38  5117.7   64.33  5147.8   55.57  5152.8   56.11  5167.4   68.87
  5220.4   67.87  5238.3   71.65  5239.4   67.25  5279.4   67.12  5619.8   69.38
  5789.8   66.48    6000   69.61 10374.4   69.64 10778.7   72.31 10778.8   75.05
#Mann= 5 , 1 , 0
  -768.8     .99       0    4000      .1       0  4925.3    .035       0
  5056.9      .1       0    6000     .99       0
#XS Ineff= 2 , 0
       0    4802      76    5249       0      76
Permanent Ineff=
       F       F
Bank Sta=4925.3,5056.9
XS Rating Curve= 0
Exp/Cntr=.5,.3

Type RM Length L Ch R = 1 ,64094.0 ,70,70,70
BEGIN DESCRIPTION:
Upstream Section of Bridge/Culvert/Weir
END DESCRIPTION:
XS GIS Cut Line= 3
       3117337.4     13894218.86      3118352.38     13889931.17
      3119782.33     13883698.08
#Sta/Elev= 30
   586.6   75.43  1066.6   78.06  1086.6   75.75  1536.6   73.95  1576.6   77.48
  1596.6   74.03  1636.6   76.73  1656.6   74.36  1696.6   79.01  1716.6   74.75
  1756.6   77.19  1796.6    73.3  1816.6   75.55  2106.6   70.91  3796.4   69.32
  4056.4   71.28  4945.4   68.15    4971   61.84  4986.7    54.7  5003.8   52.61
    5032   57.06  5049.1   55.61  5095.7   67.05  5109.6   72.62  5128.2   67.08
  6424.5   70.97  6854.5   68.96  9623.9   70.33 11156.9   70.46 11387.8   74.99
#Mann= 4 , 1 , 0
   586.6      .1       0  4945.4    .035       0  5095.7      .1       0
  9623.9      .2       0
#XS Ineff= 2 , 0
       0    4896      76    5126       0      76
Permanent Ineff=
       F       F
Bank Sta=4945.4,5095.7
XS Rating Curve= 0
Exp/Cntr=.5,.3