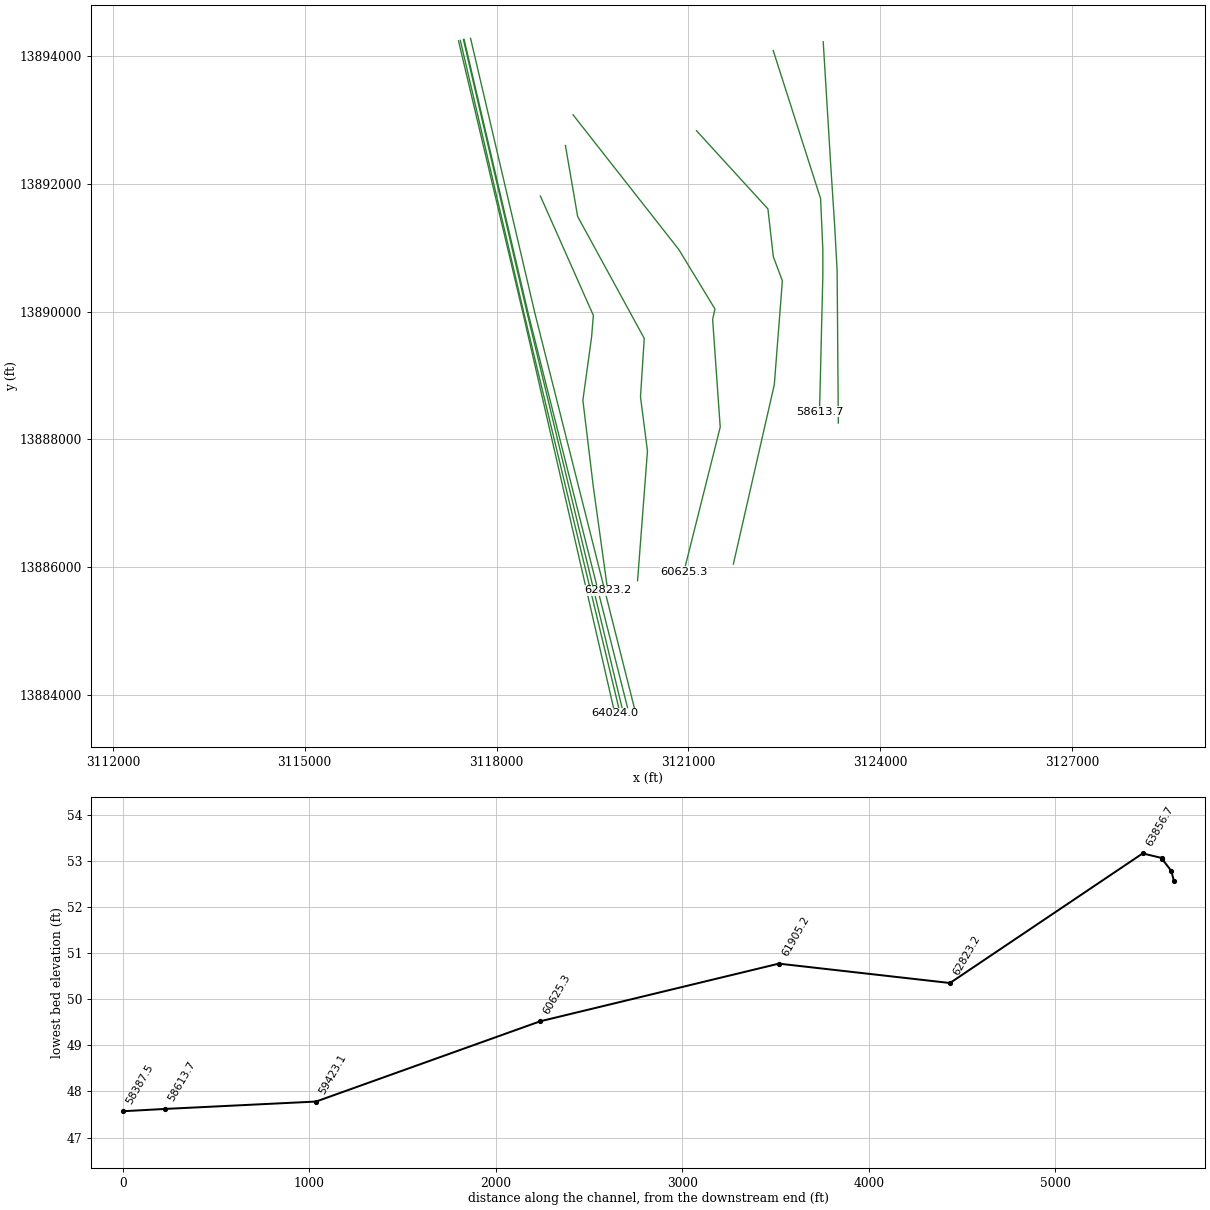
HEC-RAS study P118-00-00.PRJ: P118-00-00

--- P118-00-00.g01 (geometry) --- (continued)

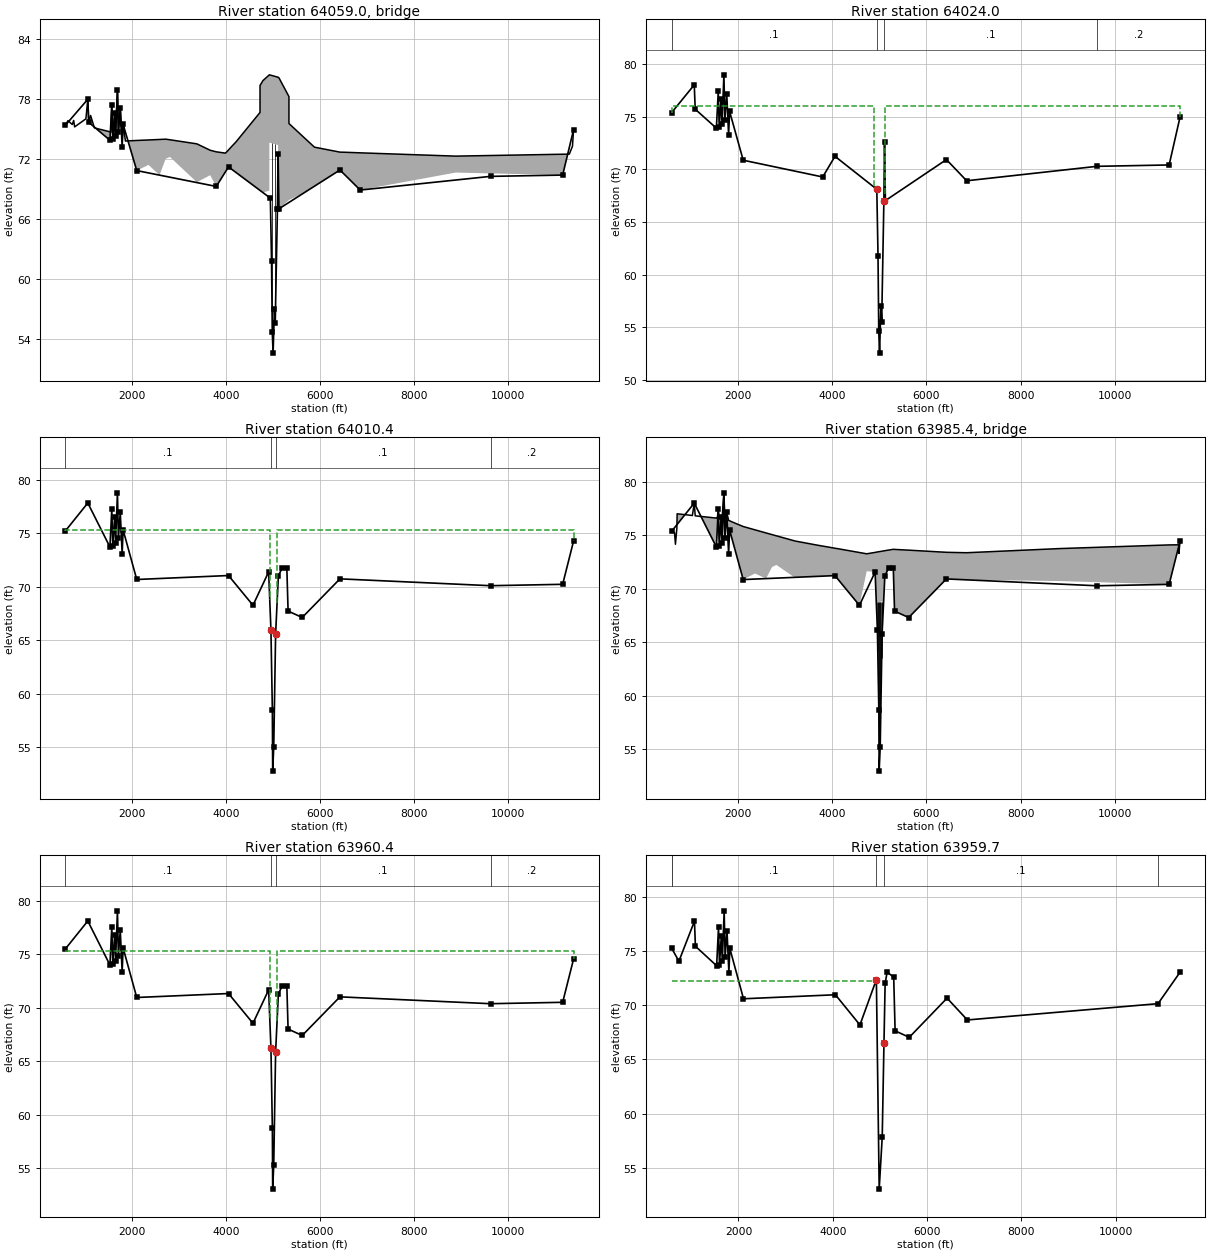
Type RM Length L Ch R = 3 ,64059.0 ,,,
BEGIN DESCRIPTION:
WEST HARDY TOLL ROAD
Structure ID: P18-30
END DESCRIPTION:
Bridge Culvert--1,0,-1,-1, 0
Deck Dist Width WeirC Skew NumUp NumDn MinLoCord MaxHiCord MaxSubmerge Is_Ogee
10,50,2.6,0, 60, 60, , , .95, 0, 1,1,,
   586.6   646.6   666.6   696.6   736.6   766.6   786.6  1026.6  1066.6  1086.6
  1126.6  1206.6  1536.6  1556.6  1576.6  1596.6  1616.6  1636.6  1656.6  1696.6
  1716.6  1756.6  1796.6  1816.6  1866.6  1936.6  2106.6  2356.6  2591.3  2721.3
  2811.3  3384.1  3666.4  3796.4  3991.9  4016.4  4056.4  4126.4  4216.4 4725.99
  4726.1  4787.9 4924.01  4924.1  4925.2  5110.1  5110.5  5128.2  5340.8 5340.91
  5664.5  5882.4  6424.5  6514.5  6854.5  8883.1 11156.9 11297.9 11365.4 11387.8
   75.37   75.86   75.77   75.64   75.47   75.88   75.23   76.04   78.01    75.7
   76.37   75.13   74.74   74.69   77.43   74.59   74.54   76.68   74.44   78.96
    74.7   77.14   73.78    75.5   73.81   73.83   73.87   73.92   73.97      74
   73.94   73.53   72.89   72.73    72.6   72.72   72.92   73.28   73.73   76.68
   79.38   79.87   80.45   80.45   80.45   80.21    80.2   80.15   78.27   75.57
   74.15    73.2    72.7   72.69   72.63    72.3   72.49    72.5   73.29   74.93
   75.37   75.26   74.15   75.62   74.31   75.87   75.01   76.03      78   75.69
   76.36   75.12   73.89   74.56   77.42   73.97    74.3   76.67    74.3   78.95
   74.69   77.13   73.24   75.49   73.73    73.7   70.85   71.42   69.77   72.03
   72.22   69.68   70.39   69.26   70.86   69.95   71.22    69.6   70.44   67.87
   67.87   67.47   68.85   73.65   73.65   73.41   72.29   67.02    67.9    67.9
   67.33   68.49   70.91   69.05    68.9   70.65    70.4   72.18   73.29   74.93
   586.6   646.6   666.6   696.6   736.6   766.6   786.6  1026.6  1066.6  1086.6
  1126.6  1206.6  1536.6  1556.6  1576.6  1596.6  1616.6  1636.6  1656.6  1696.6
  1716.6  1756.6  1796.6  1816.6  1866.6  1936.6  2106.6  2356.6  2591.3  2721.3
  2811.3  3384.1  3666.4  3796.4  3991.9  4016.4  4056.4  4126.4  4216.4 4725.99
  4726.1  4787.9 4924.01  4924.1  4925.2  5110.1  5110.5  5128.2  5340.8 5340.91
  5664.5  5882.4  6424.5  6514.5  6854.5  8883.1 11156.9 11297.9 11365.4 11387.8
   75.37   75.86   75.77   75.64   75.47   75.88   75.23   76.04   78.01    75.7
   76.37   75.13   74.74   74.69   77.43   74.59   74.54   76.68   74.44   78.96
    74.7   77.14   73.78    75.5   73.81   73.83   73.87   73.92   73.97      74
   73.94   73.53   72.89   72.73    72.6   72.72   72.92   73.28   73.73   76.68
   79.38   79.87   80.45   80.45   80.45   80.21    80.2   80.15   78.27   75.57
   74.15    73.2    72.7   72.69   72.63    72.3   72.49    72.5   73.29   74.93
   75.22   75.11      74   75.47   74.16   75.72   74.86   75.88   77.85   75.54
   76.21   74.97   73.74   74.41   77.27   73.82   74.15   76.52   74.15    78.8
   74.54   76.98   73.09   75.34   73.58   73.55    70.7   71.27   69.62   71.88
   72.07   69.53   70.24   69.11   70.71    69.8   71.07   69.45   70.29   67.72
   67.72   67.32    68.7    73.5    73.5   73.26   72.14   66.87   67.75   67.75
   67.18   68.34   70.76    68.9   68.75    70.5   70.25   72.03   73.14   74.78
Pier Skew, UpSta & Num, DnSta & Num=  ,4986.9, 2 ,4986.9, 2 , 0 , 0 , 0 ,,
     1.4     1.4
   53.45   74.57
     1.4     1.4
    53.3   74.42
Pier Skew, UpSta & Num, DnSta & Num=  ,5049.1, 2 ,5049.1, 2 , 0 , 0 , 0 ,,
     1.4     1.4
   54.61   74.49
     1.4     1.4
   54.46   74.34
Abutment Skew #Up #Dn= , 2 , 2
  4923.9  4925.2
   73.65   68.86
  4923.9  4925.2
    73.5   68.71
BR Coef= 1 , 1 , 0 ,1.25, 0 ,,,.8,0,2,0,
WSPro=,,,, 1 ,,,, 0 ,,,, 0 ,,,,-1 ,-1 ,-1 , 0 , 0 , 0 , 0 , 0
BR U #Sta/Elev= 30
   586.6   75.37  1066.6      78  1086.6   75.69  1536.6   73.89  1576.6   77.42
  1596.6   73.97  1636.6   76.67  1656.6    74.3  1696.6   78.95  1716.6   74.69
  1756.6   77.13  1796.6   73.24  1816.6   75.49  2106.6   70.85  3796.4   69.26
  4056.4   71.22  4945.4   68.09    4971   61.78  4986.7   54.64  5003.8   52.55
    5032      57  5049.1   55.55  5095.7   66.99  5109.6   72.56  5128.2   67.02
  6424.5   70.91  6854.5    68.9  9623.9   70.27 11156.9    70.4 11387.8   74.93
BR U #Mann= 4
   586.6      .1  4945.4    .035  5095.7      .1  9623.9      .2
BR U Banks=4945.4,5095.7
BR D #Sta/Elev= 30
   586.6   75.22  1066.6   77.85  1086.6   75.54  1536.6   73.74  1576.6   77.27
  1596.6   73.82  1636.6   76.52  1656.6   74.15  1696.6    78.8  1716.6   74.54
  1756.6   76.98  1796.6   73.09  1816.6   75.34  2106.6    70.7  3796.4   69.11
  4056.4   71.07  4945.4   67.94    4971   61.63  4986.7   54.49  5003.8    52.4
    5032   56.85  5049.1    55.4  5095.7   66.84  5109.6   72.41  5128.2   66.87
  6424.5   70.76  6854.5   68.75  9623.9   70.12 11156.9   70.25 11387.8   74.78
BR D #Mann= 4
   586.6      .1  4945.4    .035  5095.7      .1  9623.9      .2
BR D Banks=4945.4,5095.7
BC Design=,, 0 ,, 0 ,,,,,,

Type RM Length L Ch R = 1 ,64024.0 ,13.6,13.6,13.6
BEGIN DESCRIPTION:
Downstream Section of Bridge/Culvert/Weir
END DESCRIPTION:
XS GIS Cut Line= 3
      3117405.55     13894234.84      3118420.54     13889947.15
      3119850.48     13883714.05
#Sta/Elev= 30
   586.6   75.38  1066.6   78.01  1086.6    75.7  1536.6    73.9  1576.6   77.43
  1596.6   73.98  1636.6   76.68  1656.6   74.31  1696.6   78.96  1716.6    74.7
  1756.6   77.14  1796.6   73.25  1816.6    75.5  2106.6   70.86  3796.4   69.27
  4056.4   71.23  4945.4    68.1    4971   61.79  4986.7   54.65  5003.8   52.56
    5032   57.01  5049.1   55.56  5095.7      67  5109.6   72.57  5128.2   67.03
  6424.5   70.92  6854.5   68.91  9623.9   70.28 11156.9   70.41 11387.8   74.94
#Mann= 4 , 1 , 0
   586.6      .1       0  4945.4    .035       0  5095.7      .1       0
  9623.9      .2       0
#XS Ineff= 2 , 0
       0    4896      76    5126       0      76
Permanent Ineff=
       F       F
Bank Sta=4945.4,5095.7
XS Rating Curve= 0
Exp/Cntr=.5,.3

Type RM Length L Ch R = 1 ,64010.4 ,50,50,50
BEGIN DESCRIPTION:
Upstream Section of Bridge/Culvert/Weir
END DESCRIPTION:
XS GIS Cut Line= 3
      3117433.87     13894241.48      3118435.96     13889943.31
      3119928.97     13883732.48
#Sta/Elev= 30
   586.6   75.21  1066.6   77.84  1536.6   73.73  1576.6   77.26  1596.6   73.81
  1636.6   76.51  1656.6   74.14  1696.6   78.79  1716.6   74.53  1756.6   76.97
  1796.6   73.08  1816.6   75.33  2106.6   70.69  4056.4   71.06  4576.4   68.28
  4909.4    71.4  4958.2   65.93  4988.3   58.48  4995.1   52.78  5017.7   55.04
  5057.6   65.63  5116.2   71.02  5194.3   71.75  5295.6   71.79  5322.5   67.74
  5622.5   67.14  6424.5   70.75  9623.9   70.11 11156.9   70.24 11387.8   74.27
#Mann= 4 , 1 , 0
   586.6      .1       0  4958.2    .035       0  5057.6      .1       0
  9623.9      .2       0
#XS Ineff= 2 , 0
       0  4933.1    75.3  5089.1       0    75.3
Permanent Ineff=
       F       F
Bank Sta=4958.2,5057.6
XS Rating Curve= 0
Exp/Cntr=.5,.3

Type RM Length L Ch R = 3 ,63985.4 ,,,
BEGIN DESCRIPTION:
MISSOURI PACIFIC RAILROAD
Structure ID: P18-29
END DESCRIPTION:
Bridge Culvert--1,0,-1,-1, 0
Deck Dist Width WeirC Skew NumUp NumDn MinLoCord MaxHiCord MaxSubmerge Is_Ogee
10,30,2.6,0, 60, 60, , , .95, 0, 1,1,,
   586.6   646.6   666.6   696.6   702.9   736.6   766.6   786.6  1026.6  1066.6
  1086.6  1126.6  1536.6  1556.6  1576.6  1596.6  1616.6  1636.6  1656.6  1696.6
  1716.6  1756.6  1796.6  1816.6  1866.6  1936.6  2106.6  2356.6  2591.3  2721.3
  2811.3  3164.1  3214.1  3666.4  3796.4  3956.4  3986.4  4016.4  4056.4  4126.4
  4216.4  4576.4 4730.69  4909.4 4942.01  4942.1 5078.89    5079  5116.2  5295.6
  5322.5  5622.5  6424.5  6514.5  6854.5  8842.2 11156.9 11364.9 11365.4 11387.8
   75.37   75.26   74.15   75.62      77   76.98   76.97   76.96   76.84   78.01
   76.81   76.79    76.6   76.59   77.43   76.57   76.56   76.68   76.54   78.96
   76.51   77.14   76.38   76.35   76.25   76.12   75.81    75.5   75.21   75.05
   74.94   74.51   74.45   74.08   73.98   73.86   73.83   73.81   73.78   73.73
   73.66   73.38   73.26   73.39   73.42   73.42   73.52   73.52   73.55   73.68
   73.67    73.6    73.4   73.39   73.36   73.75   74.09    74.1   73.29   74.43
   75.37   75.26   74.15   75.62   75.57   74.31   75.87   75.01   76.03      78
   75.69   76.36   73.89   74.56   77.42   73.97    74.3   76.67    74.3   78.95
   74.69   77.13   73.24   75.49   73.73    73.7   70.85   71.42   69.77   72.03
   72.22   71.15   70.02   70.39   69.26   69.96   71.06   69.95   71.22    69.6
   70.44   68.44   71.63   71.56   67.41   68.71   68.81    67.7   71.18   71.95
    67.9    67.3   70.91   69.05    68.9   70.71    70.4   73.29   73.29   74.43
   586.6   646.6   666.6   696.6   702.9   736.6   766.6   786.6  1026.6  1066.6
  1086.6  1126.6  1536.6  1556.6  1576.6  1596.6  1616.6  1636.6  1656.6  1696.6
  1716.6  1756.6  1796.6  1816.6  1866.6  1936.6  2106.6  2356.6  2591.3  2721.3
  2811.3  3164.1  3214.1  3666.4  3796.4  3956.4  3986.4  4016.4  4056.4  4126.4
  4216.4  4576.4 4730.69  4909.4 4942.01  4942.1 5078.89    5079  5116.2  5295.6
  5322.5  5622.5  6424.5  6514.5  6854.5  8842.2 11156.9 11364.9 11365.4 11387.8
   75.37   75.26   74.15   75.62      77   76.98   76.97   76.96   76.84   78.01
   76.81   76.79    76.6   76.59   77.43   76.57   76.56   76.68   76.54   78.96
   76.51   77.14   76.38   76.35   76.25   76.12   75.81    75.5   75.21   75.05
   74.94   74.51   74.45   74.08   73.98   73.86   73.83   73.81   73.78   73.73
   73.66   73.38   73.26   73.39   73.42   73.42   73.52   73.52   73.55   73.68
   73.67    73.6    73.4   73.39   73.36   73.75   74.09    74.1   73.29   74.43
   75.22   75.11      74   75.47   75.42   74.16   75.72   74.86   75.88   77.85
   75.54   76.21   73.74   74.41   77.27   73.82   74.15   76.52   74.15    78.8
   74.54   76.98   73.09   75.34   73.58   73.55    70.7   71.27   69.62   71.88
   72.07      71   69.87   70.24   69.11   69.81   70.91    69.8   71.07   69.45
   70.29   68.29   71.48   71.41   67.26   68.56   68.66   67.55   71.03    71.8
   67.75   67.15   70.76    68.9   68.75   70.56   70.25   73.14   73.14   74.28
Pier Skew, UpSta & Num, DnSta & Num=  ,4958.2, 2 ,4958.2, 2 , 0 , 0 , 0 ,,
       2       2
   64.94   69.72
       2       2
   64.79   69.57
Pier Skew, UpSta & Num, DnSta & Num=  ,4965.5, 2 ,4965.5, 2 , 0 , 0 , 0 ,,
       2       2
   63.75   69.72
       2       2
    63.6   69.57
Pier Skew, UpSta & Num, DnSta & Num=  ,4978, 2 ,4978, 2 , 0 , 0 , 0 ,,
       2       2
   60.82   69.73
       2       2
   60.67   69.58
Pier Skew, UpSta & Num, DnSta & Num=  ,4992.8, 2 ,4992.8, 2 , 0 , 0 , 0 ,,
       2       2
   52.69   69.75
       2       2
   52.54    69.6
Pier Skew, UpSta & Num, DnSta & Num=  ,4998.7, 2 ,4998.7, 2 , 0 , 0 , 0 ,,
       2       2
   52.04   69.75
       2       2
   51.89    69.6
Pier Skew, UpSta & Num, DnSta & Num=  ,5017.7, 2 ,5017.7, 2 , 0 , 0 , 0 ,,
       2       2
   54.06   69.76
       2       2
   53.91   69.61
Pier Skew, UpSta & Num, DnSta & Num=  ,5021.2, 2 ,5021.2, 2 , 0 , 0 , 0 ,,
       2       2
   54.78   69.76
       2       2
   54.63   69.61
Pier Skew, UpSta & Num, DnSta & Num=  ,5037.1, 2 ,5037.1, 2 , 0 , 0 , 0 ,,
       2       2
   59.09   69.78
       2       2
   58.94   69.63
Pier Skew, UpSta & Num, DnSta & Num=  ,5049, 2 ,5049, 2 , 0 , 0 , 0 ,,
       2       2
   62.91   69.79
       2       2
   62.76   69.64
Pier Skew, UpSta & Num, DnSta & Num=  ,5057.6, 2 ,5057.6, 2 , 0 , 0 , 0 ,,
       2       2
   64.61   69.79
       2       2
   64.46   69.64
Abutment Skew #Up #Dn= , 2 , 2
  5074.4 5079.09
   66.16   68.81
  5074.4 5079.09
   66.01   68.66
BR Coef= 1 , 1 , 0 ,1.25, 0 ,,,.8,-1,2,0,
WSPro=,,,, 1 ,,,, 0 ,,,, 0 ,,,,-1 ,-1 ,-1 , 0 , 0 , 0 , 0 , 0
BR U #Sta/Elev= 30
   586.6   75.37  1066.6      78  1536.6   73.89  1576.6   77.42  1596.6   73.97
  1636.6   76.67  1656.6    74.3  1696.6   78.95  1716.6   74.69  1756.6   77.13
  1796.6   73.24  1816.6   75.49  2106.6   70.85  4056.4   71.22  4576.4   68.44
  4909.4   71.56  4958.2   66.09  4988.3   58.64  4995.1   52.94  5017.7    55.2
  5057.6   65.79  5116.2   71.18  5194.3   71.91  5295.6   71.95  5322.5    67.9
  5622.5    67.3  6424.5   70.91  9623.9   70.27 11156.9    70.4 11387.8   74.43
BR U #Mann= 4
   586.6      .1  4958.2    .035  5057.6      .1  9623.9      .2
BR U Banks=4958.2,5057.6
BR D #Sta/Elev= 30
   586.6   75.22  1066.6   77.85  1536.6   73.74  1576.6   77.27  1596.6   73.82
  1636.6   76.52  1656.6   74.15  1696.6    78.8  1716.6   74.54  1756.6   76.98
  1796.6   73.09  1816.6   75.34  2106.6    70.7  4056.4   71.07  4576.4   68.29
  4909.4   71.41  4958.2   65.94  4988.3   58.49  4995.1   52.79  5017.7   55.05
  5057.6   65.64  5116.2   71.03  5194.3   71.76  5295.6    71.8  5322.5   67.75
  5622.5   67.15  6424.5   70.76  9623.9   70.12 11156.9   70.25 11387.8   74.28
BR D #Mann= 4
   586.6      .1  4958.2    .035  5057.6      .1  9623.9      .2
BR D Banks=4958.2,5057.6
BC Design=,, 0 ,, 0 ,,,,,,

Type RM Length L Ch R = 1 ,63960.4 ,.7,.7,.7
BEGIN DESCRIPTION:
Downstream Section of Bridge/Culvert/Weir
END DESCRIPTION:
XS GIS Cut Line= 3
      3117482.55     13894252.89      3118484.64     13889954.71
      3119977.65     13883743.89
#Sta/Elev= 30
   586.6   75.47  1066.6    78.1  1536.6   73.99  1576.6   77.52  1596.6   74.07
  1636.6   76.77  1656.6    74.4  1696.6   79.05  1716.6   74.79  1756.6   77.23
  1796.6   73.34  1816.6   75.59  2106.6   70.95  4056.4   71.32  4576.4   68.54
  4909.4   71.66  4958.2   66.19  4988.3   58.74  4995.1   53.04  5017.7    55.3
  5057.6   65.89  5116.2   71.28  5194.3   72.01  5295.6   72.05  5322.5      68
  5622.5    67.4  6424.5   71.01  9623.9   70.37 11156.9    70.5 11387.8   74.53
#Mann= 4 , 1 , 0
   586.6      .1       0  4958.2    .035       0  5057.6      .1       0
  9623.9      .2       0
#XS Ineff= 2 , 0
       0  4933.1    75.3  5089.1       0    75.3
Permanent Ineff=
       F       F
Bank Sta=4958.2,5057.6
XS Rating Curve= 0
Exp/Cntr=.5,.3

Type RM Length L Ch R = 1 ,63959.7 ,103,103,103
BEGIN DESCRIPTION:
Upstream Section of Bridge/Culvert/Weir
END DESCRIPTION:
XS GIS Cut Line= 3
       3117492.1     13894259.47      3118497.96      13889961.3
        3120054.     13883786.34
#Sta/Elev= 30
   583.1   75.24   736.6   74.05  1066.6   77.74  1086.6   75.43  1536.6   73.63
  1576.6   77.16  1596.6   73.71  1636.6   76.41  1656.6   74.04  1696.6   78.69
  1716.6   74.43  1756.6   76.87  1796.6   72.98  1816.6   75.23  2106.6   70.59
  4056.4   70.96  4576.4   68.18    4925   72.36  4984.9   53.06    5049   57.85
  5086.2   66.52  5110.8   72.01  5154.1   73.06  5292.6   72.57  5322.5   67.64
  5622.5   67.04  6424.5   70.65  6854.5   68.64 10899.4   70.14 11365.4   73.03
#Mann= 5 , 1 , 0
   583.1      .2       0   583.1      .1       0    4925    .035       0
  5086.2      .1       0 10899.4      .2       0
#XS Ineff= 2 , 0
       0  4925.9    72.2  5121.3       0    72.2
Permanent Ineff=
       F       F
Bank Sta=4925,5086.2
XS Rating Curve= 0
Exp/Cntr=.5,.3

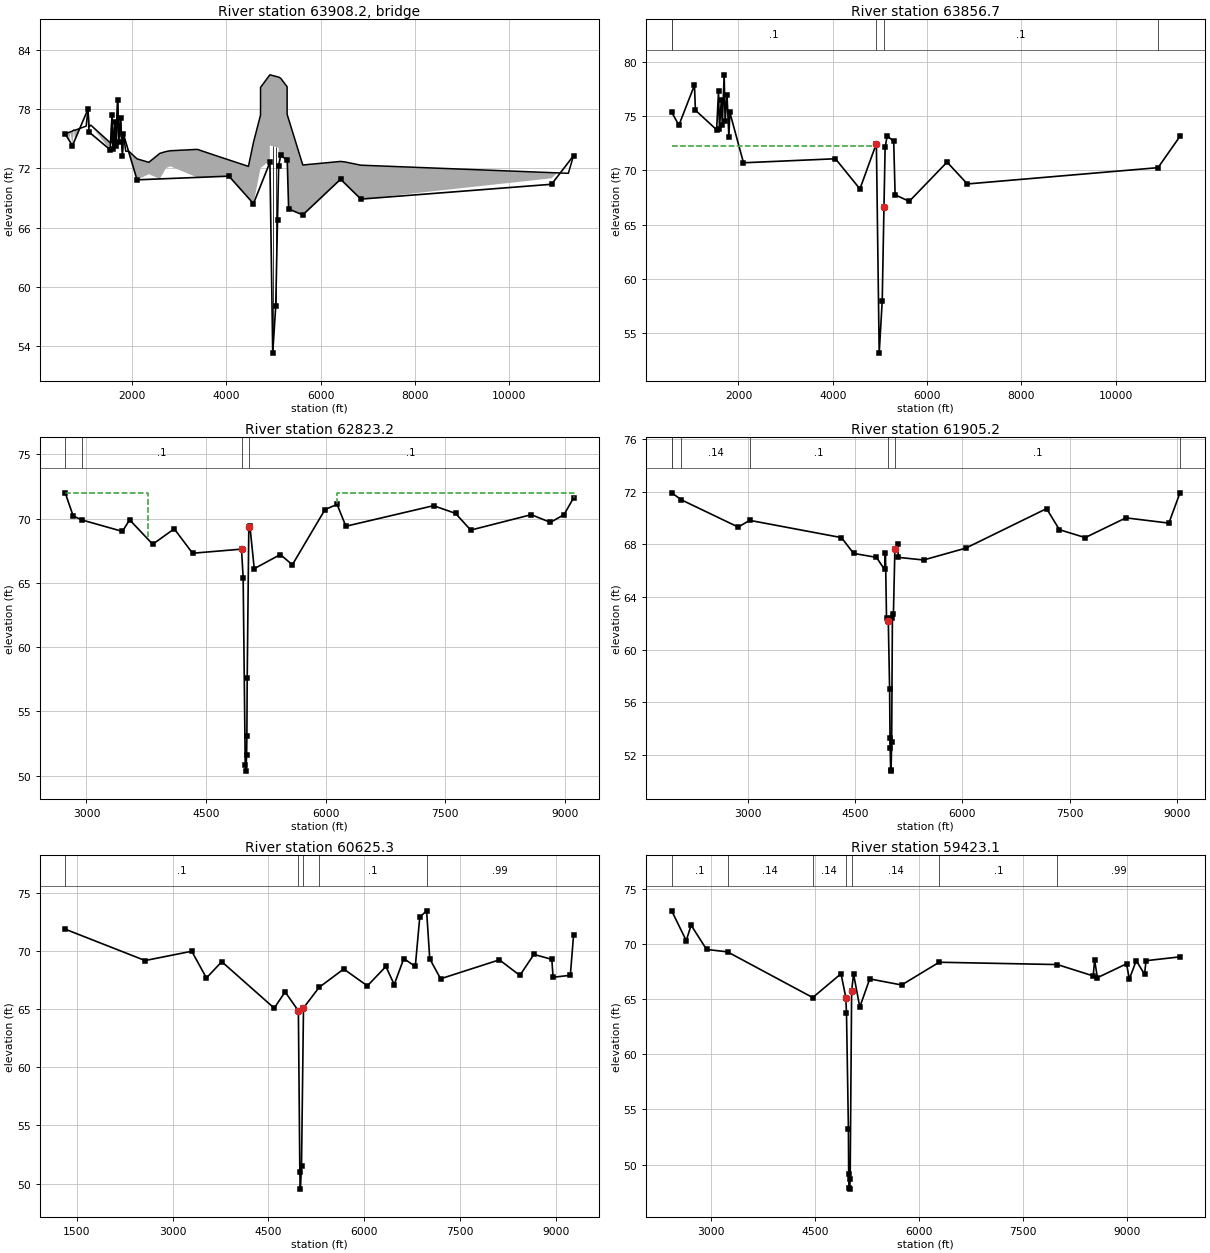
Type RM Length L Ch R = 3 ,63908.2 ,,,
BEGIN DESCRIPTION:
EAST HARDY TOLL ROAD
Structure ID: P18-28
END DESCRIPTION:
Bridge Culvert--1,0,-1,-1, 0
Deck Dist Width WeirC Skew NumUp NumDn MinLoCord MaxHiCord MaxSubmerge Is_Ogee
10,83,2.6,0, 60, 60, , , .95, 0, 1,1,,
   583.1   646.6   666.6   696.6   736.6   766.6   786.6  1026.6  1066.6  1086.6
  1126.6  1536.6  1556.6  1576.6  1596.6  1616.6  1636.6  1656.6  1696.6  1716.6
  1756.6  1796.6  1816.6  1866.6  1936.6  2106.6  2356.6  2591.3  2721.3  2811.3
  3384.1  3666.4  3796.4  3956.4  3986.4  4016.4  4056.4  4126.4  4216.4  4469.6
  4576.4 4726.19  4726.3 4923.61  4923.7 5110.99  5111.1  5111.3  5154.1  5290.3
 5290.41  5292.6  5296.5  5322.5  5622.5  6424.5  6514.5  6854.5 11255.4 11365.4
    75.5   75.61   75.65    75.7   75.77   75.88   75.85   76.27   78.01    76.2
   76.37    74.6   74.57   77.43   74.39   74.32   76.68   74.31   78.96    74.7
   77.14   73.69    75.5   73.74   73.71   72.96   72.61   73.52    73.7   73.78
   73.92   73.47   73.26   73.01   72.96   72.92   72.85   72.74    72.6    72.2
   74.63   77.39   80.19   81.46   81.46   81.23   81.23   81.23   81.11   80.25
   77.45   77.43   77.37   76.97   72.34    72.7   72.65   72.32    71.5   73.29
   75.49   75.25   74.14   75.61    74.3   75.86      75   76.02   77.99   75.68
   76.35   73.88   74.55   77.41   73.96   74.29   76.66   74.29   78.94   74.68
   77.12   73.23   75.48   73.72   73.69   70.84   71.41   69.76   72.02   72.21
   69.67   70.38   69.25   69.95   71.05   69.94   71.21   69.59   70.43   69.03
   68.43   72.02   72.02   72.79   74.31   74.08   71.77   71.45   73.31   72.82
   72.82   72.82   70.42   67.89   67.29    70.9   69.04   68.89   71.18   73.28
   583.1   646.6   666.6   696.6   736.6   766.6   786.6  1026.6  1066.6  1086.6
  1126.6  1536.6  1556.6  1576.6  1596.6  1616.6  1636.6  1656.6  1696.6  1716.6
  1756.6  1796.6  1816.6  1866.6  1936.6  2106.6  2356.6  2591.3  2721.3  2811.3
  3384.1  3666.4  3796.4  3956.4  3986.4  4016.4  4056.4  4126.4  4216.4  4469.6
  4576.4 4726.19  4726.3 4923.61  4923.7 5110.99  5111.1  5111.3  5154.1  5290.3
 5290.41  5292.6  5296.5  5322.5  5622.5  6424.5  6514.5  6854.5 11255.4 11365.4
    75.5   75.61   75.65    75.7   75.77   75.88   75.85   76.27   78.01    76.2
   76.37    74.6   74.57   77.43   74.39   74.32   76.68   74.31   78.96    74.7
   77.14   73.69    75.5   73.74   73.71   72.96   72.61   73.52    73.7   73.78
   73.92   73.47   73.26   73.01   72.96   72.92   72.85   72.74    72.6    72.2
   74.63   77.39   80.19   81.46   81.46   81.23   81.23   81.23   81.11   80.25
   77.45   77.43   77.37   76.97   72.34    72.7   72.65   72.32    71.5   73.29
   75.37   75.13   74.02   75.49   74.18   75.74   74.88    75.9   77.87   75.56
   76.23   73.76   74.43   77.29   73.84   74.17   76.54   74.17   78.82   74.56
      77   73.11   75.36    73.6   73.57   70.72   71.29   69.64    71.9   72.09
   69.55   70.26   69.13   69.83   70.93   69.82   71.09   69.47   70.31   68.91
   68.31    71.9    71.9   72.67   74.19   73.96   71.65   71.33   73.19    72.7
    72.7    72.7    70.3   67.77   67.17   70.78   68.92   68.77   71.06   73.16
Pier Skew, UpSta & Num, DnSta & Num=  ,4984.9, 2 ,4984.9, 2 , 0 , 0 , 0 ,,
     1.4     1.4
   52.34   75.24
     1.4     1.4
   52.22   75.12
Pier Skew, UpSta & Num, DnSta & Num=  ,5049, 2 ,5049, 2 , 0 , 0 , 0 ,,
     1.4     1.4
   57.12   75.16
     1.4     1.4
      57   75.04
Abutment Skew #Up #Dn= , 2 , 2
  4923.5  4925.1
   74.31   72.58
  4923.5  4925.1
   74.19   72.46
BR Coef= 1 , 1 , 0 ,1.25, 0 ,,,.8,0,2,0,
WSPro=,,,, 1 ,,,, 0 ,,,, 0 ,,,,-1 ,-1 ,-1 , 0 , 0 , 0 , 0 , 0
BR U #Sta/Elev= 30
   583.1   75.49   736.6    74.3  1066.6   77.99  1086.6   75.68  1536.6   73.88
  1576.6   77.41  1596.6   73.96  1636.6   76.66  1656.6   74.29  1696.6   78.94
  1716.6   74.68  1756.6   77.12  1796.6   73.23  1816.6   75.48  2106.6   70.84
  4056.4   71.21  4576.4   68.43    4925   72.61  4984.9   53.31    5049    58.1
  5086.2   66.77  5110.8   72.26  5154.1   73.31  5292.6   72.82  5322.5   67.89
  5622.5   67.29  6424.5    70.9  6854.5   68.89 10899.4   70.39 11365.4   73.28
BR U #Mann= 5
   583.1      .2   583.1      .1    4925    .035  5086.2      .1 10899.4      .2
BR U Banks=4925,5086.2
BR D #Sta/Elev= 30
   583.1   75.37   736.6   74.18  1066.6   77.87  1086.6   75.56  1536.6   73.76
  1576.6   77.29  1596.6   73.84  1636.6   76.54  1656.6   74.17  1696.6   78.82
  1716.6   74.56  1756.6      77  1796.6   73.11  1816.6   75.36  2106.6   70.72
  4056.4   71.09  4576.4   68.31    4925   72.49  4984.9   53.19    5049   57.98
  5086.2   66.65  5110.8   72.14  5154.1   73.19  5292.6    72.7  5322.5   67.77
  5622.5   67.17  6424.5   70.78  6854.5   68.77 10899.4   70.27 11365.4   73.16
BR D #Mann= 5
   583.1      .2   583.1      .1    4925    .035  5086.2      .1 10899.4      .2
BR D Banks=4925,5086.2
BC Design=,, 0 ,, 0 ,,,,,,

Type RM Length L Ch R = 1 ,63856.7 ,1033.5,1033.5,1033.5
BEGIN DESCRIPTION:
Downstream Section of Bridge/Culvert/Weir
END DESCRIPTION:
XS GIS Cut Line= 3
      3117594.03     13894274.28      3118599.88      13889976.1
      3120155.93     13883801.15
#Sta/Elev= 30
   583.1   75.34   736.6   74.15  1066.6   77.84  1086.6   75.53  1536.6   73.73
  1576.6   77.26  1596.6   73.81  1636.6   76.51  1656.6   74.14  1696.6   78.79
  1716.6   74.53  1756.6   76.97  1796.6   73.08  1816.6   75.33  2106.6   70.69
  4056.4   71.06  4576.4   68.28    4925   72.46  4984.9   53.16    5049   57.95
  5086.2   66.62  5110.8   72.11  5154.1   73.16  5292.6   72.67  5322.5   67.74
  5622.5   67.14  6424.5   70.75  6854.5   68.74 10899.4   70.24 11365.4   73.13
#Mann= 5 , 1 , 0
   583.1      .2       0   583.1      .1       0    4925    .035       0
  5086.2      .1       0 10899.4      .2       0
#XS Ineff= 2 , 0
       0  4925.9    72.2  5121.3       0    71.9
Permanent Ineff=
       F       F
Bank Sta=4925,5086.2
XS Rating Curve= 0
Exp/Cntr=.5,.3

Type RM Length L Ch R = 1 ,62823.2 ,582.5,918,920.1
BEGIN DESCRIPTION:
Cross Section 62823.2
END DESCRIPTION:
XS GIS Cut Line= 6
      3118686.52     13891806.56      3119514.85     13889940.53
      3119487.54     13889603.73        3119351.     13888611.54
      3119514.85     13887255.23       3119739.1     13885640.67
#Sta/Elev= 30
  2733.6      72  2833.6    70.2    2942   69.89  3451.5      69  3541.5    69.9
  3831.5      68  4101.5    69.2  4331.5    67.3  4945.6   67.62  4966.1   65.37
  4992.2   50.81  4999.2   50.35  5009.6   51.61  5012.7   53.09  5016.9   57.59
    5037   69.33  5050.1   69.45  5105.2    66.1  5433.1    67.2  5583.1    66.4
  5993.1    70.7  6144.7    71.1  6254.7    69.4  7354.7      71  7630.9    70.4
  7820.9    69.1  8580.9    70.3  8820.9    69.7  8990.9    70.3  9110.9    71.6
#Mann= 4 , 1 , 0
  2733.6     .14       0    2942      .1       0  4945.6    .035       0
    5037      .1       0
#XS Ineff= 2 , 0
       0    3771      72    6145       0      72
Permanent Ineff=
       F       F
Bank Sta=4945.6,5037
XS Rating Curve= 0
Exp/Cntr=.3,.1

Type RM Length L Ch R = 1 ,61905.2 ,1276.9,1279.9,1506.1
BEGIN DESCRIPTION:
Cross Section 61905.2
END DESCRIPTION:
XS GIS Cut Line= 6
      3119077.92     13892598.52      3119269.08     13891487.99
      3120311.22     13889580.31      3120252.17     13888666.15
       3120361.4      13887819.6      3120206.66      13885789.7
#Sta/Elev= 30
  1935.7    71.9  2070.4   71.37  2865.7    69.3  3026.6   69.81  4309.2    68.5
  4479.2    67.3  4799.2      67  4911.4   66.08  4924.6   67.34  4939.5   62.36
  4964.3   62.19  4982.8   56.98  4988.5   53.25  4990.7    52.5  4997.3   50.86
  5003.2   50.77  5011.4      53  5021.8   62.37  5035.8   62.67  5056.8   67.66
  5096.5   68.02    5103      67  5457.3    66.8  6047.3    67.7    7177    70.7
    7357    69.1    7717    68.5    8287      70    8887    69.6  9042.8    71.9
#Mann= 7 , 1 , 0
  1935.7      .2       0  1935.7      .1       0  2070.4     .14       0
  3026.6      .1       0  4964.3    .035       0  5056.8      .1       0
  9042.8      .2       0
#XS Ineff= 2 , 0
       0                    7177       0    70.7
Permanent Ineff=
       F       F
Bank Sta=4964.3,5056.8
XS Rating Curve= 0
Exp/Cntr=.3,.1

Type RM Length L Ch R = 1 ,60625.3 ,1401.1,1202.2,1171.2
BEGIN DESCRIPTION:
Cross Section 60625.3
END DESCRIPTION:
XS GIS Cut Line= 6
      3119197.54     13893077.61      3120852.95     13890969.13
      3121417.32     13890040.66      3121380.91     13889876.81
      3121499.53      13888191.8      3120931.85     13885931.98
#Sta/Elev= 30
  1319.3    71.9  2569.3    69.2  3299.3      70  3529.3    67.7  3769.3    69.1
    4590    65.1    4760    66.5    4968   64.87  4990.9   50.99    4999   49.52
  5017.1   51.52  5048.1   65.12  5292.4   66.89  5677.6   68.47  6047.6   67.02
  6337.6   68.69  6467.6   67.13  6617.6   69.37  6797.6   68.69  6867.6   72.94
  6974.5   73.48  7023.7   69.35  7193.7   67.63  8113.7   69.26  8433.7   67.92
  8653.7   69.73  8933.7    69.3  8953.7   67.76  9223.7   67.93  9273.7   71.36
#Mann= 5 , 1 , 0
  1319.3      .1       0    4968    .035       0  5048.1     .14       0
  5292.4      .1       0  6974.5     .99       0
#XS Ineff= 2 , 0
       0                  8113.7       0   69.26
Permanent Ineff=
       F       F
Bank Sta=4968,5048.1
XS Rating Curve= 0
Exp/Cntr=.3,.1

Type RM Length L Ch R = 1 ,59423.1 ,817.4,809.4,725.5
BEGIN DESCRIPTION:
Cross Section 59423.1
END DESCRIPTION:
XS GIS Cut Line= 6
      3121128.23     13892829.56      3122245.66     13891606.32
      3122330.31     13890858.47      3122471.91     13890480.86
      3122345.79     13888857.31      3121705.22      13886049.5
#Sta/Elev= 30
  2439.4      73  2649.4    70.3  2719.4    71.7  2942.1    69.5    3244   69.28
    4471   65.14    4879    67.3  4947.7   65.14  4957.5   63.76  4985.2   53.25
  4988.9   49.19  4993.2   47.84  5004.2   47.78  5010.5   48.71  5031.6   65.75
  5059.4   67.27    5149   64.28  5292.3   66.83  5752.3   66.28  6292.5   68.34
  7994.8   68.13  8511.6    67.1  8531.6   68.55  8571.6   66.94  8991.6    68.2
  9031.6   66.81  9131.6   68.49  9251.6   67.23  9271.6   68.48  9761.6   68.83
#Mann= 7 , 1 , 0
  2439.4      .1       0    3244     .14       0    4471     .14       0
  4947.7    .035       0  5031.6     .14       0  6292.5      .1       0
  7994.8     .99       0
#XS Ineff= 2 , 0
       0                  7071.6       0   67.93
Permanent Ineff=
       F       F
Bank Sta=4947.7,5031.6
XS Rating Curve= 0
Exp/Cntr=.3,.1

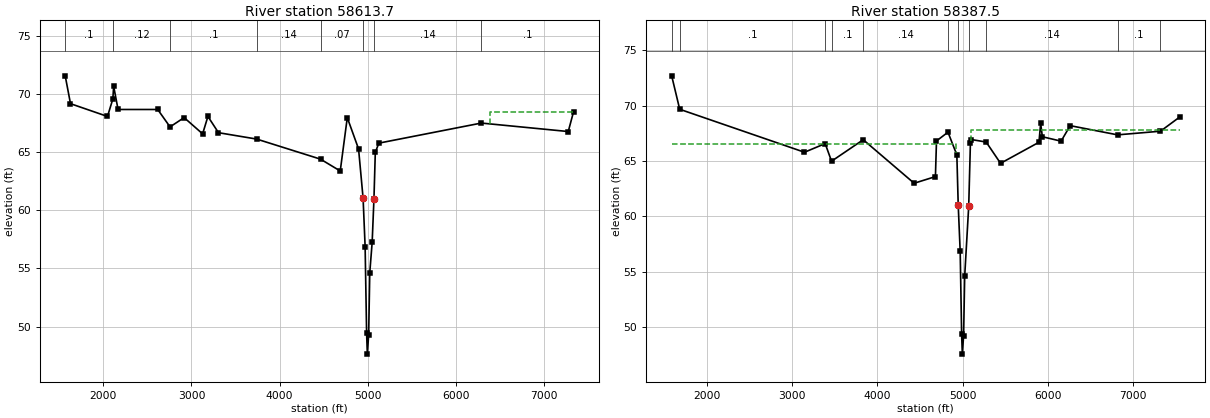
Type RM Length L Ch R = 1 ,58613.7 ,200.1,226.2,255.9
BEGIN DESCRIPTION:
Cross Section 58613.7-Interpolated
END DESCRIPTION:
XS GIS Cut Line= 5
      3122328.58      13894083.6      3123069.87     13891767.05
      3123105.05      13890969.7      3123105.05      13890559.3
      3123053.11     13888429.93
#Sta/Elev= 30
  1566.5    71.6  1626.5    69.2  2046.5    68.1  2107.4   69.61  2116.5    70.7
  2166.5    68.7  2616.5    68.7  2756.6    67.2  2916.5      68  3126.5    66.6
  3186.5    68.1  3306.5    66.7  3740.5   66.15  4465.1   64.42  4688.8    63.4
  4768.8      68  4896.9    65.3  4948.3   61.05  4971.3   56.89  4988.3    49.4
  4996.5   47.62  5011.4   49.29  5024.1   54.65  5051.2   57.25  5071.4   60.97
  5086.9      65  5126.9    65.8  6290.4   67.53  7277.3    66.8  7337.3    68.5
#Mann= 8 , 1 , 0
  1566.5      .1       0  2107.4     .12       0  2756.6      .1       0
  3740.5     .14       0  4465.1     .07       0  4948.3    .035       0
  5071.4     .14       0  6290.4      .1       0
#XS Ineff= 2 , 0
       0  3186.5    68.1  6387.3       0    68.5
Permanent Ineff=
       F       F
Bank Sta=4948.3,5071.4
XS Rating Curve= 0
Exp/Cntr=.5,.3

Type RM Length L Ch R = 1 ,58387.5 ,56,56,56
BEGIN DESCRIPTION:
Upstream Section of Bridge/Culvert/Weir
END DESCRIPTION:
XS GIS Cut Line= 6
      3123110.77     13894220.55      3123230.21     13892259.28
      3123287.97     13891375.77      3123328.34     13890645.35
      3123336.28     13889662.26      3123347.07     13888256.26
#Sta/Elev= 30
  1582.3    72.7  1676.6   69.68  3142.3    65.8  3385.5   66.58  3460.2   64.99
  3832.5   66.93  4430.4      63  4680.4    63.6    4693   66.82  4827.8   67.61
    4932   65.56  4948.3      61  4971.3   56.84  4988.3   49.35  4996.5   47.57
  5011.4   49.24  5024.1    54.6  5071.4   60.92  5091.5   66.66  5100.6   66.95
  5276.6   66.72  5445.4    64.8  5896.5    66.7  5916.5    68.4  5936.5    67.2
  6156.5    66.8  6263.3    68.2  6820.3   67.37  7324.2    67.7  7553.3      69
#Mann= 11 , 1 , 0
  1582.3      .2       0  1676.6      .1       0  3385.5     .14       0
  3460.2      .1       0  3832.5     .14       0  4827.8     .07       0
  4948.3    .035       0  5071.4     .07       0  5276.6     .14       0
  6820.3      .1       0  7324.2      .2       0
#XS Ineff= 2 , 0
       0    4925    66.5  5095.1       0    67.8
Permanent Ineff=
       F       F
Bank Sta=4948.3,5071.4
XS Rating Curve= 0
Exp/Cntr=.5,.3