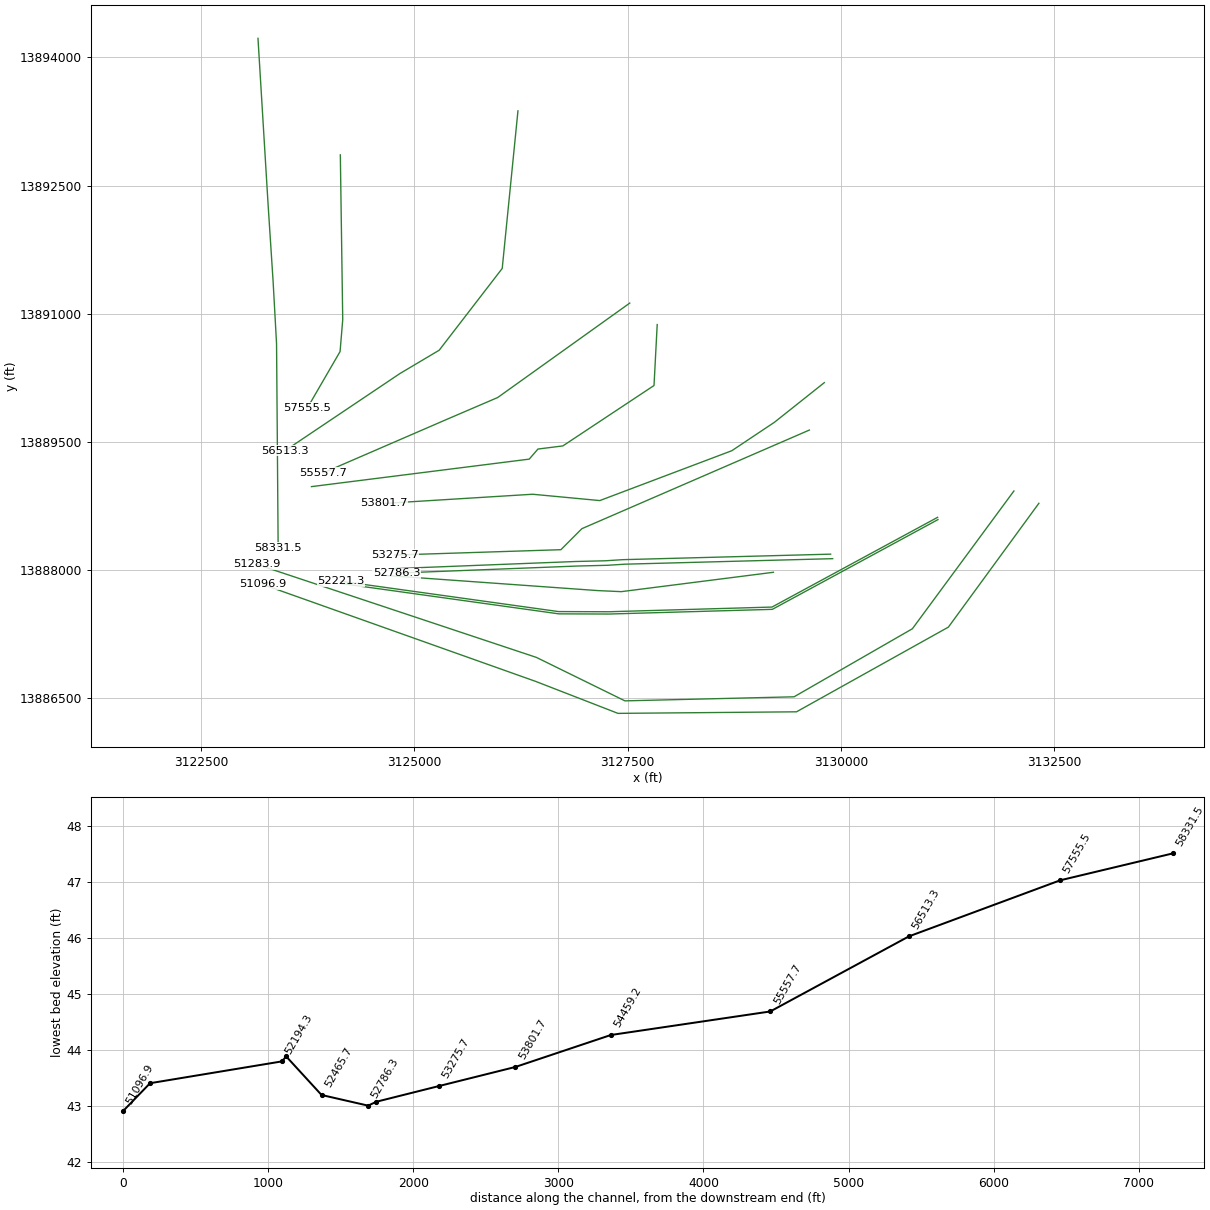
HEC-RAS study P118-00-00.PRJ: P118-00-00

--- P118-00-00.g01 (geometry) --- (continued)

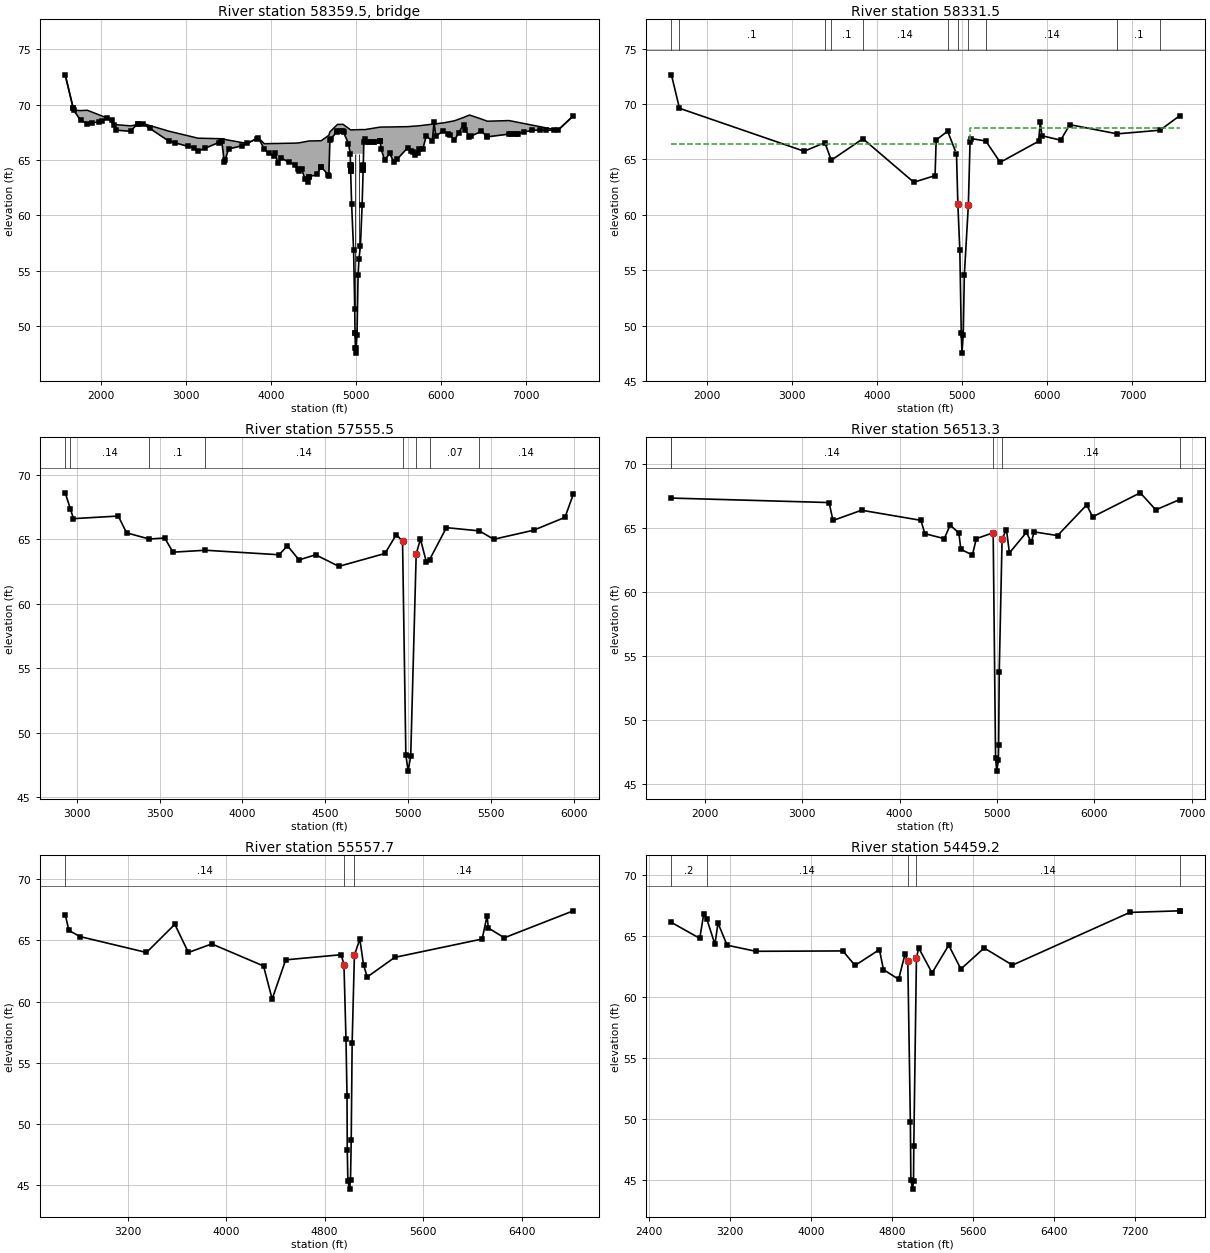
Type RM Length L Ch R = 3 ,58359.5 ,,,
BEGIN DESCRIPTION:
ALDINE-WESTFIELD ROAD
Structure ID: P18-24
END DESCRIPTION:
Bridge Culvert--1,0,-1,-1, 0
Deck Dist Width WeirC Skew NumUp NumDn MinLoCord MaxHiCord MaxSubmerge Is_Ogee
10,36,2.6,0, 60, 60, , , .95, 0, 1,1,,
  1582.3  1682.3  1762.3  1842.3  2072.3  2156.6  2182.3  2352.3  2492.3  2802.3
  3142.3  3422.3  3452.3  3502.3  3717.2  3852.3  3922.3  4050.4  4080.4  4120.4
  4280.4  4330.4  4360.4  4430.4  4450.4  4540.4  4590.4  4680.4    4693  4781.5
  4847.4  4911.3    4932 4935.01  4935.1 5084.99  5085.1  5091.5  5100.6    5283
  5295.4  5335.4  5395.4  5445.4  5605.4  5725.4  5785.4  5825.4  5896.5  5916.5
  5936.5  6026.5  6156.5  6263.3  6333.3  6473.3  6543.3  6797.3  7373.3  7553.3
    72.7   69.51   69.47    69.5   68.81   68.22    68.2   68.09   68.31   67.61
   66.98   66.93   66.88    66.8   66.51   67.01   66.48    66.5    66.5   66.51
   66.53   66.56    66.6    66.7   66.73   66.74   66.75   67.24   67.55   68.22
   68.23   67.87   67.75   67.73   67.73   67.76   67.76   67.75   67.75   67.98
   67.98   67.99   67.99      68   68.02   68.09   68.14   68.18   68.24   68.41
   68.28   68.36   68.55   68.85   69.07   68.71   68.51   68.57    67.7      69
    72.7    69.5    68.6    68.3    68.8   68.16    67.7    67.6    68.3    66.7
    65.8    66.7    64.8      66    66.5      67      66    65.6    64.7    65.2
    64.6      64    64.2      63    63.5    63.7    64.4    63.6   66.82   67.61
   67.61   66.49   65.56   64.53   65.55   65.58    64.5   66.66   66.95   66.72
      66      65    65.6    64.8    66.1    65.6      66    67.2    66.7    68.4
    67.2    67.6    66.8    68.2    67.1    67.6    67.1   67.35    67.7      69
  1582.3  1682.3  1762.3  1842.3  2072.3  2156.6  2182.3  2352.3  2492.3  2802.3
  3142.3  3422.3  3452.3  3502.3  3717.2  3852.3  3922.3  4050.4  4080.4  4120.4
  4280.4  4330.4  4360.4  4430.4  4450.4  4540.4  4590.4  4680.4    4693  4781.5
  4847.4  4911.3    4932 4935.01  4935.1 5084.99  5085.1  5091.5  5100.6    5283
  5295.4  5335.4  5395.4  5445.4  5605.4  5725.4  5785.4  5825.4  5896.5  5916.5
  5936.5  6026.5  6156.5  6263.3  6333.3  6473.3  6543.3  6797.3  7373.3  7553.3
    72.7   69.51   69.47    69.5   68.81   68.22    68.2   68.09   68.31   67.61
   66.98   66.93   66.88    66.8   66.51   67.01   66.48    66.5    66.5   66.51
   66.53   66.56    66.6    66.7   66.73   66.74   66.75   67.24   67.55   68.22
   68.23   67.87   67.75   67.73   67.73   67.76   67.76   67.75   67.75   67.98
   67.98   67.99   67.99      68   68.02   68.09   68.14   68.18   68.24   68.41
   68.28   68.36   68.55   68.85   69.07   68.71   68.51   68.57    67.7      69
   72.65   69.45   68.55   68.25   68.75   68.11   67.65   67.55   68.25   66.65
   65.75   66.65   64.75   65.95   66.45   66.95   65.95   65.55   64.65   65.15
   64.55   63.95   64.15   62.95   63.45   63.65   64.35   63.55   66.77   67.56
   67.56   66.44   65.51   64.48    65.5   65.53   64.45   66.61    66.9   66.67
   65.95   64.95   65.55   64.75   66.05   65.55   65.95   67.15   66.65   68.35
   67.15   67.55   66.75   68.15   67.05   67.55   67.05    67.3   67.65   68.95
Pier Skew, UpSta & Num, DnSta & Num=  ,4984.8, 2 ,4984.8, 2 , 0 , 0 , 0 ,,
     1.2     1.2
   50.19   66.56
     1.2     1.2
   50.14   66.51
Pier Skew, UpSta & Num, DnSta & Num=  ,5034.7, 2 ,5034.7, 2 , 0 , 0 , 0 ,,
     1.2     1.2
   55.02   66.57
     1.2     1.2
   54.97   66.52
Abutment Skew #Up #Dn= , 2 , 2
  4934.9  4936.6
   65.55   63.98
  4934.9  4936.6
    65.5   63.93
Abutment Skew #Up #Dn= , 2 , 2
    5084 5085.19
   64.13   65.58
    5084 5085.19
   64.08   65.53
BR Coef= 1 , 1 , 0 ,1.25, 0 ,,,.8,0,2,0,
WSPro=,,,, 1 ,,,, 0 ,,,, 0 ,,,,-1 ,-1 ,-1 , 0 , 0 , 0 , 0 , 0
BR U #Sta/Elev= 141
  1582.3    72.7  1676.5   69.69  1676.6   69.68  1682.3    69.5  1762.3    68.6
  1842.3    68.3  1896.6   68.36  1976.6   68.46  2012.3    68.5  2072.3    68.8
  2132.3    68.6  2156.6   68.16  2182.3    67.7  2352.3    67.6  2432.3    68.3
  2436.6    68.3  2492.3    68.3  2576.6   67.86  2802.3    66.7  2876.6   66.55
  3026.6   66.24  3092.3    66.1  3142.3    65.8  3226.6   66.07  3385.5   66.58
  3416.6   66.68  3422.3    66.7  3452.3    64.8  3460.2   64.99  3502.3      66
  3662.3    66.3  3717.2    66.5  3832.5   66.93  3852.3      67  3922.3      66
  3972.3    65.6  4030.4    65.4  4050.4    65.6  4080.4    64.7  4120.4    65.2
  4210.4    64.8  4280.4    64.6  4317.2   64.16  4330.4      64  4360.4    64.2
  4400.4    63.3  4430.4      63  4450.4    63.5  4452.6    63.5  4540.4    63.7
  4590.4    64.4  4592.6   64.38  4672.6   63.67  4680.4    63.6    4693   66.82
  4707.4   66.95  4778.5   67.58  4781.5   67.61  4827.8   67.61  4847.4   67.61
  4852.9   67.51  4911.3   66.49    4932   65.56  4934.9   64.56 4935.01   64.53
  4935.1    64.5 4935.19   64.46  4935.3   64.43 4935.41   64.39  4936.5   64.01
  4936.6   63.98  4948.3      61  4971.3   56.84  4984.8   51.57  4988.3   49.35
  4988.7    49.4  4992.2   48.03  4996.5   47.57    5002   48.07  5011.4   49.24
  5024.1    54.6  5034.7    56.1  5051.2    57.2  5071.4   60.92  5083.9    64.1
    5084   64.13 5084.69   64.36  5084.8    64.4 5084.91   64.44 5084.99   64.46
  5085.1    64.5  5085.2   64.53  5091.5   66.66  5100.6   66.95  5148.8   66.62
  5150.5   66.61  5212.5   66.67    5215   66.67  5276.6   66.72  5282.9   66.72
    5283   66.72  5295.4      66  5335.4      65  5395.4    65.6  5445.4    64.8
  5485.4    65.1  5605.4    66.1  5645.4    65.8  5664.2   65.69  5695.4    65.5
  5725.4    65.6  5745.4      66  5785.4      66  5825.4    67.2  5896.5    66.7
  5916.5    68.4  5936.5    67.2  6026.5    67.6  6086.5    67.4  6104.2   67.25
  6156.5    66.8  6207.3   67.47  6263.3    68.2  6283.3    67.7  6333.3    67.1
  6347.3   67.15  6473.3    67.6  6537.3   67.14  6543.3    67.1  6797.3   67.35
  6820.3   67.37  6853.3    67.4  6887.3    67.4  6903.3    67.4  6977.3   67.53
  7073.3    67.7  7157.3    67.7  7233.3    67.7  7324.2    67.7  7373.3    67.7
  7553.3      69
BR U #Mann= 11
  1582.3      .2  1676.6      .1  3385.5     .14  3460.2      .1  3832.5     .14
  4827.8     .07  4948.3    .035  5071.4     .07  5276.6     .14  6820.3      .1
  7324.2      .2
BR U Banks=4948.3,5071.4
BR D #Sta/Elev= 141
  1582.3   72.65  1676.5   69.64  1676.6   69.63  1682.3   69.45  1762.3   68.55
  1842.3   68.25  1896.6   68.31  1976.6   68.41  2012.3   68.45  2072.3   68.75
  2132.3   68.55  2156.6   68.11  2182.3   67.65  2352.3   67.55  2432.3   68.25
  2436.6   68.25  2492.3   68.25  2576.6   67.81  2802.3   66.65  2876.6    66.5
  3026.6   66.19  3092.3   66.05  3142.3   65.75  3226.6   66.02  3385.5   66.53
  3416.6   66.63  3422.3   66.65  3452.3   64.75  3460.2   64.94  3502.3   65.95
  3662.3   66.25  3717.2   66.45  3832.5   66.88  3852.3   66.95  3922.3   65.95
  3972.3   65.55  4030.4   65.35  4050.4   65.55  4080.4   64.65  4120.4   65.15
  4210.4   64.75  4280.4   64.55  4317.2   64.11  4330.4   63.95  4360.4   64.15
  4400.4   63.25  4430.4   62.95  4450.4   63.45  4452.6   63.45  4540.4   63.65
  4590.4   64.35  4592.6   64.33  4672.6   63.62  4680.4   63.55    4693   66.77
  4707.4    66.9  4778.5   67.53  4781.5   67.56  4827.8   67.56  4847.4   67.56
  4852.9   67.46  4911.3   66.44    4932   65.51  4934.9   64.51 4935.01   64.48
  4935.1   64.45 4935.19   64.41  4935.3   64.38 4935.41   64.34  4936.5   63.96
  4936.6   63.93  4948.3   60.95  4971.3   56.79  4984.8   51.52  4988.3    49.3
  4988.7   49.35  4992.2   47.98  4996.5   47.52    5002   48.02  5011.4   49.19
  5024.1   54.55  5034.7   56.05  5051.2   57.15  5071.4   60.87  5083.9   64.05
    5084   64.08 5084.69   64.31  5084.8   64.35 5084.91   64.39 5084.99   64.41
  5085.1   64.45  5085.2   64.48  5091.5   66.61  5100.6    66.9  5148.8   66.57
  5150.5   66.56  5212.5   66.62    5215   66.62  5276.6   66.67  5282.9   66.67
    5283   66.67  5295.4   65.95  5335.4   64.95  5395.4   65.55  5445.4   64.75
  5485.4   65.05  5605.4   66.05  5645.4   65.75  5664.2   65.64  5695.4   65.45
  5725.4   65.55  5745.4   65.95  5785.4   65.95  5825.4   67.15  5896.5   66.65
  5916.5   68.35  5936.5   67.15  6026.5   67.55  6086.5   67.35  6104.2    67.2
  6156.5   66.75  6207.3   67.42  6263.3   68.15  6283.3   67.65  6333.3   67.05
  6347.3    67.1  6473.3   67.55  6537.3   67.09  6543.3   67.05  6797.3    67.3
  6820.3   67.32  6853.3   67.35  6887.3   67.35  6903.3   67.35  6977.3   67.48
  7073.3   67.65  7157.3   67.65  7233.3   67.65  7324.2   67.65  7373.3   67.65
  7553.3   68.95
BR D #Mann= 11
  1582.3      .2  1676.6      .1  3385.5     .14  3460.2      .1  3832.5     .14
  4827.8     .07  4948.3    .035  5071.4     .07  5276.6     .14  6820.3      .1
  7324.2      .2
BR D Banks=4948.3,5071.4
BC Design=,, 0 ,, 0 ,,,,,,

Type RM Length L Ch R = 1 ,58331.5 ,776,776,776
BEGIN DESCRIPTION:
Downstream Section of Bridge/Culvert/Weir
END DESCRIPTION:
XS GIS Cut Line= 6
      3123166.71     13894223.26      3123286.15     13892261.98
      3123343.91     13891378.47      3123384.28     13890648.05
      3123392.22     13889664.96        3123403.     13888258.96
#Sta/Elev= 30
  1582.3   72.64  1676.6   69.62  3142.3   65.74  3385.5   66.52  3460.2   64.93
  3832.5   66.87  4430.4   62.94  4680.4   63.54    4693   66.76  4827.8   67.55
    4932    65.5  4948.3   60.94  4971.3   56.78  4988.3   49.29  4996.5   47.51
  5011.4   49.18  5024.1   54.54  5071.4   60.86  5091.5    66.6  5100.6   66.89
  5276.6   66.66  5445.4   64.74  5896.5   66.64  5916.5   68.34  5936.5   67.14
  6156.5   66.74  6263.3   68.14  6820.3   67.31  7324.2   67.64  7553.3   68.94
#Mann= 11 , 1 , 0
  1582.3      .2       0  1676.6      .1       0  3385.5     .14       0
  3460.2      .1       0  3832.5     .14       0  4827.8     .07       0
  4948.3    .035       0  5071.4     .07       0  5276.6     .14       0
  6820.3      .1       0  7324.2      .2       0
#XS Ineff= 2 , 0
       0    4925    66.4  5095.1       0    67.8
Permanent Ineff=
       F       F
Bank Sta=4948.3,5071.4
XS Rating Curve= 0
Exp/Cntr=.5,.3

Type RM Length L Ch R = 1 ,57555.5 ,1849.8,1042.2,745.7
BEGIN DESCRIPTION:
Cross Section 57555.5
END DESCRIPTION:
XS GIS Cut Line= 4
      3124131.68     13892859.26      3124159.93     13890931.11
      3124128.75     13890556.92      3123747.21     13889899.57
#Sta/Elev= 30
    2931    68.6  2961.8   67.37    2981    66.6    3251    66.8    3301    65.5
  3437.5   65.02    3531    65.1    3581      64  3776.7   64.15    4221    63.8
    4271    64.5    4341    63.4    4441    63.8    4581    62.9  4859.4    63.9
  4927.9   65.37  4965.2   64.83  4985.1   48.29  4998.9   47.03  5014.4   48.19
  5047.5   63.86  5073.1   65.02  5109.4    63.2  5128.8   63.43  5229.4    65.9
  5428.5   65.65  5514.9      65  5754.9    65.7  5944.9    66.7  5994.9    68.5
#Mann= 8 , 1 , 0
    2931      .1       0  2961.8     .14       0  3437.5      .1       0
  3776.7     .14       0  4965.2    .035       0  5047.5     .14       0
  5128.8     .07       0  5428.5     .14       0
Bank Sta=4965.2,5047.5
XS Rating Curve= 0
Exp/Cntr=.3,.1

Type RM Length L Ch R = 1 ,56513.3 ,957.4,955.6,743.4
BEGIN DESCRIPTION:
Cross Section 56513.3
END DESCRIPTION:
XS GIS Cut Line= 5
      3126213.41      13893374.3      3126028.95     13891529.73
      3125290.29     13890572.52      3124830.35     13890299.67
      3123481.72     13889395.39
#Sta/Elev= 30
  1654.5   67.36  3274.5   67.01  3314.5   65.61  3608.3   66.41  4218.3   65.62
  4258.3   64.58  4458.3   64.19  4518.3   65.25  4608.3   64.63  4628.3   63.36
  4747.4   62.91  4787.4   64.19  4960.7   64.65  4985.2   47.09  4997.4   46.03
  5013.9   46.88  5016.7   48.06  5022.9   53.75  5052.3   64.18  5097.4    64.9
  5127.4   63.07  5302.1   64.68  5352.1   63.91  5382.1   64.72  5622.1   64.43
  5922.1   66.83  5982.1   65.89  6472.1   67.77  6632.1   66.44  6875.9   67.24
#Mann= 5 , 1 , 0
  1654.5      .2       0  1654.5     .14       0  4960.7    .035       0
  5052.3     .14       0  6875.9      .2       0
Bank Sta=4960.7,5052.3
XS Rating Curve= 0
Exp/Cntr=.3,.1

Type RM Length L Ch R = 1 ,55557.7 ,1050.7,1098.5,1124.5
BEGIN DESCRIPTION:
Cross Section 55557.7
END DESCRIPTION:
XS GIS Cut Line= 4
      3127523.85     13891124.42      3125976.29     13890019.03
      3125376.04     13889761.78      3123935.03     13889138.45
#Sta/Elev= 30
  2694.1    67.1  2724.1    65.8  2814.1    65.3  3354.1      64  3584.1    66.3
  3694.1      64  3884.1    64.7  4304.1    62.9  4374.1    60.2  4484.1    63.4
  4935.2   63.82  4957.1   62.99  4973.4   56.98  4981.9   52.33  4983.9    47.9
  4988.9   45.33  5003.4   44.69  5010.3   45.46    5016   48.71  5023.6   56.65
  5041.8   63.77  5085.9    65.1  5115.9      63  5145.9      62    5369    63.6
    6079    65.1    6119      67    6129      66    6259    65.2    6819    67.4
#Mann= 3 , 1 , 0
  2694.1     .14       0  4957.1    .035       0  5041.8     .14       0
Bank Sta=4957.1,5041.8
XS Rating Curve= 0
Exp/Cntr=.3,.1

Type RM Length L Ch R = 1 ,54459.2 ,688.7,657.5,499.6
BEGIN DESCRIPTION:
Cross Section 54459.2
END DESCRIPTION:
XS GIS Cut Line= 6
       3127845.3     13890872.89      3127807.98     13890159.51
      3126739.63     13889452.45      3126447.64     13889415.67
      3126345.49     13889297.79      3123793.54     13888975.99
#Sta/Elev= 30
  2620.7   66.08  2900.7   64.78  2940.7   66.81  2970.9   66.34  3050.7   64.29
  3080.7   66.03  3170.7   64.22  3455.1   63.72  4315.1   63.75  4435.1   62.56
  4676.2   63.86  4716.2   62.22  4866.2   61.43  4928.5   63.48  4956.8   62.91
  4982.1   49.76  4986.9   45.02  5003.7   44.27  5013.2   44.93  5015.9   47.76
    5042   63.17  5064.3   63.99  5196.5   61.95  5361.2   64.22  5481.2   62.27
  5711.2   63.99  5991.2   62.59  7151.2    66.9  7642.3   67.03  7642.4   67.03
#Mann= 5 , 1 , 0
  2620.7      .2       0  2970.9     .14       0  4956.8    .035       0
    5042     .14       0  7642.3      .2       0
Bank Sta=4956.8,5042
XS Rating Curve= 0
Exp/Cntr=.3,.1

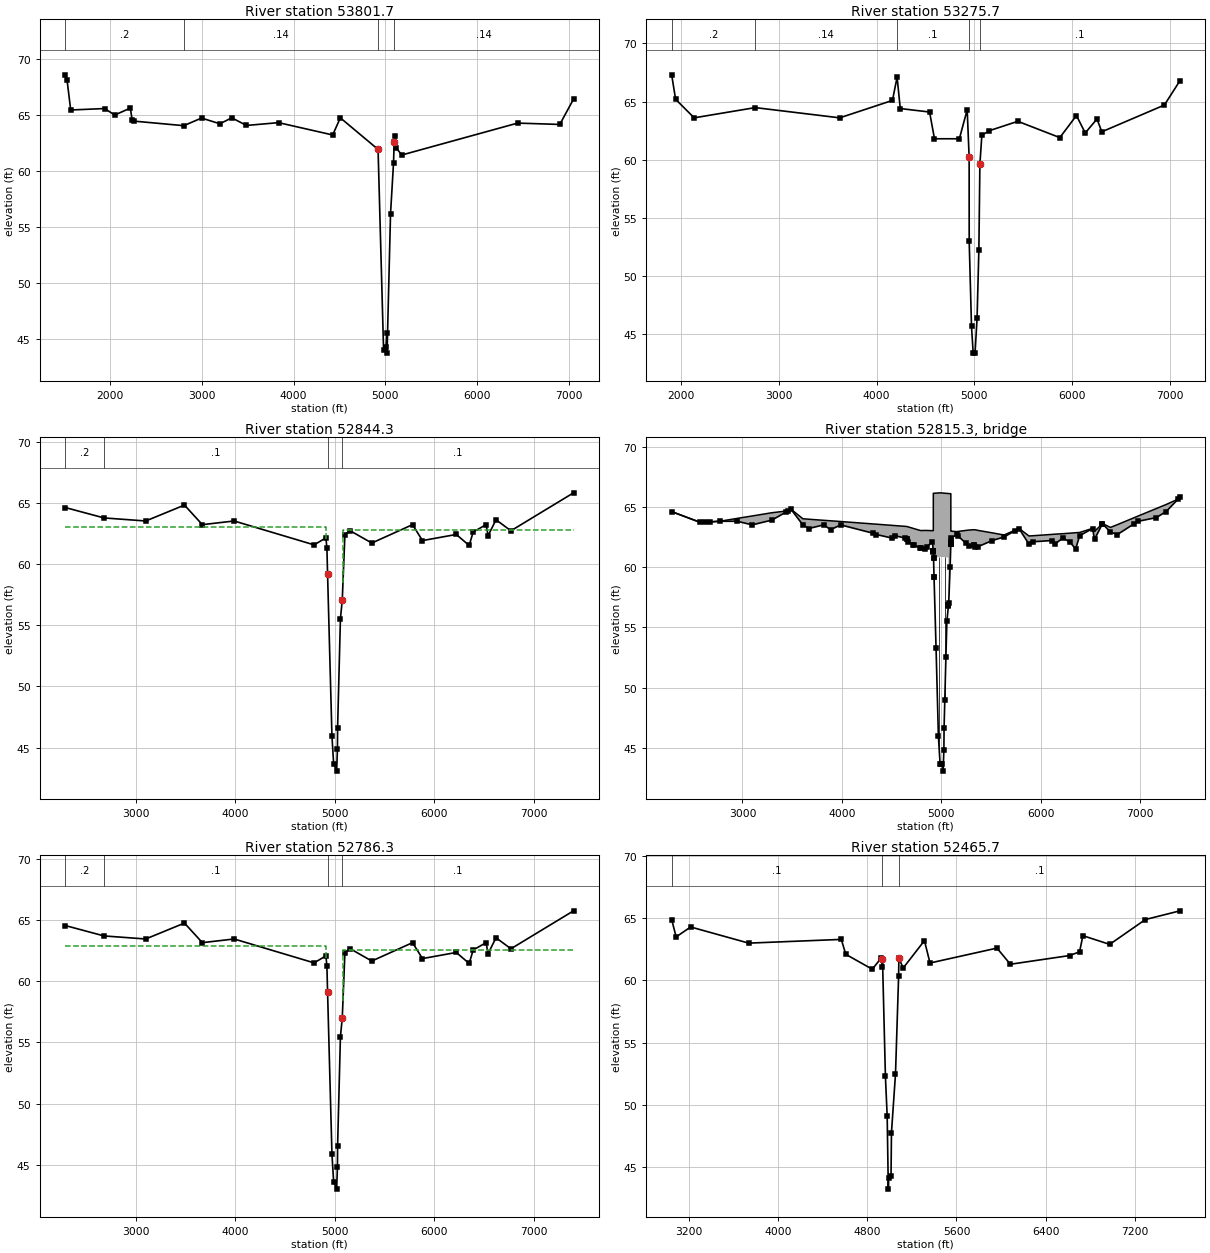
Type RM Length L Ch R = 1 ,53801.7 ,302.1,526,681.2
BEGIN DESCRIPTION:
Cross Section 53801.7-Interpolated
END DESCRIPTION:
XS GIS Cut Line= 6
       3129803.6     13890192.97      3129219.96     13889729.76
      3128719.69     13889396.25      3127172.56      13888812.6
       3126385.1     13888886.71      3124638.44     13888778.89
#Sta/Elev= 30
  1509.6   68.55  1529.6   68.09  1569.6   65.41  1939.6   65.54  2049.6   64.96
  2219.6   65.58  2239.6   64.52  2254.7   64.42  2802.3   64.01    2996   64.69
    3196   64.18    3326   64.71    3486   64.03    3836   64.28    4426   63.18
  4509.5   64.71 4920.96   61.89 4980.96   43.97 5007.66   44.28 5016.86   45.52
 5018.76    43.7 5056.86   56.15 5089.36   60.66 5096.36   62.51  5109.5   63.11
  5119.5   62.02  5179.5   61.39  6442.2   64.24  6902.2   64.12  7052.2   66.38
#Mann= 4 , 1 , 0
  1509.6      .2       0  2802.3     .14       0 4920.96    .035       0
 5096.36     .14       0
Bank Sta=4920.96,5096.36
XS Rating Curve= 0
Exp/Cntr=.3,.1

Type RM Length L Ch R = 1 ,53275.7 ,478.5,431.4,135.4
BEGIN DESCRIPTION:
Cross Section 53275.7-Interpolated
END DESCRIPTION:
XS GIS Cut Line= 4
      3129628.62     13889638.03      3126962.79     13888483.86
      3126716.55     13888237.62      3124767.54     13888175.04
#Sta/Elev= 30
  1902.5    67.3  1942.5    65.2  2132.5    63.6  2757.9   64.48  3622.5    63.6
  4162.5    65.1  4209.9    67.1  4242.5    64.4  4542.5    64.1  4592.5    61.8
  4847.4    61.8  4927.4    64.3  4947.4    60.2 4947.86   52.98 4971.56   45.66
 4988.56   43.38 5007.66   43.36 5028.46   46.34 5046.96   52.24  5057.4    59.6
  5077.4    62.1  5155.7    62.5  5445.7    63.3  5875.7    61.9  6045.7    63.8
  6135.7    62.3  6255.7    63.5  6305.7    62.4  6945.7    64.7  7105.7    66.8
#Mann= 5 , 1 , 0
  1902.5      .2       0  2757.9     .14       0  4209.9      .1       0
  4947.4    .035       0  5057.4      .1       0
#XS Ineff= 2 , 0
       0  4542.5    64.1               0
Permanent Ineff=
       F       F
Bank Sta=4947.4,5057.4
XS Rating Curve= 0
Exp/Cntr=.5,.3

Type RM Length L Ch R = 1 ,52844.3 ,58,58,58
BEGIN DESCRIPTION:
Upstream Section of Bridge/Culvert/Weir
END DESCRIPTION:
XS GIS Cut Line= 6
      3129877.93     13888185.51      3127441.21     13888120.86
      3127237.91     13888107.93       3126887.3      13888099.4
      3124893.32     13888021.23      3124765.88     13888014.95
#Sta/Elev= 30
  2287.5   64.61  2677.8   63.76  3097.5   63.51  3487.5   64.81  3667.5   63.21
  3987.5   63.51  4791.7   61.56    4911   62.13    4921   61.27  4927.4   59.22
  4971.6   45.96  4988.6   43.68  5018.8   43.08  5026.8   44.87  5028.5   46.64
  5056.9   55.53  5075.5   57.06    5102   62.39  5153.6   62.72  5372.6   61.71
  5782.6   63.21  5882.6   61.91  6222.6   62.41  6352.6   61.51  6392.6   62.61
  6522.6   63.21  6542.6   62.31  6622.6   63.61  6772.6   62.71  7402.6   65.81
#Mann= 4 , 1 , 0
  2287.5      .2       0  2677.8      .1       0  4927.4    .035       0
  5075.5      .1       0
#XS Ineff= 2 , 0
       0    4913      63  5082.3       0    62.8
Permanent Ineff=
       F       F
Bank Sta=4927.4,5075.5
XS Rating Curve= 0
Exp/Cntr=.5,.3

Type RM Length L Ch R = 3 ,52815.3 ,,,
BEGIN DESCRIPTION:
BERTRAND STREET
Structure ID: P18-22
END DESCRIPTION:
Bridge Culvert--1,0,-1,-1, 0
Deck Dist Width WeirC Skew NumUp NumDn MinLoCord MaxHiCord MaxSubmerge Is_Ogee
10,38,2.6,0, 59, 59, , , .95, 0, 1,1,,
  2287.5  2577.5  2777.5  2947.5  3097.5  3297.5    3459  3487.5  3607.5  3667.5
  3817.5  3887.5  3987.5  4507.5  4537.5  4637.5  4657.5  4664.9  4791.7  4840.4
    4911 4920.29  4920.4    4921 4922.51  4988.6 5072.69  5072.8  5075.5  5089.4
  5096.7 5096.81    5102  5153.6  5275.7  5328.6  5342.6  5372.6  5512.6  5632.6
  5782.6  5882.6  5922.6  6112.6  6142.6  6222.6  6292.6  6352.6  6392.6  6522.6
  6542.6  6622.6  6702.6  6772.6  6982.6  7162.6  7262.6  7381.5  7402.6
    64.6    63.7   63.81   64.04   64.24   64.51   64.67   64.81   64.01   63.97
   63.88   63.84   63.78   63.46   63.44   63.38   63.36   63.34   63.03   63.04
   63.02   63.02   66.12   66.12   66.12   66.16    66.1    66.1    66.1   66.09
   66.08   62.98   62.98   62.94   63.07    63.1   63.09   63.04   62.84   62.66
   63.21   62.58    62.6   62.71   62.73   62.77   62.81   62.85   62.87   63.21
   62.96   63.61   63.29   63.52   64.24   64.85   65.19   65.63    65.8
    64.6    63.7    63.8    63.8    63.5    63.9   64.66    64.8    63.5    63.2
    63.5    63.1    63.5    62.4    62.6    62.4    62.3   62.05   61.55   61.53
   62.12   61.32   61.31   61.26   60.78   60.85   60.79   56.83   57.05   60.03
   61.91   61.92   62.38   62.71   61.75   61.87    61.7    61.7    62.2    62.5
    63.2    61.9    62.1    62.2    61.9    62.4    62.1    61.5    62.6    63.2
    62.3    63.6    62.9    62.7    63.8    64.1    64.6   65.62    65.8
  2287.5  2577.5  2777.5  2947.5  3097.5  3297.5    3459  3487.5  3607.5  3667.5
  3817.5  3887.5  3987.5  4507.5  4537.5  4637.5  4657.5  4664.9  4791.7  4840.4
    4911 4920.29  4920.4    4921 4922.51  4988.6 5072.69  5072.8  5075.5  5089.4
  5096.7 5096.81    5102  5153.6  5275.7  5328.6  5342.6  5372.6  5512.6  5632.6
  5782.6  5882.6  5922.6  6112.6  6142.6  6222.6  6292.6  6352.6  6392.6  6522.6
  6542.6  6622.6  6702.6  6772.6  6982.6  7162.6  7262.6  7381.5  7402.6
    64.6    63.7   63.81   64.04   64.24   64.51   64.67   64.81   64.01   63.97
   63.88   63.84   63.78   63.46   63.44   63.38   63.36   63.34   63.03   63.04
   63.02   63.02   66.12   66.12   66.12   66.16    66.1    66.1    66.1   66.09
   66.08   62.98   62.98   62.94   63.07    63.1   63.09   63.04   62.84   62.66
   63.21   62.58    62.6   62.71   62.73   62.77   62.81   62.85   62.87   63.21
   62.96   63.61   63.29   63.52   64.24   64.85   65.19   65.63    65.8
   64.53   63.63   63.73   63.73   63.43   63.83   64.59   64.73   63.43   63.13
   63.43   63.03   63.43   62.33   62.53   62.33   62.23   61.98   61.48   61.46
   62.05   61.25   61.24   61.19   60.71   60.78   60.72   56.76   56.98   59.96
   61.84   61.85   62.31   62.64   61.68    61.8   61.63   61.63   62.13   62.43
   63.13   61.83   62.03   62.13   61.83   62.33   62.03   61.43   62.53   63.13
   62.23   63.53   62.83   62.63   63.73   64.03   64.53   65.55   65.73
Pier Skew, UpSta & Num, DnSta & Num=  ,4981, 2 ,4981, 2 , 0 , 0 , 0 ,,
     1.3     1.3
    43.6   61.85
     1.3     1.3
   43.53   61.78
Pier Skew, UpSta & Num, DnSta & Num=  ,5035.8, 2 ,5035.8, 2 , 0 , 0 , 0 ,,
     1.3     1.3
   47.76   61.82
     1.3     1.3
   47.69   61.75
Abutment Skew #Up #Dn= , 2 , 2
  4922.4  4927.5
   60.81   59.18
  4922.4  4927.5
   60.74   59.11
BR Coef= 1 , 1 , 0 ,1.25, 0 ,,,.8,-1,2,0,
WSPro=,,,, 1 ,,,, 0 ,,,, 0 ,,,,-1 ,-1 ,-1 , 0 , 0 , 0 , 0 , 0
BR U #Sta/Elev= 94
  2287.5    64.6  2577.5    63.7    2619   63.72  2677.8   63.75  2777.5    63.8
  2947.5    63.8  3097.5    63.5  3297.5    63.9    3439   64.57    3459   64.66
  3487.5    64.8  3607.5    63.5  3667.5    63.2  3817.5    63.5  3887.5    63.1
  3987.5    63.5  4317.5    62.8  4347.5    62.7  4507.5    62.4  4537.5    62.6
  4637.5    62.4  4654.7   62.31  4657.5    62.3  4664.9   62.05  4718.7   61.87
  4722.2   61.85  4787.1   61.57  4791.7   61.55  4840.4   61.53  4855.6   61.66
    4911   62.12  4919.9   61.35 4920.29   61.32  4920.4   61.31 4920.51    61.3
    4921   61.26 4922.51   60.78  4922.6   60.75  4927.4   59.21  4927.5   59.18
  4947.9   53.27  4971.6   45.95  4988.6   43.67    4994   43.66  5007.7   43.65
  5018.8   43.07  5026.8   44.86  5028.5   46.63  5035.8   48.97    5047   52.53
  5056.9   55.52  5072.4   56.79 5072.69   56.82  5072.8   56.83  5075.5   57.05
  5089.4   60.03  5096.4   61.88 5096.59    61.9  5096.7   61.91 5096.81   61.92
  5099.8   62.18    5102   62.38  5153.6   62.71  5173.6   62.55  5249.2   61.96
  5275.7   61.75  5328.6   61.87    5334    61.8  5342.6    61.7  5372.6    61.7
  5512.6    62.2  5632.6    62.5  5739.5      63  5782.6    63.2  5882.6    61.9
  5922.6    62.1  6112.6    62.2  6142.6    61.9  6222.6    62.4  6292.6    62.1
  6352.6    61.5  6392.6    62.6  6522.6    63.2  6542.6    62.3    6619   63.54
  6622.6    63.6  6702.6    62.9  6772.6    62.7  6942.6    63.6  6982.6    63.8
  7162.6    64.1  7262.6    64.6  7381.5   65.62  7402.6    65.8
BR U #Mann= 4
  2287.5      .2  2677.8      .1  4927.4    .035  5075.5      .1
BR U Banks=4927.4,5075.5
BR D #Sta/Elev= 94
  2287.5   64.53  2577.5   63.63    2619   63.65  2677.8   63.68  2777.5   63.73
  2947.5   63.73  3097.5   63.43  3297.5   63.83    3439    64.5    3459   64.59
  3487.5   64.73  3607.5   63.43  3667.5   63.13  3817.5   63.43  3887.5   63.03
  3987.5   63.43  4317.5   62.73  4347.5   62.63  4507.5   62.33  4537.5   62.53
  4637.5   62.33  4654.7   62.24  4657.5   62.23  4664.9   61.98  4718.7    61.8
  4722.2   61.78  4787.1    61.5  4791.7   61.48  4840.4   61.46  4855.6   61.59
    4911   62.05  4919.9   61.28 4920.29   61.25  4920.4   61.24 4920.51   61.23
    4921   61.19 4922.51   60.71  4922.6   60.68  4927.4   59.14  4927.5   59.11
  4947.9    53.2  4971.6   45.88  4988.6    43.6    4994   43.59  5007.7   43.58
  5018.8      43  5026.8   44.79  5028.5   46.56  5035.8    48.9    5047   52.46
  5056.9   55.45  5072.4   56.72 5072.69   56.75  5072.8   56.76  5075.5   56.98
  5089.4   59.96  5096.4   61.81 5096.59   61.83  5096.7   61.84 5096.81   61.85
  5099.8   62.11    5102   62.31  5153.6   62.64  5173.6   62.48  5249.2   61.89
  5275.7   61.68  5328.6    61.8    5334   61.73  5342.6   61.63  5372.6   61.63
  5512.6   62.13  5632.6   62.43  5739.5   62.93  5782.6   63.13  5882.6   61.83
  5922.6   62.03  6112.6   62.13  6142.6   61.83  6222.6   62.33  6292.6   62.03
  6352.6   61.43  6392.6   62.53  6522.6   63.13  6542.6   62.23    6619   63.47
  6622.6   63.53  6702.6   62.83  6772.6   62.63  6942.6   63.53  6982.6   63.73
  7162.6   64.03  7262.6   64.53  7381.5   65.55  7402.6   65.73
BR D #Mann= 4
  2287.5      .2  2677.8      .1  4927.4    .035  5075.5      .1
BR D Banks=4927.4,5075.5
BC Design=,, 0 ,, 0 ,,,,,,

Type RM Length L Ch R = 1 ,52786.3 ,320.6,320.6,320.6
BEGIN DESCRIPTION:
Downstream Section of Bridge/Culvert/Weir
END DESCRIPTION:
XS GIS Cut Line= 6
      3129901.79     13888132.65      3127465.07       13888068.
      3127261.77     13888055.07      3126911.16     13888046.54
      3124917.18     13887968.37      3124789.75     13887962.08
#Sta/Elev= 30
  2287.5   64.54  2677.8   63.69  3097.5   63.44  3487.5   64.74  3667.5   63.14
  3987.5   63.44  4791.7   61.49    4911   62.06    4921    61.2  4927.4   59.15
  4971.6   45.89  4988.6   43.61  5018.8   43.01  5026.8    44.8  5028.5   46.57
  5056.9   55.46  5075.5   56.99    5102   62.32  5153.6   62.65  5372.6   61.64
  5782.6   63.14  5882.6   61.84  6222.6   62.34  6352.6   61.44  6392.6   62.54
  6522.6   63.14  6542.6   62.24  6622.6   63.54  6772.6   62.64  7402.6   65.74
#Mann= 4 , 1 , 0
  2287.5      .2       0  2677.8      .1       0  4927.4    .035       0
  5075.5      .1       0
#XS Ineff= 2 , 0
       0    4913    62.9  5082.3       0    62.5
Permanent Ineff=
       F       F
Bank Sta=4927.4,5075.5
XS Rating Curve= 0
Exp/Cntr=.5,.3

Type RM Length L Ch R = 1 ,52465.7 ,251.6,244.4,226.9
BEGIN DESCRIPTION:
Cross Section 52465.7-Interpolated
END DESCRIPTION:
XS GIS Cut Line= 4
       3129207.2     13887973.23       3127424.2     13887746.49
        3127147.     13887759.09      3124673.35     13887935.78
#Sta/Elev= 30
  3048.1    64.9  3088.1    63.5  3218.1    64.3  3738.1      63  4568.1    63.3
  4608.1    62.1  4845.5    60.9  4925.5    61.8  4935.5    61.1    4937   61.76
  4963.3   52.27  4979.1   49.07  4989.3    43.2  4992.7   44.09  5013.5   44.24
  5017.5   47.75  5053.6   52.46  5081.6   60.33  5083.9   61.77  5122.9      61
  5312.9    63.2  5362.9    61.4  5962.9    62.6  6082.9    61.3  6612.9      62
  6702.9    62.3  6732.9    63.6  6972.9    62.9  7292.9    64.9  7602.9    65.6
#Mann= 3 , 1 , 0
  3048.1      .1       0    4937    .035       0  5083.9      .1       0
Bank Sta=4937,5083.9
XS Rating Curve= 0
Exp/Cntr=.5,.3

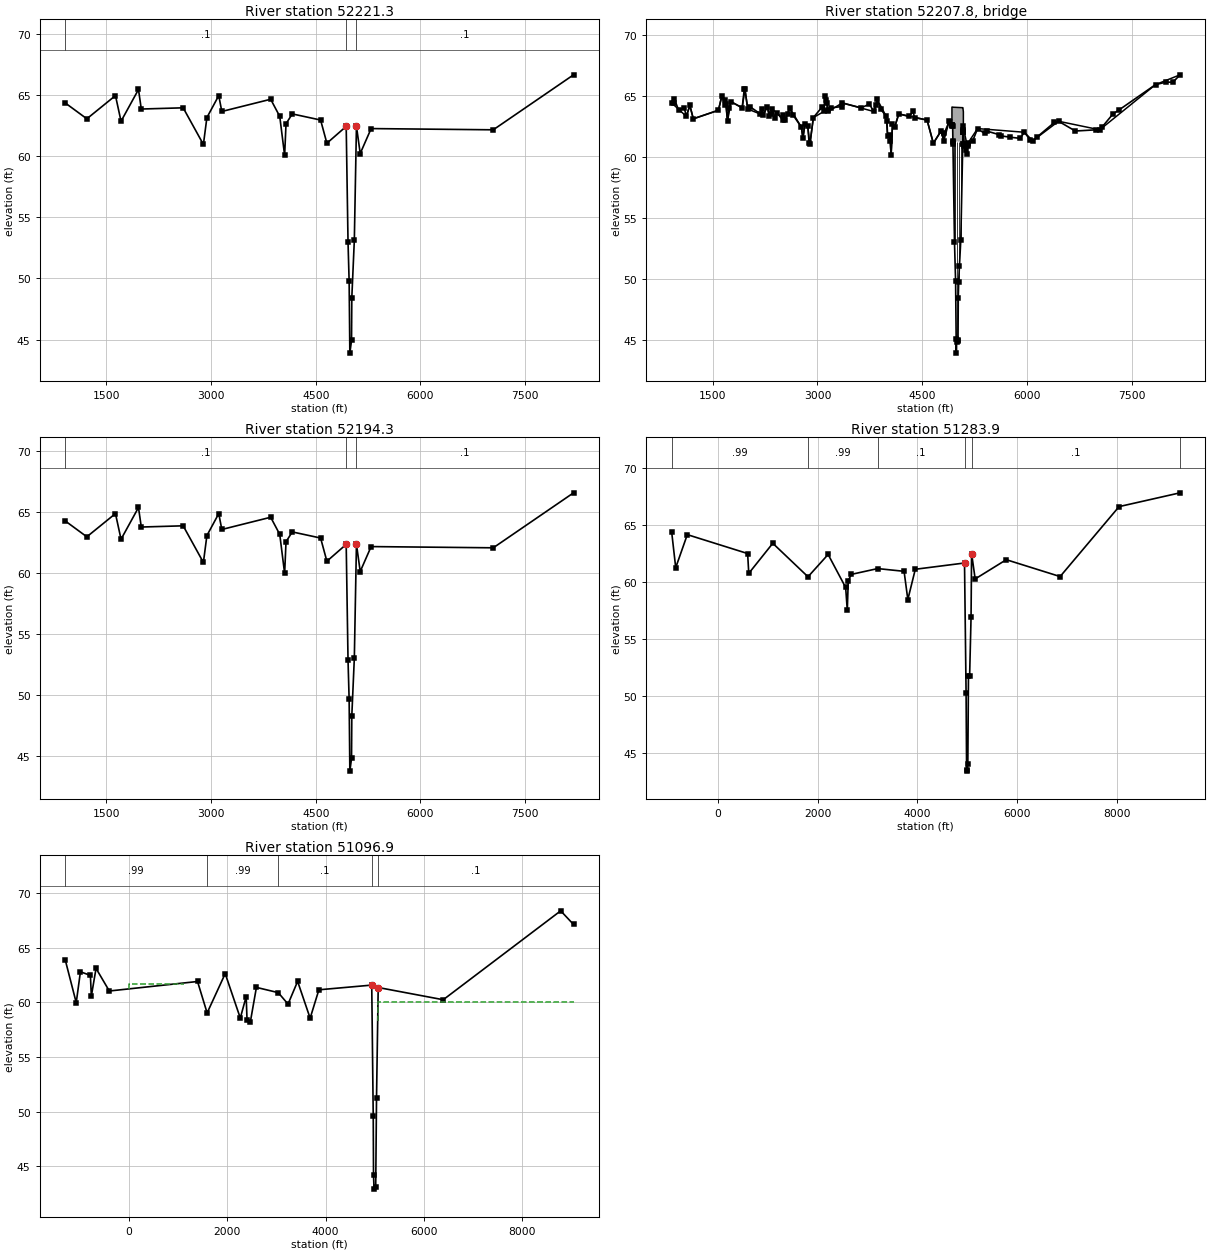
Type RM Length L Ch R = 1 ,52221.3 ,27,27,27
BEGIN DESCRIPTION:
Upstream Section of Bridge/Culvert/Weir
END DESCRIPTION:
XS GIS Cut Line= 6
      3131131.44     13888616.55      3129190.39      13887566.1
      3127342.13     13887513.18       3127285.5     13887511.18
      3126688.33     13887513.34      3124139.75     13887868.34
#Sta/Elev= 30
   911.1   64.37  1221.1   63.07  1631.1   64.97  1711.1   62.87  1961.1   65.47
  2001.1   63.87  2601.1   63.97  2891.1   60.97  2941.1   63.17  3111.1   64.97
  3154.9   63.67  3854.9   64.67  3984.9   63.27  4054.9   60.07  4074.9   62.67
  4164.9   63.47  4570.3   62.97  4660.3   61.07    4937   62.45  4963.3   52.96
  4979.1   49.76  4989.3   43.89  5013.5   44.93  5017.5   48.44  5053.6   53.15
  5083.9   62.46  5137.9   60.23  5294.2   62.27  7044.2   62.17  8194.2   66.67
#Mann= 3 , 1 , 0
   911.1      .1       0    4937    .035       0  5083.9      .1       0
#XS Ineff= 2 , 0
       0    4930    61.1    5091       0    61.1
Permanent Ineff=
       F       F
Bank Sta=4937,5083.9
XS Rating Curve= 0
Exp/Cntr=.5,.3

Type RM Length L Ch R = 3 ,52207.8 ,,,
BEGIN DESCRIPTION:
FOOTBRIDGE
Structure ID: P18-21
END DESCRIPTION:
Bridge Culvert--1,0,-1,-1, 0
Deck Dist Width WeirC Skew NumUp NumDn MinLoCord MaxHiCord MaxSubmerge Is_Ogee
10,7,2.6,0, 60, 60, , , .95, 0, 1,1,,
   911.1  1121.1  1171.1  1221.1  1581.1  1631.1  1681.1  1711.1  1761.1  1921.1
  1961.1  2001.1  2221.1  2281.1  2311.1  2351.1  2531.1  2601.1  2771.1  2791.1
  2821.1  2861.1  2891.1  2941.1  3091.1  3111.1  3154.9  3354.9  3804.9  3854.9
  3984.9  4004.9  4034.9  4054.9  4074.9  4104.9  4164.9  4570.3  4660.3  4770.3
  4810.3    4887 4926.59  4926.7    4937 4940.41  5081.6  5083.4  5090.4 5090.51
    5105  5137.9  5154.2  5294.2  5964.2  6084.2  6454.2  7044.2  7844.2  8194.2
    64.4    63.3    64.2    63.1    63.8      65    64.6    62.9    64.5      64
    65.5    63.9    63.4    64.1    63.3    63.9      63      64    62.4    61.5
    62.7    62.5      61    63.2    63.7      65    63.7    64.4    63.7    64.7
    63.3    61.7    61.8    60.1    62.7    62.4    63.5      63    61.1    62.1
    61.3   62.89   63.06   64.06   64.06   64.05   64.01   64.01   63.67   62.67
   61.98   61.11    61.1    62.3      62    61.3    62.9    62.2    65.9    66.7
    64.4    63.3    64.2    63.1    63.8      65    64.6    62.9    64.5      64
    65.5    63.9    63.4    64.1    63.3    63.9      63      64    62.4    61.5
    62.7    62.5      61    63.2    63.7      65    63.7    64.4    63.7    64.7
    63.3    61.7    61.8    60.1    62.7    62.4    63.5      63    61.1    62.1
    61.3   62.89   62.57   62.56   62.48   61.25   61.21   62.18      62      62
   60.91   60.26    61.1    62.3      62    61.3    62.9    62.2    65.9    66.7
   911.1  1121.1  1171.1  1221.1  1581.1  1631.1  1681.1  1711.1  1761.1  1921.1
  1961.1  2001.1  2221.1  2281.1  2311.1  2351.1  2531.1  2601.1  2771.1  2791.1
  2821.1  2861.1  2891.1  2941.1  3091.1  3111.1  3154.9  3354.9  3804.9  3854.9
  3984.9  4004.9  4034.9  4054.9  4074.9  4104.9  4164.9  4570.3  4660.3  4770.3
  4810.3    4887 4926.59  4926.7    4937 4940.41  5081.6  5083.4  5090.4 5090.51
    5105  5137.9  5154.2  5294.2  5964.2  6084.2  6454.2  7044.2  7844.2  8194.2
    64.4    63.3    64.2    63.1    63.8      65    64.6    62.9    64.5      64
    65.5    63.9    63.4    64.1    63.3    63.9      63      64    62.4    61.5
    62.7    62.5      61    63.2    63.7      65    63.7    64.4    63.7    64.7
    63.3    61.7    61.8    60.1    62.7    62.4    63.5      63    61.1    62.1
    61.3   62.89   63.06   64.06   64.06   64.05   64.01   64.01   63.67   62.67
   61.98   61.11    61.1    62.3      62    61.3    62.9    62.2    65.9    66.7
   64.28   63.18   64.08   62.98   63.68   64.88   64.48   62.78   64.38   63.88
   65.38   63.78   63.28   63.98   63.18   63.78   62.88   63.88   62.28   61.38
   62.58   62.38   60.88   63.08   63.58   64.88   63.58   64.28   63.58   64.58
   63.18   61.58   61.68   59.98   62.58   62.28   63.38   62.88   60.98   61.98
   61.18   62.77   62.45   62.44   62.36   61.13   61.09   62.06   61.88   61.88
   60.79   60.14   60.98   62.18   61.88   61.18   62.78   62.08   65.78   66.58
Pier Skew, UpSta & Num, DnSta & Num=  ,4963.3, 2 ,4963.3, 2 , 0 , 0 , 0 ,,
     1.2     1.2
   51.87   62.23
     1.2     1.2
   51.75   62.11
Pier Skew, UpSta & Num, DnSta & Num=  ,4992.7, 2 ,4992.7, 2 , 0 , 0 , 0 ,,
     1.2     1.2
   43.65    62.2
     1.2     1.2
   43.53   62.08
Pier Skew, UpSta & Num, DnSta & Num=  ,5023.5, 2 ,5023.5, 2 , 0 , 0 , 0 ,,
     1.2     1.2
   48.65   62.19
     1.2     1.2
   48.53   62.07
Pier Skew, UpSta & Num, DnSta & Num=  ,5053.6, 2 ,5053.6, 2 , 0 , 0 , 0 ,,
     1.2     1.2
   52.11    62.2
     1.2     1.2
   51.99   62.08
Abutment Skew #Up #Dn= , 2 , 2
  5081.6 5083.39
   61.05   62.05
  5081.6 5083.39
   60.93   61.93
BR Coef= 1 , 1 , 0 ,1.25, 0 ,,,.8,-1,2,0,
WSPro=,,,, 1 ,,,, 0 ,,,, 0 ,,,,-1 ,-1 ,-1 , 0 , 0 , 0 , 0 , 0
BR U #Sta/Elev= 136
   911.1    64.4   941.1    64.4   951.1    64.7  1011.1    63.8  1091.1      64
  1121.1    63.3  1171.1    64.2  1221.1    63.1  1581.1    63.8  1631.1      65
  1671.1    64.2  1681.1    64.6  1691.1    64.3  1711.1    62.9  1731.1      64
  1761.1    64.5  1921.1      64  1951.1    65.5  1961.1    65.5  2001.1    63.9
  2031.1    64.1  2181.1    63.5  2211.1    63.9  2221.1    63.4  2281.1    64.1
  2311.1    63.3  2341.1    63.5  2351.1    63.9  2391.1    63.2  2421.1    63.6
  2501.1      63  2511.1    63.4  2531.1      63  2581.1    63.5  2601.1      64
  2651.1    63.4  2771.1    62.4  2791.1    61.5  2821.1    62.7  2861.1    62.5
  2881.1    61.1  2891.1      61  2941.1    63.2  3071.1    64.1  3091.1    63.7
  3111.1      65  3124.9    64.6  3134.9    64.4  3144.9    63.8  3154.9    63.7
  3194.9      64  3344.9    64.1  3354.9    64.4  3624.9      64  3744.9    64.3
  3804.9    63.7  3844.9    64.2  3854.9    64.7  3904.9    63.9  3984.9    63.3
  3994.9    62.9  4004.9    61.7  4034.9    61.8  4044.9    61.3  4054.9    60.1
  4074.9    62.7  4104.9    62.4  4164.9    63.5  4310.3    63.3  4370.3    63.7
  4390.3    63.2  4570.3      63  4660.3    61.1  4770.3    62.1  4810.3    61.3
  4817.1   61.91    4887   62.89  4896.3   62.81 4926.59   62.57  4926.7   62.56
 4926.81   62.56  4933.6   62.51    4937   62.48 4940.41   61.25  4940.5   61.22
  4940.9   61.07  4963.3   52.99  4979.1   49.79  4986.6   45.11  4989.3   43.92
  4992.7   44.81    5008   44.92  5013.5   44.96  5017.5   48.47  5023.5   49.78
  5034.4   51.09  5053.6   53.18  5081.5   61.02  5081.6   61.05 5083.19   62.05
  5083.3   62.11  5083.4   62.18  5083.9   62.49 5090.29   62.01  5090.4      62
 5090.51      62    5105   60.91  5121.8   60.58  5137.9   60.26  5150.8   60.87
  5153.1   61.03  5154.2    61.1  5224.2    61.3  5294.2    62.3  5394.2    61.9
  5424.2    62.1  5604.2    61.8  5634.2    61.7  5754.2    61.6  5904.2    61.5
  5964.2      62  6044.2    61.4  6084.2    61.3  6144.2    61.6  6394.2    62.8
  6454.2    62.9  6694.2    62.1  6994.2    62.2  7044.2    62.2  7074.2    62.4
  7234.2    63.5  7314.2    63.8  7844.2    65.9  7994.2    66.1  8094.2    66.1
  8194.2    66.7
BR U #Mann= 3
   911.1      .1    4937    .035  5083.9      .1
BR U Banks=4937,5083.9
BR D #Sta/Elev= 136
   911.1   64.28   941.1   64.28   951.1   64.58  1011.1   63.68  1091.1   63.88
  1121.1   63.18  1171.1   64.08  1221.1   62.98  1581.1   63.68  1631.1   64.88
  1671.1   64.08  1681.1   64.48  1691.1   64.18  1711.1   62.78  1731.1   63.88
  1761.1   64.38  1921.1   63.88  1951.1   65.38  1961.1   65.38  2001.1   63.78
  2031.1   63.98  2181.1   63.38  2211.1   63.78  2221.1   63.28  2281.1   63.98
  2311.1   63.18  2341.1   63.38  2351.1   63.78  2391.1   63.08  2421.1   63.48
  2501.1   62.88  2511.1   63.28  2531.1   62.88  2581.1   63.38  2601.1   63.88
  2651.1   63.28  2771.1   62.28  2791.1   61.38  2821.1   62.58  2861.1   62.38
  2881.1   60.98  2891.1   60.88  2941.1   63.08  3071.1   63.98  3091.1   63.58
  3111.1   64.88  3124.9   64.48  3134.9   64.28  3144.9   63.68  3154.9   63.58
  3194.9   63.88  3344.9   63.98  3354.9   64.28  3624.9   63.88  3744.9   64.18
  3804.9   63.58  3844.9   64.08  3854.9   64.58  3904.9   63.78  3984.9   63.18
  3994.9   62.78  4004.9   61.58  4034.9   61.68  4044.9   61.18  4054.9   59.98
  4074.9   62.58  4104.9   62.28  4164.9   63.38  4310.3   63.18  4370.3   63.58
  4390.3   63.08  4570.3   62.88  4660.3   60.98  4770.3   61.98  4810.3   61.18
  4817.1   61.79    4887   62.77  4896.3   62.69 4926.59   62.45  4926.7   62.44
 4926.81   62.44  4933.6   62.39    4937   62.36 4940.41   61.13  4940.5    61.1
  4940.9   60.95  4963.3   52.87  4979.1   49.67  4986.6   44.99  4989.3    43.8
  4992.7   44.69    5008    44.8  5013.5   44.84  5017.5   48.35  5023.5   49.66
  5034.4   50.97  5053.6   53.06  5081.5    60.9  5081.6   60.93 5083.19   61.93
  5083.3   61.99  5083.4   62.06  5083.9   62.37 5090.29   61.89  5090.4   61.88
 5090.51   61.88    5105   60.79  5121.8   60.46  5137.9   60.14  5150.8   60.75
  5153.1   60.91  5154.2   60.98  5224.2   61.18  5294.2   62.18  5394.2   61.78
  5424.2   61.98  5604.2   61.68  5634.2   61.58  5754.2   61.48  5904.2   61.38
  5964.2   61.88  6044.2   61.28  6084.2   61.18  6144.2   61.48  6394.2   62.68
  6454.2   62.78  6694.2   61.98  6994.2   62.08  7044.2   62.08  7074.2   62.28
  7234.2   63.38  7314.2   63.68  7844.2   65.78  7994.2   65.98  8094.2   65.98
  8194.2   66.58
BR D #Mann= 3
   911.1      .1    4937    .035  5083.9      .1
BR D Banks=4937,5083.9
BC Design=,, 0 ,, 0 ,,,,,,

Type RM Length L Ch R = 1 ,52194.3 ,910.4,910.4,910.4
BEGIN DESCRIPTION:
Downstream Section of Bridge/Culvert/Weir
END DESCRIPTION:
XS GIS Cut Line= 6
      3131135.49     13888589.86      3129194.45      13887539.4
      3127346.19     13887486.48      3127289.56     13887484.48
      3126692.39     13887486.64      3124143.81     13887841.65
#Sta/Elev= 30
   911.1   64.28  1221.1   62.98  1631.1   64.88  1711.1   62.78  1961.1   65.38
  2001.1   63.78  2601.1   63.88  2891.1   60.88  2941.1   63.08  3111.1   64.88
  3154.9   63.58  3854.9   64.58  3984.9   63.18  4054.9   59.98  4074.9   62.58
  4164.9   63.38  4570.3   62.88  4660.3   60.98    4937   62.36  4963.3   52.87
  4979.1   49.67  4989.3    43.8  5013.5   44.84  5017.5   48.35  5053.6   53.06
  5083.9   62.37  5137.9   60.14  5294.2   62.18  7044.2   62.08  8194.2   66.58
#Mann= 3 , 1 , 0
   911.1      .1       0    4937    .035       0  5083.9      .1       0
#XS Ineff= 2 , 0
       0    4930    61.1    5091       0    61.1
Permanent Ineff=
       F       F
Bank Sta=4937,5083.9
XS Rating Curve= 0
Exp/Cntr=.5,.3

Type RM Length L Ch R = 1 ,51283.9 ,250.4,187,160.1
BEGIN DESCRIPTION:
Cross Section 51283.9
END DESCRIPTION:
XS GIS Cut Line= 6
      3132025.57     13888924.76      3130835.77     13887312.14
      3129449.32     13886515.67      3127467.22     13886468.21
      3126429.34     13886976.98      3123152.87     13888065.74
#Sta/Elev= 30
  -927.6    64.4  -846.6   61.27  -614.1   64.17   595.8   62.51   618.7   60.77
  1100.5   63.41  1806.8   60.47  2210.2   62.43  2562.1   59.53  2594.8   57.52
    2614   60.12  2675.4   60.68  3204.2   61.19  3733.9   60.95  3808.9   58.47
  3958.9   61.13  4945.9   61.68  4977.5    50.3  4987.8   43.48  4998.9   43.41
  5012.5   44.07  5025.1   51.72  5048.5   51.78    5077    56.9  5087.8   62.51
  5159.7   60.28  5783.6   61.97  6863.5   60.49    8046   66.63    9268   67.84
#Mann= 6 , 1 , 0
  -927.6     .99       0  1806.8     .99       0  3204.2      .1       0
  4945.9    .035       0  5087.8      .1       0    9268      .2       0
#XS Ineff= 2 , 0
       0  1221.7      62               0
Permanent Ineff=
       F       F
Bank Sta=4945.9,5087.8
XS Rating Curve= 0
Exp/Cntr=.5,.3

Type RM Length L Ch R = 1 ,51096.9 ,26,26,26
BEGIN DESCRIPTION:
Upstream Section of Bridge/Culvert/Weir
END DESCRIPTION:
XS GIS Cut Line= 6
      3132318.37     13888780.89      3131257.75     13887331.37
      3129477.87       13886340.       3127385.7     13886321.72
      3126420.98     13886696.02      3123224.27      13887830.3
#Sta/Elev= 30
 -1301.5   63.91   -1077   59.98  -991.5   62.81  -788.4   62.48  -769.3   60.58
  -673.5   63.12  -403.2   61.05  1393.5   61.92  1588.8   59.04  1957.1   62.64
  2264.5   58.57    2384   60.54  2402.2   58.35  2469.4   58.23  2592.6   61.38
  3037.2    60.9  3236.7   59.85  3431.8   61.93  3686.9   58.56  3864.9   61.16
 4941.43   61.59 4971.83   49.58 4977.73   44.17 4988.53   42.91 5022.23   43.12
 5038.63   51.21 5073.03   61.37  6397.6   60.25  8789.6   68.39  9051.2   67.14
#Mann= 5 , 1 , 0
 -1301.5     .99       0  1588.8     .99       0  3037.2      .1       0
 4941.43    .035       0 5073.03      .1       0
#XS Ineff= 2 , 0
       0    1118    61.7  5062.5       0      60
Permanent Ineff=
       F       F
Bank Sta=4941.43,5073.03
XS Rating Curve= 0
Exp/Cntr=.5,.3