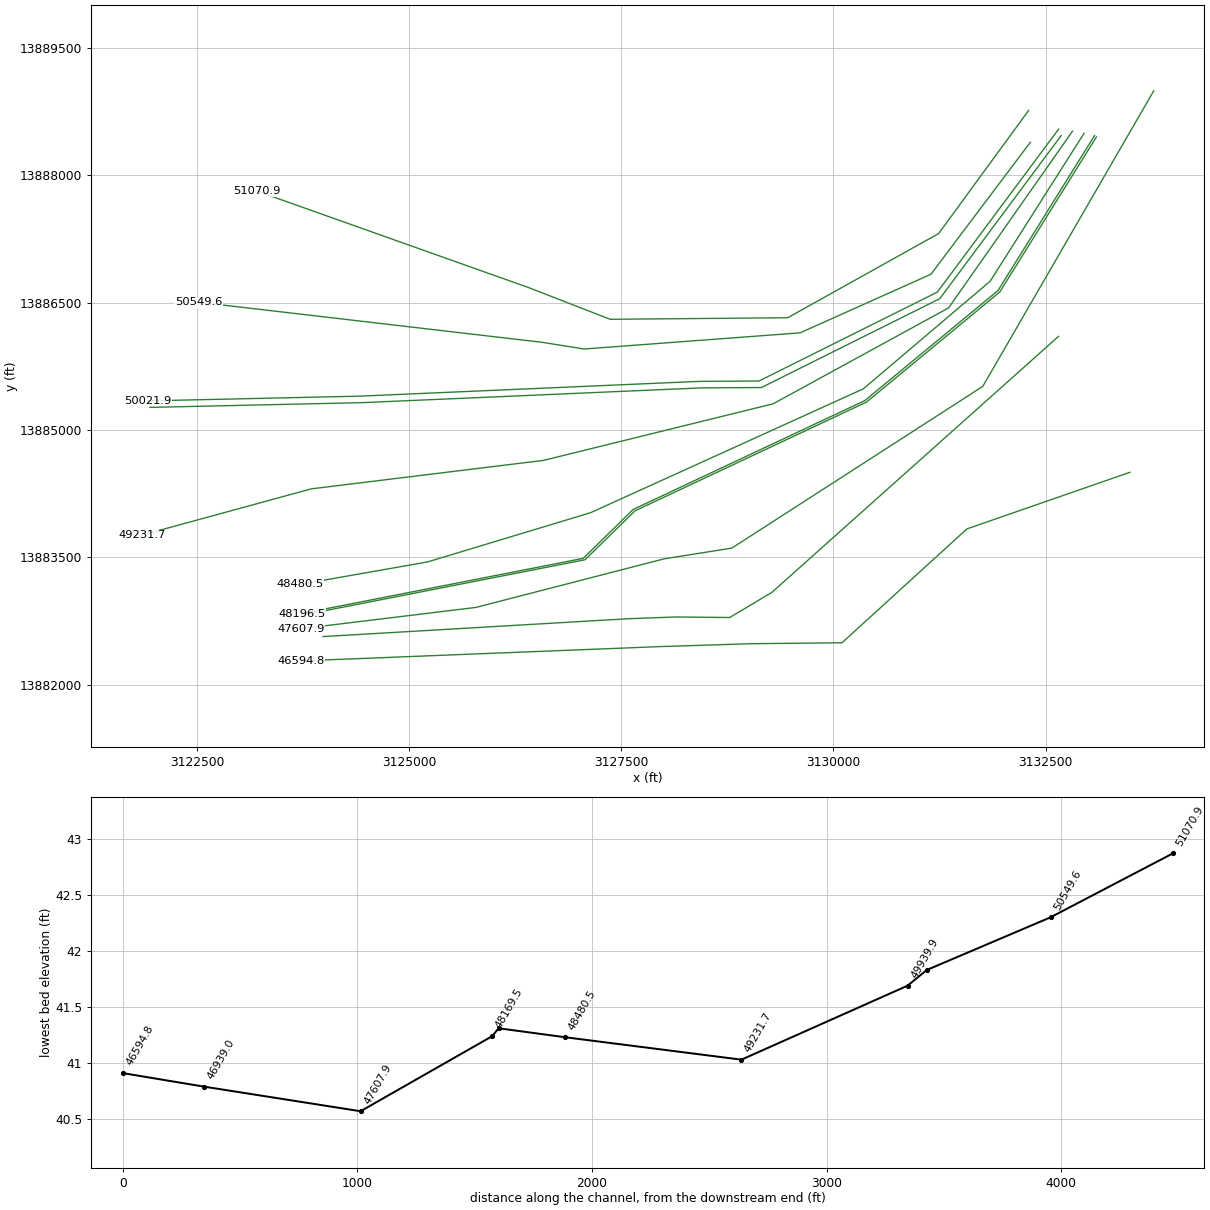
HEC-RAS study P118-00-00.PRJ: P118-00-00

--- P118-00-00.g01 (geometry) --- (continued)

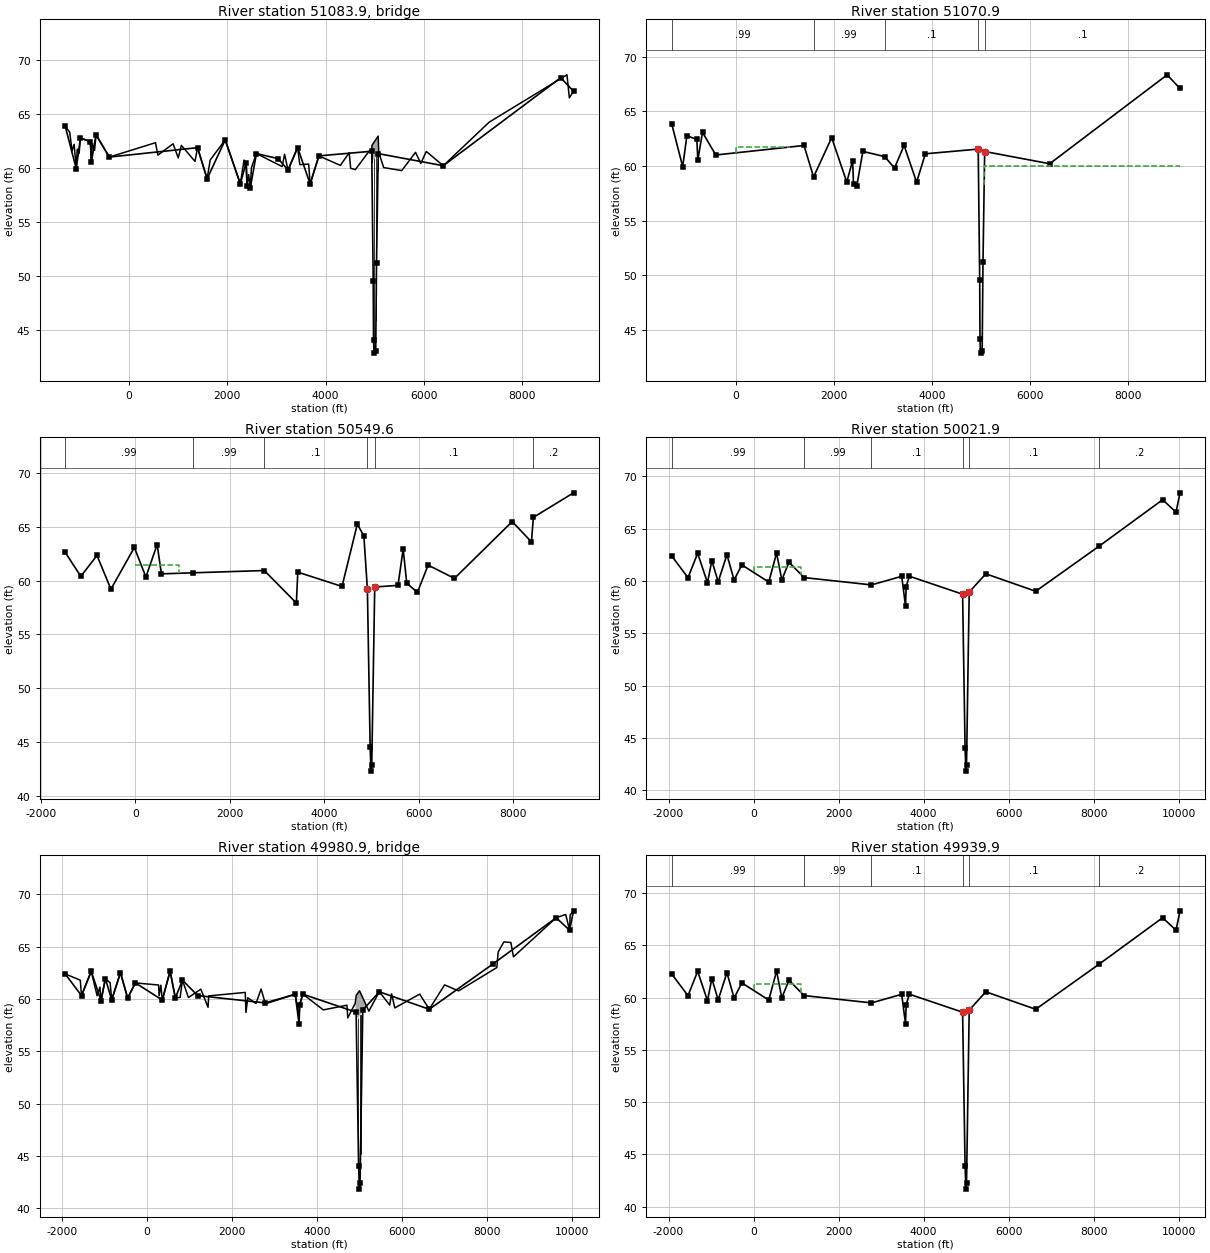
Type RM Length L Ch R = 3 ,51083.9 ,,,
BEGIN DESCRIPTION:
SERIES OF PIPELINES
END DESCRIPTION:
Bridge Culvert--1,0,-1,-1, 0
Deck Dist Width WeirC Skew NumUp NumDn MinLoCord MaxHiCord MaxSubmerge Is_Ogee
10,6,2.6,0, 60, 60, , , .95, 0, 1,1,,
 -1301.5 -1209.9 -1162.4 -1119.7   -1077 -1056.6 -1018.3  -991.5  -788.4  -769.3
  -750.1  -703.3  -673.5  -403.2   537.4   585.6     896  1000.7  1064.1  1342.3
  1393.5  1588.4  1651.2  1957.1  2264.5  2341.5    2384  2402.2  2435.2  2469.4
  2490.7  2592.6  3116.7  3166.3  3236.7  3431.8  3476.8  3656.9  3686.9  3864.9
  4302.2  4482.3  4512.3  4607.2 4893.63 4941.43 4944.03 4945.03 5072.53 5083.83
 5184.33    5553  5833.5  5940.5  6052.6  6397.6    7333  8917.7  8965.7  9051.2
   63.88   63.32   61.58    62.2   59.95   61.75   61.36   62.78   62.45   60.55
   62.26   61.64   63.09   61.02   62.35    61.2   62.25   60.94    62.1   60.62
   61.89      59   60.75   62.61   58.54   60.74   60.51   58.32   59.39    58.2
   60.02   61.35   60.14   61.27   59.82    61.9   60.32   60.37   58.53   61.13
   60.25   61.42   59.98   59.86    61.6   61.56   60.49    62.1   62.96   61.47
   60.05   59.77   61.46   60.43   61.54   60.22   64.25   68.63    66.5   67.11
   63.88   63.32   61.58    62.2   59.95   61.75   61.36   62.78   62.45   60.55
   62.26   61.64   63.09   61.02   62.35    61.2   62.25   60.94    62.1   60.62
   61.89      59   60.75   62.61   58.54   60.74   60.51   58.32   59.39    58.2
   60.02   61.35   60.14   61.27   59.82    61.9   60.32   60.37   58.53   61.13
   60.25   61.42   59.98   59.86    61.6   61.56   60.49    60.6   61.46   61.47
   60.05   59.77   61.46   60.43   61.54   60.22   64.25   68.63    66.5   67.11
 -1301.5 -1209.9 -1162.4 -1119.7   -1077 -1056.6 -1018.3  -991.5  -788.4  -769.3
  -750.1  -703.3  -673.5  -403.2   537.4   585.6     896  1000.7  1064.1  1342.3
  1393.5  1588.4  1651.2  1957.1  2264.5  2341.5    2384  2402.2  2435.2  2469.4
  2490.7  2592.6  3116.7  3166.3  3236.7  3431.8  3476.8  3656.9  3686.9  3864.9
  4302.2  4482.3  4512.3  4607.2 4893.63 4941.43 4944.03 4945.03 5072.53 5083.83
 5184.33    5553  5833.5  5940.5  6052.6  6397.6    7333  8917.7  8965.7  9051.2
   63.88   63.32   61.58    62.2   59.95   61.75   61.36   62.78   62.45   60.55
   62.26   61.64   63.09   61.02   62.35    61.2   62.25   60.94    62.1   60.62
   61.89      59   60.75   62.61   58.54   60.74   60.51   58.32   59.39    58.2
   60.02   61.35   60.14   61.27   59.82    61.9   60.32   60.37   58.53   61.13
   60.25   61.42   59.98   59.86    61.6   61.56   60.49    62.1   62.96   61.47
   60.05   59.77   61.46   60.43   61.54   60.22   64.25   68.63    66.5   67.11
   63.88   63.32   61.58    62.2   59.95   61.75   61.36   62.78   62.45   60.55
   62.26   61.64   63.09   61.02   62.35    61.2   62.25   60.94    62.1   60.62
   61.89      59   60.75   62.61   58.54   60.74   60.51   58.32   59.39    58.2
   60.02   61.35   60.14   61.27   59.82    61.9   60.32   60.37   58.53   61.13
   60.25   61.42   59.98   59.86    61.6   61.56   60.49    60.6   61.46   61.47
   60.05   59.77   61.46   60.43   61.54   60.22   64.25   68.63    66.5   67.11
Pier Skew, UpSta & Num, DnSta & Num=  ,4988.5, 2 ,4988.5, 2 , 0 , 0 , 0 ,,
     1.5     1.5
   41.92   61.82
     1.5     1.5
   41.92   61.82
Pier Skew, UpSta & Num, DnSta & Num=  ,5027.9, 2 ,5027.9, 2 , 0 , 0 , 0 ,,
     1.5     1.5
   45.75   62.13
     1.5     1.5
   45.75   62.13
Pier Skew, UpSta & Num, DnSta & Num=  ,5067.7, 2 ,5067.7, 2 , 0 , 0 , 0 ,,
     1.5     1.5
   58.38   62.43
     1.5     1.5
   58.38   62.43
BR Coef= 1 , 1 , 0 ,1.25, 0 ,,,.8,0,2,0,
WSPro=,,,, 1 ,,,, 0 ,,,, 0 ,,,,-1 ,-1 ,-1 , 0 , 0 , 0 , 0 , 0
BR U #Sta/Elev= 30
 -1301.5   63.88   -1077   59.95  -991.5   62.78  -788.4   62.45  -769.3   60.55
  -673.5   63.09  -403.2   61.02  1393.5   61.89  1588.8   59.01  1957.1   62.61
  2264.5   58.54    2384   60.51  2402.2   58.32  2469.4    58.2  2592.6   61.35
  3037.2   60.87  3236.7   59.82  3431.8    61.9  3686.9   58.53  3864.9   61.13
 4941.43   61.56 4971.83   49.55 4977.73   44.14 4988.53   42.88 5022.23   43.09
 5038.63   51.18 5073.03   61.34  6397.6   60.22  8789.6   68.36  9051.2   67.11
BR U #Mann= 5
 -1301.5     .99  1588.8     .99  3037.2      .1 4941.43     .04 5073.03      .1
BR U Banks=4941.43,5073.03
BR D #Sta/Elev= 30
 -1301.5   63.88   -1077   59.95  -991.5   62.78  -788.4   62.45  -769.3   60.55
  -673.5   63.09  -403.2   61.02  1393.5   61.89  1588.8   59.01  1957.1   62.61
  2264.5   58.54    2384   60.51  2402.2   58.32  2469.4    58.2  2592.6   61.35
  3037.2   60.87  3236.7   59.82  3431.8    61.9  3686.9   58.53  3864.9   61.13
 4941.43   61.56 4971.83   49.55 4977.73   44.14 4988.53   42.88 5022.23   43.09
 5038.63   51.18 5073.03   61.34  6397.6   60.22  8789.6   68.36  9051.2   67.11
BR D #Mann= 5
 -1301.5     .99  1588.8     .99  3037.2      .1 4941.43     .04 5073.03      .1
BR D Banks=4941.43,5073.03
BC Design=,, 0 ,, 0 ,,,,,,

Type RM Length L Ch R = 1 ,51070.9 ,521.3,521.3,521.3
BEGIN DESCRIPTION:
Downstream Section of Bridge/Culvert/Weir
END DESCRIPTION:
XS GIS Cut Line= 6
       3132300.4     13888762.11      3131239.77     13887312.59
      3129459.89     13886321.22      3127367.72     13886302.94
        3126403.     13886677.24       3123206.3     13887811.52
#Sta/Elev= 30
 -1301.5   63.87   -1077   59.94  -991.5   62.77  -788.4   62.44  -769.3   60.54
  -673.5   63.08  -403.2   61.01  1393.5   61.88  1588.8      59  1957.1    62.6
  2264.5   58.53    2384    60.5  2402.2   58.31  2469.4   58.19  2592.6   61.34
  3037.2   60.86  3236.7   59.81  3431.8   61.89  3686.9   58.52  3864.9   61.12
 4941.43   61.55 4971.83   49.54 4977.73   44.13 4988.53   42.87 5022.23   43.08
 5038.63   51.17 5073.03   61.33  6397.6   60.21  8789.6   68.35  9051.2    67.1
#Mann= 5 , 1 , 0
 -1301.5     .99       0  1588.8     .99       0  3037.2      .1       0
 4941.43    .035       0 5073.03      .1       0
#XS Ineff= 2 , 0
       0    1118    61.7  5062.5       0      60
Permanent Ineff=
       F       F
Bank Sta=4941.43,5073.03
XS Rating Curve= 0
Exp/Cntr=.5,.3

Type RM Length L Ch R = 1 ,50549.6 ,505,527.7,638.9
BEGIN DESCRIPTION:
Cross Section 50549.6-Interpolated
END DESCRIPTION:
XS GIS Cut Line= 6
      3132320.65     13888387.49        3131149.     13886833.53
      3129606.54     13886143.38      3127059.59     13885952.96
       3126567.4     13886031.71      3122511.76     13886504.21
#Sta/Elev= 30
 -1487.1   62.63 -1156.4    60.4  -813.7   62.34  -518.5   59.21   -21.8   63.08
   222.4   60.34     461   63.35   551.8   60.63  1228.4   60.73  2731.5   60.94
  3411.4   57.92  3441.5   60.79  4378.8   59.46  4702.9   65.25  4841.8   64.15
  4916.2   59.21  4974.6   44.54  4994.3    42.3  5008.5   42.84  5071.8   59.41
    5565   59.56  5674.5   62.94    5750   59.76  5976.5   58.91    6203   61.44
  6761.5   60.21    7985   65.49  8392.7    63.6  8433.6   65.88  9284.5   68.16
#Mann= 6 , 1 , 0
 -1487.1     .99       0  1228.4     .99       0  2731.5      .1       0
  4916.2    .035       0  5071.8      .1       0  8433.6      .2       0
#XS Ineff= 2 , 0
       0     925    61.5               0
Permanent Ineff=
       F       F
Bank Sta=4916.2,5071.8
XS Rating Curve= 0
Exp/Cntr=.5,.3

Type RM Length L Ch R = 1 ,50021.9 ,82,82,82
BEGIN DESCRIPTION:
Upstream Section of Bridge/Culvert/Weir
END DESCRIPTION:
XS GIS Cut Line= 6
       3132654.2     13888542.19      3131224.23     13886622.78
      3129121.23     13885576.02      3128416.96     13885571.87
      3124411.07     13885397.72      3121911.59     13885342.02
#Sta/Elev= 30
 -1926.7    62.4 -1542.9   60.32 -1315.3   62.65 -1084.6   59.84  -982.1   61.95
  -832.6   59.92  -626.9   62.52  -458.7    60.1  -275.4   61.54   357.1    59.9
   540.6   62.67   663.9   60.11     832    61.8  1188.7   60.33  2773.2   59.63
  3483.6   60.45  3573.7   57.63  3588.8   59.46  3663.9   60.46  4916.2   58.74
  4974.6   44.07  4994.3   41.83  5008.5   42.37  5071.8   58.94    5462   60.69
  6636.3   59.02  8126.8   63.33  9621.5   67.77  9936.5   66.58   10030   68.43
#Mann= 6 , 1 , 0
 -1926.7     .99       0  1188.7     .99       0  2773.2      .1       0
  4916.2    .035       0  5071.8      .1       0  8126.8      .2       0
#XS Ineff= 2 , 0
       0    1118    61.3    5079       0    58.8
Permanent Ineff=
       F       F
Bank Sta=4916.2,5071.8
XS Rating Curve= 0
Exp/Cntr=.5,.3

Type RM Length L Ch R = 3 ,49980.9 ,,,
BEGIN DESCRIPTION:
HOPPER STREET
Structure ID: P18-19
END DESCRIPTION:
Bridge Culvert--1,0,-1,-1, 0
Deck Dist Width WeirC Skew NumUp NumDn MinLoCord MaxHiCord MaxSubmerge Is_Ogee
10,62,2.6,0, 60, 60, , , .95, 0, 1,1,,
 -1926.7 -1572.6 -1542.9 -1315.3 -1175.9 -1109.7 -1084.6  -982.1    -870  -832.6
  -626.9  -458.7  -275.4   270.3   282.1     323   357.1   540.6   663.9     776
     832   971.2  1263.2  1433.3  1448.4  2308.1  2324.8  2367.4  2561.1  2681.2
  2782.1  3483.6  3573.7  3588.8  3663.9  4144.5  4700.5  4718.7  4893.5  4918.3
  4996.2  5216.1    5462  5706.2  5750.3  5826.1  6411.3  6636.3  6996.3  7326.3
  8226.4  8256.4  8391.4  8556.4  8616.4  9621.5  9845.6  9936.5  9951.5   10030
   62.39   61.79   60.31   62.64    60.3   61.13   59.83   61.94   61.54   59.91
   62.51   60.09   61.53   61.33    60.3   61.31   59.89   62.66    60.1   60.14
   61.79   60.13   60.93    59.2   60.29   60.62   58.71   60.11   59.57   60.95
   59.53   60.45    58.3   59.46   60.46   58.95    59.4   58.19   59.57   60.33
   60.78   58.83   60.69   59.41   60.49   59.14   60.46   59.01   61.34   60.77
      63   64.47   65.45   65.39   64.02   67.76   68.07   66.57   68.03   68.42
   62.39   61.79   60.31   62.64    60.3   61.13   59.83   61.94   61.54   59.91
   62.51   60.09   61.53   61.33    60.3   61.31   59.89   62.66    60.1   60.14
   61.79   60.13   60.93    59.2   60.29   60.62   58.71   60.11   59.57   60.95
   59.53   60.44   57.62   59.45   60.45   58.94   59.39   58.18   59.56   57.72
   58.43    58.7   60.68    59.4   60.48   59.14   60.46   59.01   61.34   60.77
      63   64.47   65.45   65.39   64.02   67.76   68.07   66.57   68.03   68.42
 -1926.7 -1572.6 -1542.9 -1315.3 -1175.9 -1109.7 -1084.6  -982.1    -870  -832.6
  -626.9  -458.7  -275.4   270.3   282.1     323   357.1   540.6   663.9     776
     832   971.2  1263.2  1433.3  1448.4  2308.1  2324.8  2367.4  2561.1  2681.2
  2782.1  3483.6  3573.7  3588.8  3663.9  4144.5  4700.5  4718.7  4893.5  4918.3
  4996.2  5216.1    5462  5706.2  5750.3  5826.1  6411.3  6636.3  6996.3  7326.3
  8226.4  8256.4  8391.4  8556.4  8616.4  9621.5  9845.6  9936.5  9951.5   10030
   62.39   61.79   60.31   62.64    60.3   61.13   59.83   61.94   61.54   59.91
   62.51   60.09   61.53   61.33    60.3   61.31   59.89   62.66    60.1   60.14
   61.79   60.13   60.93    59.2   60.29   60.62   58.71   60.11   59.57   60.95
   59.53   60.45    58.3   59.46   60.46   58.95    59.4   58.19   59.57   60.33
   60.78   58.83   60.69   59.41   60.49   59.14   60.46   59.01   61.34   60.77
      63   64.47   65.45   65.39   64.02   67.76   68.07   66.57   68.03   68.42
   62.27   61.67   60.19   62.52   60.18   61.01   59.71   61.82   61.42   59.79
   62.39   59.97   61.41   61.21   60.18   61.19   59.77   62.54   59.98   60.02
   61.67   60.01   60.81   59.08   60.17    60.5   58.59   59.99   59.45   60.83
   59.41   60.32    57.5   59.33   60.33   58.82   59.27   58.06   59.44    57.6
   58.31   58.58   60.56   59.28   60.36   59.02   60.34   58.89   61.22   60.65
   62.88   64.35   65.33   65.27    63.9   67.64   67.95   66.45   67.91    68.3
Pier Skew, UpSta & Num, DnSta & Num=  ,4967.6, 2 ,4967.6, 2 , 0 , 0 , 0 ,,
     1.6     1.6
   44.57   59.27
     1.6     1.6
   44.45   59.15
Pier Skew, UpSta & Num, DnSta & Num=  ,5019.1, 2 ,5019.1, 2 , 0 , 0 , 0 ,,
     1.6     1.6
   44.35   59.29
     1.6     1.6
   44.23   59.17
BR Coef= 1 , 1 , 0 ,1.25, 0 ,,,.8,0,2,0,
WSPro=,,,, 1 ,,,, 0 ,,,, 0 ,,,,-1 ,-1 ,-1 , 0 , 0 , 0 , 0 , 0
BR U #Sta/Elev= 30
 -1926.7   62.39 -1542.9   60.31 -1315.3   62.64 -1084.6   59.83  -982.1   61.94
  -832.6   59.91  -626.9   62.51  -458.7   60.09  -275.4   61.53   357.1   59.89
   540.6   62.66   663.9    60.1     832   61.79  1188.7   60.32  2773.2   59.62
  3483.6   60.44  3573.7   57.62  3588.8   59.45  3663.9   60.45  4916.2   58.73
  4974.6   44.06  4994.3   41.82  5008.5   42.36  5071.8   58.93    5462   60.68
  6636.3   59.01  8126.8   63.32  9621.5   67.76  9936.5   66.57   10030   68.42
BR U #Mann= 6
 -1926.7     .99  1188.7     .99  2773.2      .1  4916.2    .035  5071.8      .1
  8126.8      .2
BR U Banks=4916.2,5071.8
BR D #Sta/Elev= 30
 -1926.7   62.27 -1542.9   60.19 -1315.3   62.52 -1084.6   59.71  -982.1   61.82
  -832.6   59.79  -626.9   62.39  -458.7   59.97  -275.4   61.41   357.1   59.77
   540.6   62.54   663.9   59.98     832   61.67  1188.7    60.2  2773.2    59.5
  3483.6   60.32  3573.7    57.5  3588.8   59.33  3663.9   60.33  4916.2   58.61
  4974.6   43.94  4994.3    41.7  5008.5   42.24  5071.8   58.81    5462   60.56
  6636.3   58.89  8126.8    63.2  9621.5   67.64  9936.5   66.45   10030    68.3
BR D #Mann= 6
 -1926.7     .99  1188.7     .99  2773.2      .1  4916.2    .035  5071.8      .1
  8126.8      .2
BR D Banks=4916.2,5071.8
BC Design=,, 0 ,, 0 ,,,,,,

Type RM Length L Ch R = 1 ,49939.9 ,708.2,708.2,708.2
BEGIN DESCRIPTION:
Downstream Section of Bridge/Culvert/Weir
END DESCRIPTION:
XS GIS Cut Line= 6
      3132683.59     13888465.64      3131253.63     13886546.22
      3129150.63     13885499.46      3128446.36     13885495.31
      3124440.47     13885321.16      3121940.98     13885265.47
#Sta/Elev= 30
 -1926.7   62.26 -1542.9   60.18 -1315.3   62.51 -1084.6    59.7  -982.1   61.81
  -832.6   59.78  -626.9   62.38  -458.7   59.96  -275.4    61.4   357.1   59.76
   540.6   62.53   663.9   59.97     832   61.66  1188.7   60.19  2773.2   59.49
  3483.6   60.31  3573.7   57.49  3588.8   59.32  3663.9   60.32  4916.2    58.6
  4974.6   43.93  4994.3   41.69  5008.5   42.23  5071.8    58.8    5462   60.55
  6636.3   58.88  8126.8   63.19  9621.5   67.63  9936.5   66.44   10030   68.29
#Mann= 6 , 1 , 0
 -1926.7     .99       0  1188.7     .99       0  2773.2      .1       0
  4916.2    .035       0  5071.8      .1       0  8126.8      .2       0
#XS Ineff= 2 , 0
       0    1118    61.3    5079       0    58.6
Permanent Ineff=
       F       F
Bank Sta=4916.2,5071.8
XS Rating Curve= 0
Exp/Cntr=.5,.3

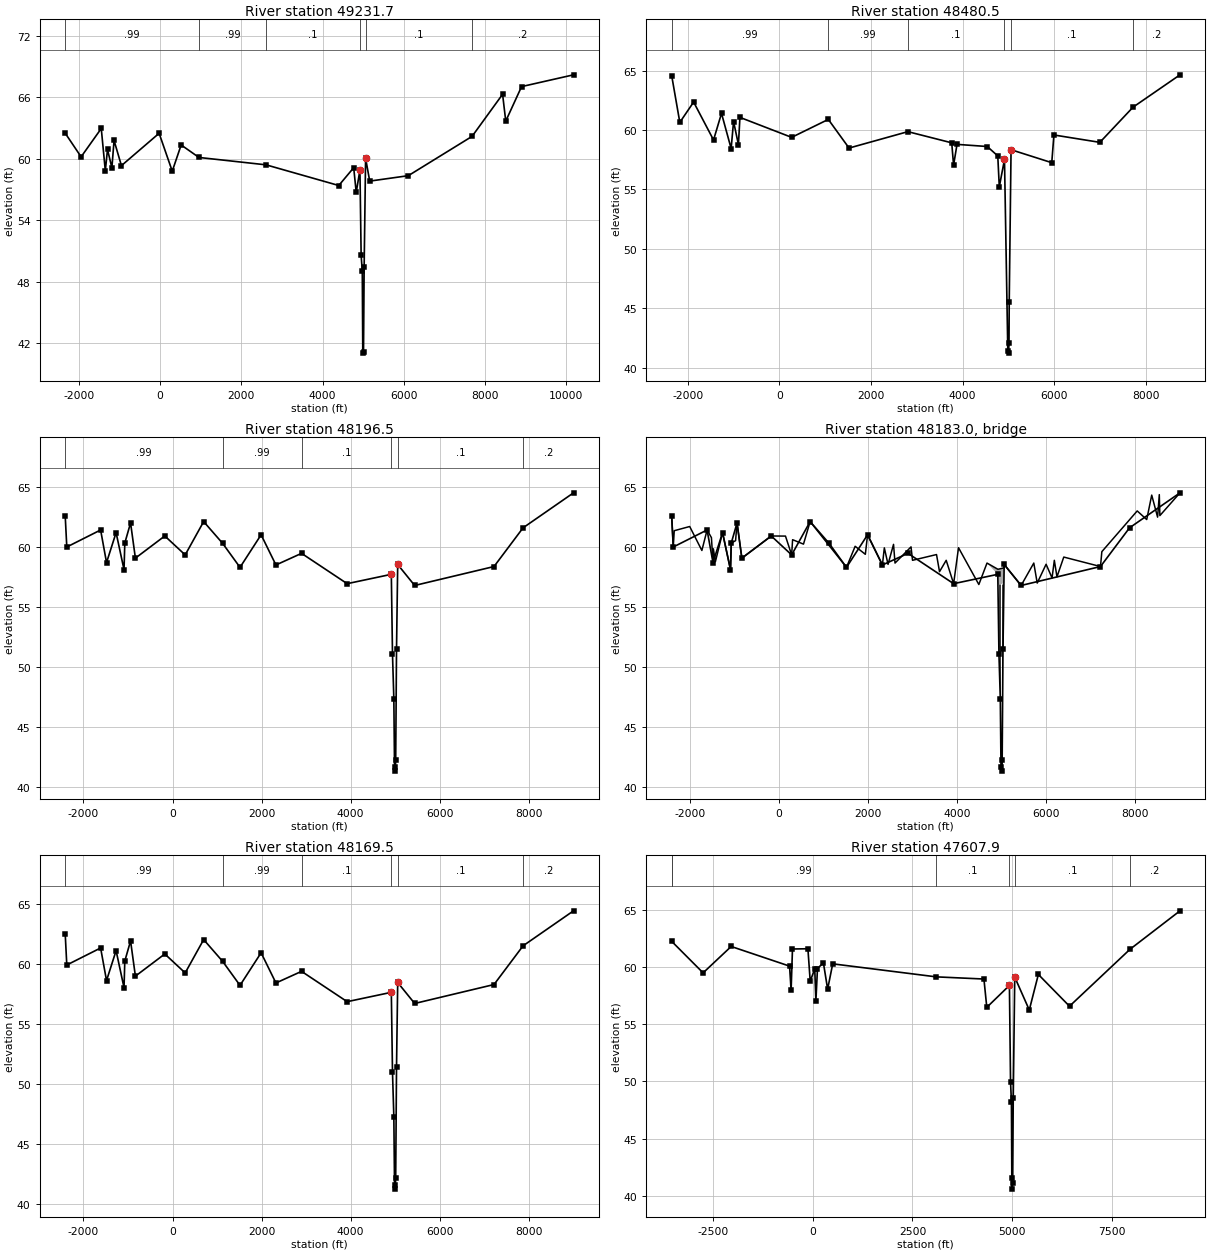
Type RM Length L Ch R = 1 ,49231.7 ,710.5,751.2,889.5
BEGIN DESCRIPTION:
Cross Section 49231.7
END DESCRIPTION:
XS GIS Cut Line= 6
      3132817.49     13888518.08      3131356.92       13886437.
      3129289.19     13885307.97      3126581.03     13884641.28
      3123844.34     13884306.18      3121847.68     13883761.63
#Sta/Elev= 30
 -2334.4   62.51 -1942.8    60.2 -1446.7   62.97 -1346.9   58.84 -1293.1   60.92
 -1185.4   59.13 -1131.6    61.8  -950.5   59.34   -22.4    62.5   300.9    58.8
     520   61.36   958.4   60.14  2609.2   59.42  4400.3    57.4  4767.8   59.14
  4829.8   56.73  4921.5   58.92    4951   50.58  4979.1   49.05  4991.4   41.03
  5009.4   41.12  5025.1   49.48  5060.6   60.06  5162.2   57.83  6112.2   58.36
    7682    62.2  8433.4   66.31  8511.1   63.69  8900.6   67.06 10179.8   68.21
#Mann= 6 , 1 , 0
 -2334.4     .99       0   958.4     .99       0  2609.2      .1       0
  4921.5    .035       0  5060.6      .1       0    7682      .2       0
Bank Sta=4921.5,5060.6
XS Rating Curve= 0
Exp/Cntr=.3,.1

Type RM Length L Ch R = 1 ,48480.5 ,159.5,284,493.6
BEGIN DESCRIPTION:
Cross Section 48480.5-Interpolated
END DESCRIPTION:
XS GIS Cut Line= 6
      3132953.67     13888492.45      3131847.96     13886752.39
      3130351.93     13885483.93      3127136.81     13884025.52
      3125214.36     13883445.47      3123706.23     13883180.31
#Sta/Elev= 30
 -2347.4   64.58 -2169.7   60.64 -1868.4   62.35 -1433.7   59.16 -1259.9    61.4
   -1050   58.44  -996.7   60.71  -890.8   58.77  -857.8   61.06   270.8   59.38
  1070.6   60.89  1523.3   58.48  2807.1   59.86  3763.9   58.92  3804.5   57.04
  3879.4   58.79    4539   58.61  4768.8   57.82  4802.1   55.22  4915.5   57.52
  4987.8   41.43  5004.1   41.23  5013.8   42.06  5018.6   45.49  5058.7   58.34
  5947.1   57.25  5994.1   59.58  6996.8   58.96  7721.1   61.92  8745.5   64.64
#Mann= 6 , 1 , 0
 -2347.4     .99       0  1070.6     .99       0  2807.1      .1       0
  4915.5    .035       0  5058.7      .1       0  7721.1      .2       0
Bank Sta=4915.5,5058.7
XS Rating Curve= 0
Exp/Cntr=.5,.3

Type RM Length L Ch R = 1 ,48196.5 ,27,27,27
BEGIN DESCRIPTION:
Upstream Section of Bridge/Culvert/Weir
END DESCRIPTION:
XS GIS Cut Line= 6
      3133078.32     13888466.89       3131938.9     13886640.68
      3130368.96     13885345.09      3127638.87     13884063.79
      3127049.29     13883487.52      3123730.18     13882838.09
#Sta/Elev= 30
 -2410.2   62.61 -2374.5   60.01 -1614.7   61.43 -1481.9   58.71 -1267.3   61.21
 -1089.1   58.12 -1071.3   60.34    -942   62.02  -833.5   59.08    -173   60.93
   284.8   59.35   699.9   62.13  1124.8   60.32  1516.6   58.31  1990.3   61.03
  2323.6   58.51  2898.9   59.48  3923.4   56.95  4915.5   57.73  4941.8   51.07
  4972.1   47.36  4987.8   41.64  5003.2   41.31  5013.8   42.27  5032.5   51.53
  5058.7   58.55  5439.8    56.8  7222.5   58.38    7875   61.61  9008.7   64.53
#Mann= 6 , 1 , 0
 -2410.2     .99       0  1124.8     .99       0  2898.9      .1       0
  4915.5    .035       0  5058.7      .1       0    7875      .2       0
#XS Ineff= 2 , 0
       0    4909    57.3    5063       0    57.5
Permanent Ineff=
       F       F
Bank Sta=4915.5,5058.7
XS Rating Curve= 0
Exp/Cntr=.5,.3

Type RM Length L Ch R = 3 ,48183.0 ,,,
BEGIN DESCRIPTION:
FOOTBRIDGE
Structure ID: P18-18
END DESCRIPTION:
Bridge Culvert--1,0,-1,-1, 0
Deck Dist Width WeirC Skew NumUp NumDn MinLoCord MaxHiCord MaxSubmerge Is_Ogee
10,7,2.6,0, 60, 60, , , .95, 0, 1,1,,
 -2410.2 -2374.5 -2352.5 -2005.3 -1731.8 -1614.7 -1517.1 -1481.9 -1473.7 -1428.3
 -1267.3 -1089.1 -1071.3  -974.6    -942  -833.5    -173   146.4   284.8   306.3
   550.9   699.9  1516.6  1711.2  1940.3  1990.3  2323.6  2366.8    2450  2573.6
  2606.9  2966.6  3000.2  3539.3  3606.6  3756.7  3923.4  4033.4  4489.9  4673.3
 4918.91  5052.9  5058.7  5439.8  5724.4  5801.3  6000.6  6134.5  6185.7    6245
  6397.7  7222.5    7253  8047.2  8261.1  8373.4  8505.3  8543.7  8556.5  9008.7
   62.61   60.01   61.37   61.72   59.72   61.43   60.79   58.71   59.86   58.78
   61.21   58.12   60.34   60.54   62.02   59.08   60.93   60.92   59.35   60.62
   60.25   62.13   58.31   60.07    59.4   61.03   58.51   59.94   58.56   60.23
   58.67   60.02    58.9   59.38   57.95    58.9   56.95   59.95   56.88   58.67
   58.15   58.27   58.56    56.8   58.67      57   58.57   57.43    58.9   57.52
   59.17   58.38   59.62   63.02    62.3   64.34    62.5   64.38   62.63   64.53
   62.61   60.01   61.37   61.72   59.72   61.43   60.79   58.71   59.86   58.78
   61.21   58.12   60.34   60.54   62.02   59.08   60.93   60.92   59.35   60.62
   60.25   62.13   58.31   60.07    59.4   61.03   58.51   59.94   58.56   60.23
   58.67   60.02    58.9   59.38   57.95    58.9   56.95   59.95   56.88   58.67
   56.87   56.97   58.55    56.8   58.67      57   58.57   57.43    58.9   57.52
   59.17   58.38   59.62   63.02    62.3   64.34    62.5   64.38   62.63   64.53
 -2410.2 -2374.5 -2352.5 -2005.3 -1731.8 -1614.7 -1517.1 -1481.9 -1473.7 -1428.3
 -1267.3 -1089.1 -1071.3  -974.6    -942  -833.5    -173   146.4   284.8   306.3
   550.9   699.9  1516.6  1711.2  1940.3  1990.3  2323.6  2366.8    2450  2573.6
  2606.9  2966.6  3000.2  3539.3  3606.6  3756.7  3923.4  4033.4  4489.9  4673.3
 4918.91  5052.9  5058.7  5439.8  5724.4  5801.3  6000.6  6134.5  6185.7    6245
  6397.7  7222.5    7253  8047.2  8261.1  8373.4  8505.3  8543.7  8556.5  9008.7
   62.61   60.01   61.37   61.72   59.72   61.43   60.79   58.71   59.86   58.78
   61.21   58.12   60.34   60.54   62.02   59.08   60.93   60.92   59.35   60.62
   60.25   62.13   58.31   60.07    59.4   61.03   58.51   59.94   58.56   60.23
   58.67   60.02    58.9   59.38   57.95    58.9   56.95   59.95   56.88   58.67
   58.15   58.27   58.56    56.8   58.67      57   58.57   57.43    58.9   57.52
   59.17   58.38   59.62   63.02    62.3   64.34    62.5   64.38   62.63   64.53
   62.55   59.95   61.31   61.66   59.66   61.37   60.73   58.65    59.8   58.72
   61.15   58.06   60.28   60.48   61.96   59.02   60.87   60.86   59.29   60.56
   60.19   62.07   58.25   60.01   59.34   60.97   58.45   59.88    58.5   60.17
   58.61   59.96   58.84   59.32   57.89   58.84   56.89   59.89   56.82   58.61
   56.81   56.91   58.49   56.74   58.61   56.94   58.51   57.37   58.84   57.46
   59.11   58.32   59.56   62.96   62.24   64.28   62.44   64.32   62.57   64.47
Pier Skew, UpSta & Num, DnSta & Num=  ,4941.8, 2 ,4941.8, 2 , 0 , 0 , 0 ,,
     1.2     1.2
   49.99   57.91
     1.2     1.2
   49.93   57.85
Pier Skew, UpSta & Num, DnSta & Num=  ,4972.1, 2 ,4972.1, 2 , 0 , 0 , 0 ,,
     1.2     1.2
   46.14   57.94
     1.2     1.2
   46.08   57.88
Pier Skew, UpSta & Num, DnSta & Num=  ,5003.2, 2 ,5003.2, 2 , 0 , 0 , 0 ,,
     1.2     1.2
   40.32   57.97
     1.2     1.2
   40.26   57.91
Pier Skew, UpSta & Num, DnSta & Num=  ,5032.5, 2 ,5032.5, 2 , 0 , 0 , 0 ,,
     1.2     1.2
   50.28   57.99
     1.2     1.2
   50.22   57.93
Abutment Skew #Up #Dn= , 2 , 2
  4918.8    4921
   56.89   56.34
  4918.8    4921
   56.83   56.28
Abutment Skew #Up #Dn= , 2 , 2
  5050.6 5052.99
   56.34   57.01
  5050.6 5052.99
   56.28   56.95
BR Coef= 1 , 1 , 0 ,1.25, 0 ,,,.8,0,2,0,
WSPro=,,,, 1 ,,,, 0 ,,,, 0 ,,,,-1 ,-1 ,-1 , 0 , 0 , 0 , 0 , 0
BR U #Sta/Elev= 30
 -2410.2   62.61 -2374.5   60.01 -1614.7   61.43 -1481.9   58.71 -1267.3   61.21
 -1089.1   58.12 -1071.3   60.34    -942   62.02  -833.5   59.08    -173   60.93
   284.8   59.35   699.9   62.13  1124.8   60.32  1516.6   58.31  1990.3   61.03
  2323.6   58.51  2898.9   59.48  3923.4   56.95  4915.5   57.73  4941.8   51.07
  4972.1   47.36  4987.8   41.64  5003.2   41.31  5013.8   42.27  5032.5   51.53
  5058.7   58.55  5439.8    56.8  7222.5   58.38    7875   61.61  9008.7   64.53
BR U #Mann= 6
 -2410.2     .99  1124.8     .99  2898.9      .1  4915.5    .035  5058.7      .1
    7875      .2
BR U Banks=4915.5,5058.7
BR D #Sta/Elev= 30
 -2410.2   62.55 -2374.5   59.95 -1614.7   61.37 -1481.9   58.65 -1267.3   61.15
 -1089.1   58.06 -1071.3   60.28    -942   61.96  -833.5   59.02    -173   60.87
   284.8   59.29   699.9   62.07  1124.8   60.26  1516.6   58.25  1990.3   60.97
  2323.6   58.45  2898.9   59.42  3923.4   56.89  4915.5   57.67  4941.8   51.01
  4972.1    47.3  4987.8   41.58  5003.2   41.25  5013.8   42.21  5032.5   51.47
  5058.7   58.49  5439.8   56.74  7222.5   58.32    7875   61.55  9008.7   64.47
BR D #Mann= 6
 -2410.2     .99  1124.8     .99  2898.9      .1  4915.5    .035  5058.7      .1
    7875      .2
BR D Banks=4915.5,5058.7
BC Design=,, 0 ,, 0 ,,,,,,

Type RM Length L Ch R = 1 ,48169.5 ,561.6,561.6,561.6
BEGIN DESCRIPTION:
Downstream Section of Bridge/Culvert/Weir
END DESCRIPTION:
XS GIS Cut Line= 6
      3133099.75     13888450.46      3131960.32     13886624.24
      3130390.38     13885328.65      3127660.29     13884047.35
      3127070.71     13883471.08      3123751.61     13882821.65
#Sta/Elev= 30
 -2410.2   62.54 -2374.5   59.94 -1614.7   61.36 -1481.9   58.64 -1267.3   61.14
 -1089.1   58.05 -1071.3   60.27    -942   61.95  -833.5   59.01    -173   60.86
   284.8   59.28   699.9   62.06  1124.8   60.25  1516.6   58.24  1990.3   60.96
  2323.6   58.44  2898.9   59.41  3923.4   56.88  4915.5   57.66  4941.8      51
  4972.1   47.29  4987.8   41.57  5003.2   41.24  5013.8    42.2  5032.5   51.46
  5058.7   58.48  5439.8   56.73  7222.5   58.31    7875   61.54  9008.7   64.46
#Mann= 6 , 1 , 0
 -2410.2     .99       0  1124.8     .99       0  2898.9      .1       0
  4915.5    .035       0  5058.7      .1       0    7875      .2       0
#XS Ineff= 2 , 0
       0    4909    57.3    5063       0    57.5
Permanent Ineff=
       F       F
Bank Sta=4915.5,5058.7
XS Rating Curve= 0
Exp/Cntr=.5,.3

Type RM Length L Ch R = 1 ,47607.9 ,1033.4,668.9,625.7
BEGIN DESCRIPTION:
Cross Section 47607.9
END DESCRIPTION:
XS GIS Cut Line= 6
      3133775.85     13888993.59      3131760.08      13885512.7
       3128801.1     13883608.04      3128005.23     13883482.38
      3125785.16     13882909.91      3123718.68     13882658.58
#Sta/Elev= 30
 -3529.1   62.26 -2742.1    59.5 -2038.9   61.81    -577   60.09  -538.5   57.97
    -504   61.59  -117.7   61.61   -60.1   58.77    53.6   59.85      82   57.03
   121.9   59.88   270.4   60.38   376.4   58.07   503.1   60.29  3096.3   59.15
  4289.9   58.96  4361.9   56.48  4928.2    58.4  4956.3   49.98  4978.7   48.16
  4988.7   41.51  5000.4   40.57  5010.3   41.13    5024   48.58  5061.6   59.13
  5425.7   56.25  5652.8   59.36  6432.9   56.58  7949.8   61.57  9199.8   64.93
#Mann= 6 , 1 , 0
 -3529.1     .99       0 -3529.1     .99       0  3096.3      .1       0
  4928.2    .035       0  5061.6      .1       0  7949.8      .2       0
Bank Sta=4928.2,5061.6
XS Rating Curve= 0
Exp/Cntr=.3,.1

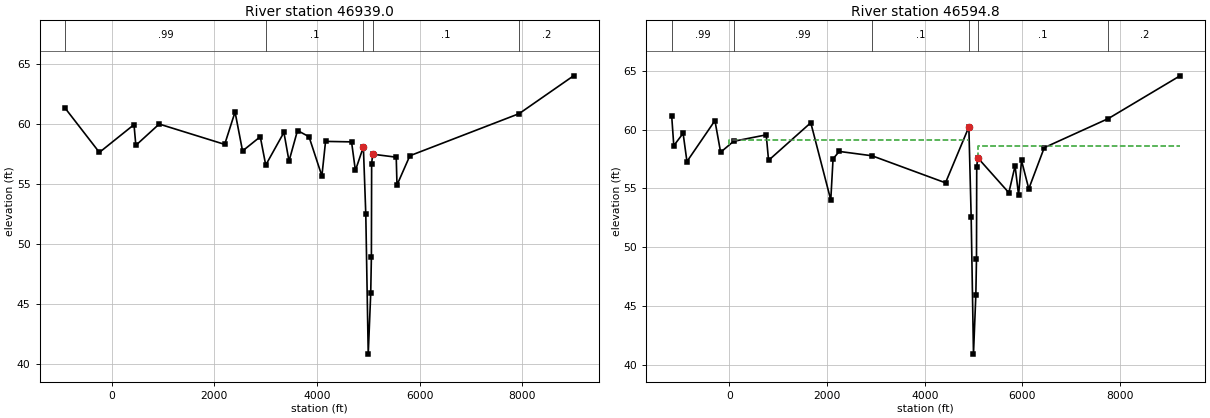
Type RM Length L Ch R = 1 ,46939.0 ,329.7,344.2,459.1
BEGIN DESCRIPTION:
Cross Section 46939.0-Interpolated
END DESCRIPTION:
XS GIS Cut Line= 6
       3132652.5     13886101.62      3129274.27     13883087.36
      3128776.59     13882790.87      3128147.09     13882797.47
      3127574.33     13882776.26      3123982.53     13882566.54
#Sta/Elev= 30
  -907.9   61.34  -241.9   57.65   432.9   59.97   468.9   58.24   923.9   60.02
  2200.4   58.32  2402.3   61.03  2548.6   57.77  2893.9   58.96  3000.5   56.59
  3354.8   59.32  3454.3   56.92  3619.6   59.48    3844   58.96  4094.9   55.68
  4166.4   58.57    4673   58.53  4748.1   56.14  4903.5   58.11  4950.7   52.47
  4998.2   40.79  5046.6   45.86  5059.8   48.91  5064.6   56.69  5083.8    57.5
  5543.8   57.25  5558.8   54.92  5809.4   57.37  7939.7   60.89  8999.6   64.05
#Mann= 5 , 1 , 0
  -907.9     .99       0  3000.5      .1       0  4903.5    .035       0
  5083.8      .1       0  7939.7      .2       0
Bank Sta=4903.5,5083.8
XS Rating Curve= 0
Exp/Cntr=.5,.3

Type RM Length L Ch R = 1 ,46594.8 ,68,68,68
BEGIN DESCRIPTION:
Upstream Section of Bridge/Culvert/Weir
END DESCRIPTION:
XS GIS Cut Line= 6
      3133496.04     13884501.45      3131572.97     13883834.25
       3130100.6     13882493.54      3129025.57     13882482.51
      3127947.65     13882448.12      3123725.07     13882280.12
#Sta/Elev= 30
 -1180.4   61.19 -1137.1   58.64  -946.3   59.69  -867.7   57.29  -294.9   60.77
  -178.3   58.08    86.4   59.01   755.1   59.56   803.1   57.39  1667.3   60.59
  2076.7   54.02  2123.4   57.52  2250.6   58.15  2921.3   57.78  4425.5   55.48
  4903.5   60.23  4950.7   52.59  4998.2   40.91  5046.6   45.98  5059.8   49.03
  5064.6   56.81  5083.8   57.62  5721.9   54.64  5849.5   56.92  5921.5   54.44
  5981.6   57.38  6130.3   54.97    6447   58.47  7761.3   60.95    9226   64.58
#Mann= 6 , 1 , 0
 -1180.4     .99       0    86.4     .99       0  2921.3      .1       0
  4903.5    .035       0  5083.8      .1       0  7761.3      .2       0
#XS Ineff= 2 , 0
       0  4904.8    59.1    5096       0   58.65
Permanent Ineff=
       F       F
Bank Sta=4903.5,5083.8
XS Rating Curve= 0
Exp/Cntr=.5,.3