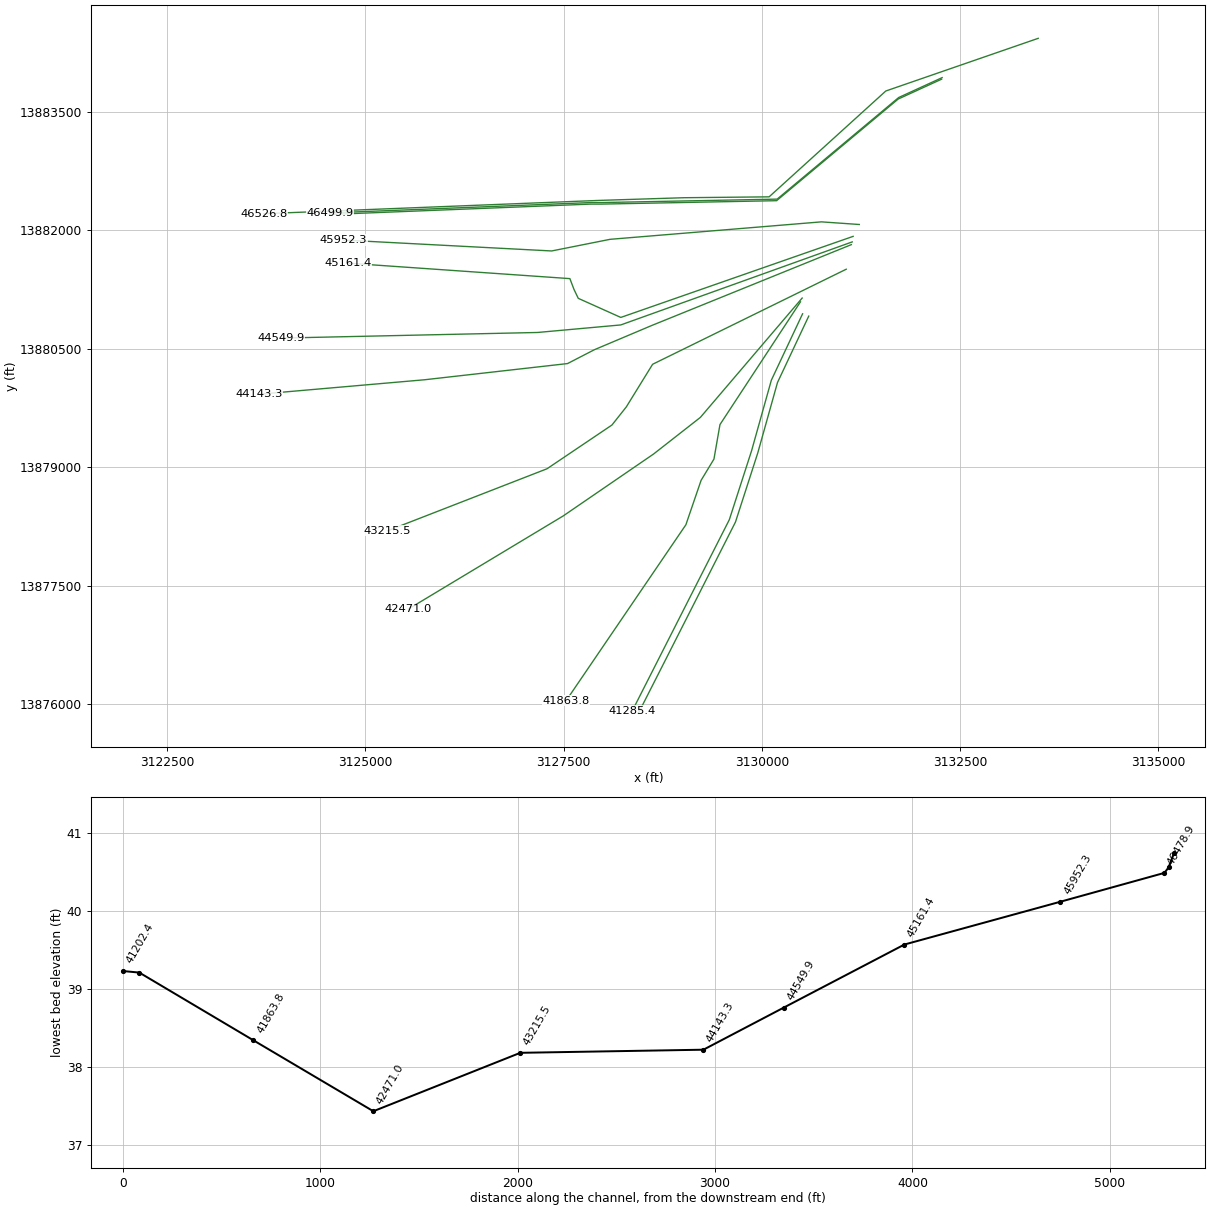
HEC-RAS study P118-00-00.PRJ: P118-00-00

--- P118-00-00.g01 (geometry) --- (continued)

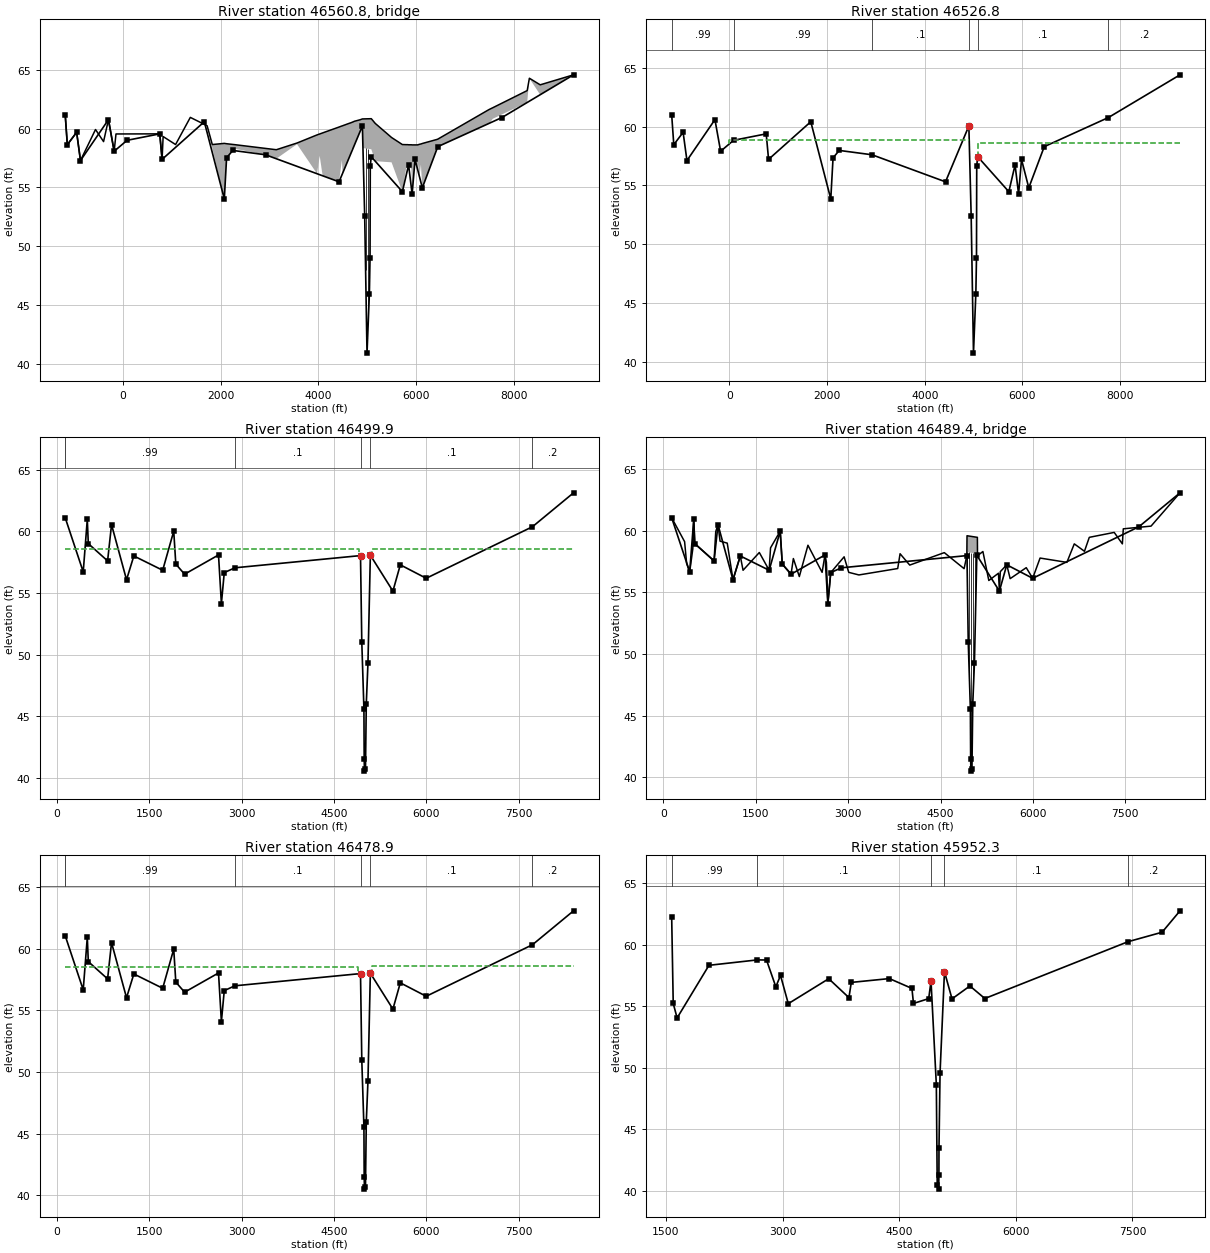
Type RM Length L Ch R = 3 ,46560.8 ,,,
BEGIN DESCRIPTION:
LITTLE YORK ROAD
Structure ID: P18-17
END DESCRIPTION:
Bridge Culvert--1,0,-1,-1, 0
Deck Dist Width WeirC Skew NumUp NumDn MinLoCord MaxHiCord MaxSubmerge Is_Ogee
10,48,2.6,0, 60, 60, , , .95, 0, 1,1,,
 -1180.4 -1137.1  -946.3  -867.7  -560.1  -395.2  -294.9  -178.3  -140.8   755.1
   803.1   824.3    1079  1380.9  1724.8  1830.8  2076.7  2123.4  2293.1  3141.6
  3565.3    3975  4029.6  4089.7  4425.5  4483.6  4498.2  4643.5    4660    4690
  4701.6    4720  4739.6  4858.3  4903.5  4915.1 5085.89  5166.1  5500.7  5721.9
  5801.3  5831.3  5849.5  5906.3  5921.5  5981.6  6026.7  6041.7  6071.7  6101.8
  6130.3  6434.5    6447  7497.1  7512.1  7572.1  8277.2  8322.2  8543.6    9226
   61.19   58.64   59.69   57.29   59.93    58.9   60.77   58.08   59.55   59.56
   57.39   59.33   58.65   60.96   60.25   58.65   58.75   58.72   58.64   58.21
   58.78   59.47   59.55   59.64   60.14   60.23   60.25   60.47   60.49   60.54
   60.56   60.59   60.63   60.76   60.83   60.83   60.85   60.45   59.25   58.65
   58.64   58.64   58.63   58.63   58.62   58.62   58.62   58.63   58.67    58.7
   58.74   59.09   59.11   61.63   61.66   61.78   63.24   64.29   63.73   64.58
   61.19   58.64   59.69   57.29   59.93    58.9   60.77   58.08   59.55   59.56
   57.39   59.33   58.65   60.96   60.24   58.35   54.02   57.52   58.29   56.61
   58.68   55.89   57.69   55.85   55.48   57.33   55.83   57.71   56.45   58.31
   56.56   56.55   58.29   58.48   60.23   58.35   58.25   56.43   57.14   54.64
   56.68   54.75   56.92   56.57   54.44   57.38   55.22      57   55.59   56.94
   54.97   57.09   58.47   60.45   59.33   60.84   62.24   64.28   62.55   64.58
 -1180.4 -1137.1  -946.3  -867.7  -560.1  -395.2  -294.9  -178.3  -140.8   755.1
   803.1   824.3    1079  1380.9  1724.8  1830.8  2076.7  2123.4  2293.1  3141.6
  3565.3    3975  4029.6  4089.7  4425.5  4483.6  4498.2  4643.5    4660    4690
  4701.6    4720  4739.6  4858.3  4903.5  4915.1 5085.89  5166.1  5500.7  5721.9
  5801.3  5831.3  5849.5  5906.3  5921.5  5981.6  6026.7  6041.7  6071.7  6101.8
  6130.3  6434.5    6447  7497.1  7512.1  7572.1  8277.2  8322.2  8543.6    9226
   61.19   58.64   59.69   57.29   59.93    58.9   60.77   58.08   59.55   59.56
   57.39   59.33   58.65   60.96   60.25   58.65   58.75   58.72   58.64   58.21
   58.78   59.47   59.55   59.64   60.14   60.23   60.25   60.47   60.49   60.54
   60.56   60.59   60.63   60.76   60.83   60.83   60.85   60.45   59.25   58.65
   58.64   58.64   58.63   58.63   58.62   58.62   58.62   58.63   58.67    58.7
   58.74   59.09   59.11   61.63   61.66   61.78   63.24   64.29   63.73   64.58
   61.08   58.53   59.58   57.18   59.82   58.79   60.66   57.97   59.44   59.45
   57.28   59.22   58.54   60.85   60.13   58.24   53.91   57.41   58.18    56.5
   58.57   55.78   57.58   55.74   55.37   57.22   55.72    57.6   56.34    58.2
   56.45   56.44   58.18   58.37   60.12   58.24   58.14   56.32   57.03   54.53
   56.57   54.64   56.81   56.46   54.33   57.27   55.11   56.89   55.48   56.83
   54.86   56.98   58.36   60.34   59.22   60.73   62.13   64.17   62.44   64.47
Pier Skew, UpSta & Num, DnSta & Num=  ,4969.5, 2 ,4969.5, 2 , 0 , 0 , 0 ,,
     1.3     1.3
   47.29   59.24
     1.3     1.3
   47.18   59.13
Pier Skew, UpSta & Num, DnSta & Num=  ,5023.4, 2 ,5023.4, 2 , 0 , 0 , 0 ,,
     1.3     1.3
   41.28   59.24
     1.3     1.3
   41.17   59.13
Abutment Skew #Up #Dn= , 2 , 2
    5079 5086.09
   57.22   58.25
    5079 5086.09
   57.11   58.14
BR Coef= 1 , 1 , 0 ,1.25, 0 ,,,.8,0,2,0,
WSPro=,,,, 1 ,,,, 0 ,,,, 0 ,,,,-1 ,-1 ,-1 , 0 , 0 , 0 , 0 , 0
BR U #Sta/Elev= 30
 -1180.4   61.19 -1137.1   58.64  -946.3   59.69  -867.7   57.29  -294.9   60.77
  -178.3   58.08    86.4   59.01   755.1   59.56   803.1   57.39  1667.3   60.59
  2076.7   54.02  2123.4   57.52  2250.6   58.15  2921.3   57.78  4425.5   55.48
  4903.5   60.23  4950.7   52.59  4998.2   40.91  5046.6   45.98  5059.8   49.03
  5064.6   56.81  5083.8   57.62  5721.9   54.64  5849.5   56.92  5921.5   54.44
  5981.6   57.38  6130.3   54.97    6447   58.47  7761.3   60.95    9226   64.58
BR U #Mann= 6
 -1180.4     .99    86.4     .99  2921.3      .1  4903.5    .035  5083.8      .1
  7761.3      .2
BR U Banks=4903.5,5083.8
BR D #Sta/Elev= 30
 -1180.4   61.08 -1137.1   58.53  -946.3   59.58  -867.7   57.18  -294.9   60.66
  -178.3   57.97    86.4    58.9   755.1   59.45   803.1   57.28  1667.3   60.48
  2076.7   53.91  2123.4   57.41  2250.6   58.04  2921.3   57.67  4425.5   55.37
  4903.5   60.12  4950.7   52.48  4998.2    40.8  5046.6   45.87  5059.8   48.92
  5064.6    56.7  5083.8   57.51  5721.9   54.53  5849.5   56.81  5921.5   54.33
  5981.6   57.27  6130.3   54.86    6447   58.36  7761.3   60.84    9226   64.47
BR D #Mann= 6
 -1180.4     .99    86.4     .99  2921.3      .1  4903.5    .035  5083.8      .1
  7761.3      .2
BR D Banks=4903.5,5083.8
BC Design=,, 0 ,, 0 ,,,,,,

Type RM Length L Ch R = 1 ,46526.8 ,26.9,26.9,26.9
BEGIN DESCRIPTION:
Downstream Section of Bridge/Culvert/Weir
END DESCRIPTION:
XS GIS Cut Line= 6
      3133488.53     13884433.86      3131565.47     13883766.67
       3130093.1     13882425.96      3129018.07     13882414.93
      3127940.15     13882380.54      3123717.56     13882212.53
#Sta/Elev= 30
 -1180.4   61.02 -1137.1   58.47  -946.3   59.52  -867.7   57.12  -294.9    60.6
  -178.3   57.91    86.4   58.84   755.1   59.39   803.1   57.22  1667.3   60.42
  2076.7   53.85  2123.4   57.35  2250.6   57.98  2921.3   57.61  4425.5   55.31
  4903.5   60.06  4950.7   52.42  4998.2   40.74  5046.6   45.81  5059.8   48.86
  5064.6   56.64  5083.8   57.45  5721.9   54.47  5849.5   56.75  5921.5   54.27
  5981.6   57.21  6130.3    54.8    6447    58.3  7761.3   60.78    9226   64.41
#Mann= 6 , 1 , 0
 -1180.4     .99       0    86.4     .99       0  2921.3      .1       0
  4903.5    .035       0  5083.8      .1       0  7761.3      .2       0
#XS Ineff= 2 , 0
       0  4904.8   58.85    5096       0   58.65
Permanent Ineff=
       F       F
Bank Sta=4903.5,5083.8
XS Rating Curve= 0
Exp/Cntr=.5,.3

Type RM Length L Ch R = 1 ,46499.9 ,21,21,21
BEGIN DESCRIPTION:
Upstream Section of Bridge/Culvert/Weir
END DESCRIPTION:
XS GIS Cut Line= 6
      3132276.82      13883936.3      3131728.44     13883684.34
      3130194.55     13882397.07      3127979.52     13882353.67
        3127847.     13882353.67      3124551.28     13882222.16
#Sta/Elev= 30
     135   61.11   427.4   56.72   493.5   60.97     510   59.01   823.2   57.61
   887.1   60.55  1130.5   56.08  1249.1   58.01  1717.5   56.85  1896.9   60.02
  1930.5   57.35  2073.1   56.53  2623.8   58.09  2670.5   54.15  2717.2   56.66
  2889.5   57.05 4928.99   58.04 4949.69   51.05 4984.39    45.6 4988.69   41.54
 4993.69   40.56 5009.49    40.7 5022.79   46.01 5049.89   49.32 5088.79   58.07
  5455.1   55.16  5575.2   57.29  5995.6    56.2  7720.6   60.38  8387.3   63.13
#Mann= 6 , 1 , 0
     135     .99       0     135     .99       0  2889.5      .1       0
 4928.99    .035       0 5088.79      .1       0  7720.6      .2       0
#XS Ineff= 2 , 0
       0  4904.8    58.6    5111       0    58.6
Permanent Ineff=
       F       F
Bank Sta=4928.99,5088.79
XS Rating Curve= 0
Exp/Cntr=.5,.3

Type RM Length L Ch R = 3 ,46489.4 ,,,
BEGIN DESCRIPTION:
15" PIPELINE
END DESCRIPTION:
Bridge Culvert--1,0,-1,-1, 0
Deck Dist Width WeirC Skew NumUp NumDn MinLoCord MaxHiCord MaxSubmerge Is_Ogee
10,1,2.6,0, 60, 60, , , .95, 0, 1,1,,
     135   344.9   377.9   427.4   477.8   493.5     510   823.2   850.5   887.1
   920.5  1037.1  1130.5  1249.1  1293.8  1557.8  1717.5  1740.2  1896.9  1930.5
  2073.1  2110.5  2207.3  2347.3  2577.2  2623.8  2647.2  2670.5  2717.2  2934.5
  3009.5  3174.5  3804.6  3842.8  3999.7  4560.7 4882.29 4926.69 4929.59 5097.99
 5100.09  5187.5  5283.6  5440.1  5455.1  5470.2  5575.2    5630  5891.2  5995.6
  6115.7    6551  6671.1  6836.2  6914.8    7319  7451.7  7466.7  7917.1  8387.3
   61.05   59.11   57.34   56.66   58.52   60.91   58.95   57.55   59.93   60.49
   59.15   58.99   56.02   57.95   56.79   58.23   56.79   58.61   59.96   57.29
   56.47   57.74   56.28   58.82   56.62   58.03   57.42   54.09    56.6   57.88
   56.62   56.41   56.93   58.13   57.21   58.22   56.92   57.98   59.59   59.46
   57.97   58.31   55.96   56.55    55.1   56.68   57.23   56.11      57   56.14
   57.78   57.43   58.93   58.33   59.46   59.86   58.93   60.15   60.37   63.07
   61.05   59.11   57.34   56.66   58.52   60.91   58.95   57.55   59.93   60.49
   59.15   58.99   56.02   57.95   56.79   58.23   56.79   58.61   59.96   57.29
   56.47   57.74   56.28   58.82   56.62   58.03   57.42   54.09    56.6   57.88
   56.62   56.41   56.93   58.13   57.21   58.22   56.92   57.95   58.26   58.13
   57.97   58.31   55.96   56.55    55.1   56.68   57.23   56.11      57   56.14
   57.78   57.43   58.93   58.33   59.46   59.86   58.93   60.15   60.37   63.07
     135   344.9   377.9   427.4   477.8   493.5     510   823.2   850.5   887.1
   920.5  1037.1  1130.5  1249.1  1293.8  1557.8  1717.5  1740.2  1896.9  1930.5
  2073.1  2110.5  2207.3  2347.3  2577.2  2623.8  2647.2  2670.5  2717.2  2934.5
  3009.5  3174.5  3804.6  3842.8  3999.7  4560.7 4882.29 4926.69 4929.59 5097.99
 5100.09  5187.5  5283.6  5440.1  5455.1  5470.2  5575.2    5630  5891.2  5995.6
  6115.7    6551  6671.1  6836.2  6914.8    7319  7451.7  7466.7  7917.1  8387.3
   61.05   59.11   57.34   56.66   58.52   60.91   58.95   57.55   59.93   60.49
   59.15   58.99   56.02   57.95   56.79   58.23   56.79   58.61   59.96   57.29
   56.47   57.74   56.28   58.82   56.62   58.03   57.42   54.09    56.6   57.88
   56.62   56.41   56.93   58.13   57.21   58.22   56.92   57.98   59.59   59.46
   57.97   58.31   55.96   56.55    55.1   56.68   57.23   56.11      57   56.14
   57.78   57.43   58.93   58.33   59.46   59.86   58.93   60.15   60.37   63.07
   61.05   59.11   57.34   56.66   58.52   60.91   58.95   57.55   59.93   60.49
   59.15   58.99   56.02   57.95   56.79   58.23   56.79   58.61   59.96   57.29
   56.47   57.74   56.28   58.82   56.62   58.03   57.42   54.09    56.6   57.88
   56.62   56.41   56.93   58.13   57.21   58.22   56.92   57.95   58.26   58.13
   57.97   58.31   55.96   56.55    55.1   56.68   57.23   56.11      57   56.14
   57.78   57.43   58.93   58.33   59.46   59.86   58.93   60.15   60.37   63.07
Pier Skew, UpSta & Num, DnSta & Num=  ,4933.9, 2 ,4933.9, 2 , 0 , 0 , 0 ,,
     1.8     1.8
   55.02   59.26
     1.8     1.8
   55.02   59.26
Pier Skew, UpSta & Num, DnSta & Num=  ,4963.7, 2 ,4963.7, 2 , 0 , 0 , 0 ,,
     1.8     1.8
   47.65   59.23
     1.8     1.8
   47.65   59.23
Pier Skew, UpSta & Num, DnSta & Num=  ,4992.8, 2 ,4992.8, 2 , 0 , 0 , 0 ,,
     1.8     1.8
    39.5   59.21
     1.8     1.8
    39.5   59.21
Pier Skew, UpSta & Num, DnSta & Num=  ,5032.8, 2 ,5032.8, 2 , 0 , 0 , 0 ,,
     1.8     1.8
   46.06   59.18
     1.8     1.8
   46.06   59.18
Pier Skew, UpSta & Num, DnSta & Num=  ,5064.4, 2 ,5064.4, 2 , 0 , 0 , 0 ,,
     1.8     1.8
   51.32   59.16
     1.8     1.8
   51.32   59.16
BR Coef= 1 , 1 , 0 ,1.25, 0 ,,,.8,0,2,0,
WSPro=,,,, 1 ,,,, 0 ,,,, 0 ,,,,-1 ,-1 ,-1 , 0 , 0 , 0 , 0 , 0
BR U #Sta/Elev= 30
     135   61.05   427.4   56.66   493.5   60.91     510   58.95   823.2   57.55
   887.1   60.49  1130.5   56.02  1249.1   57.95  1717.5   56.79  1896.9   59.96
  1930.5   57.29  2073.1   56.47  2623.8   58.03  2670.5   54.09  2717.2    56.6
  2889.5   56.99 4928.99   57.98 4949.69   50.99 4984.39   45.54 4988.69   41.48
 4993.69    40.5 5009.49   40.64 5022.79   45.95 5049.89   49.26 5088.79   58.01
  5455.1    55.1  5575.2   57.23  5995.6   56.14  7720.6   60.32  8387.3   63.07
BR U #Mann= 6
     135     .99     135     .99  2889.5      .1 4928.99     .04 5088.79      .1
  7720.6      .2
BR U Banks=4928.99,5088.79
BR D #Sta/Elev= 30
     135   61.05   427.4   56.66   493.5   60.91     510   58.95   823.2   57.55
   887.1   60.49  1130.5   56.02  1249.1   57.95  1717.5   56.79  1896.9   59.96
  1930.5   57.29  2073.1   56.47  2623.8   58.03  2670.5   54.09  2717.2    56.6
  2889.5   56.99 4928.99   57.98 4949.69   50.99 4984.39   45.54 4988.69   41.48
 4993.69    40.5 5009.49   40.64 5022.79   45.95 5049.89   49.26 5088.79   58.01
  5455.1    55.1  5575.2   57.23  5995.6   56.14  7720.6   60.32  8387.3   63.07
BR D #Mann= 6
     135     .99     135     .99  2889.5      .1 4928.99     .04 5088.79      .1
  7720.6      .2
BR D Banks=4928.99,5088.79
BC Design=,, 0 ,, 0 ,,,,,,

Type RM Length L Ch R = 1 ,46478.9 ,526.6,526.6,526.6
BEGIN DESCRIPTION:
Downstream Section of Bridge/Culvert/Weir
END DESCRIPTION:
XS GIS Cut Line= 6
      3132269.62     13883916.58      3131721.24     13883664.62
      3130187.35     13882377.35      3127972.32     13882333.95
       3127839.8     13882333.95      3124544.08     13882202.44
#Sta/Elev= 30
     135   61.04   427.4   56.65   493.5    60.9     510   58.94   823.2   57.54
   887.1   60.48  1130.5   56.01  1249.1   57.94  1717.5   56.78  1896.9   59.95
  1930.5   57.28  2073.1   56.46  2623.8   58.02  2670.5   54.08  2717.2   56.59
  2889.5   56.98 4928.99   57.97 4949.69   50.98 4984.39   45.53 4988.69   41.47
 4993.69   40.49 5009.49   40.63 5022.79   45.94 5049.89   49.25 5088.79      58
  5455.1   55.09  5575.2   57.22  5995.6   56.13  7720.6   60.31  8387.3   63.06
#Mann= 6 , 1 , 0
     135     .99       0     135     .99       0  2889.5      .1       0
 4928.99    .035       0 5088.79      .1       0  7720.6      .2       0
#XS Ineff= 2 , 0
       0  4889.8    58.5    5111       0    58.6
Permanent Ineff=
       F       F
Bank Sta=4928.99,5088.79
XS Rating Curve= 0
Exp/Cntr=.5,.3

Type RM Length L Ch R = 1 ,45952.3 ,924.1,790.9,458.9
BEGIN DESCRIPTION:
Cross Section 45952.3-Interpolated
END DESCRIPTION:
XS GIS Cut Line= 5
      3131231.12     13882075.71      3130752.66     13882109.09
      3128086.37     13881887.93      3127349.15     13881740.48
      3124722.78     13881878.71
#Sta/Elev= 30
  1574.8   62.26  1594.8   55.22  1644.8   54.04  2054.4   58.32  2677.4   58.76
  2794.4   58.75  2914.4   56.57  2974.4    57.5  3074.4    55.2  3594.4   57.23
  3854.4   55.69  3884.4   56.93  4374.4   57.24  4664.4   56.44  4684.4   55.22
  4879.9   55.61  4909.9   57.03  4978.2   48.62  4989.7   40.47  5008.6   40.12
  5011.4   41.23  5012.3   43.43  5026.1    49.6  5082.8    57.8  5179.9   55.59
  5409.9   56.64  5601.7   55.62  7443.6   60.24  7881.7   61.01  8111.7   62.75
#Mann= 5 , 1 , 0
  1574.8     .99       0  2677.4      .1       0  4909.9    .035       0
  5082.8      .1       0  7443.6      .2       0
Bank Sta=4909.9,5082.8
XS Rating Curve= 0
Exp/Cntr=.3,.1

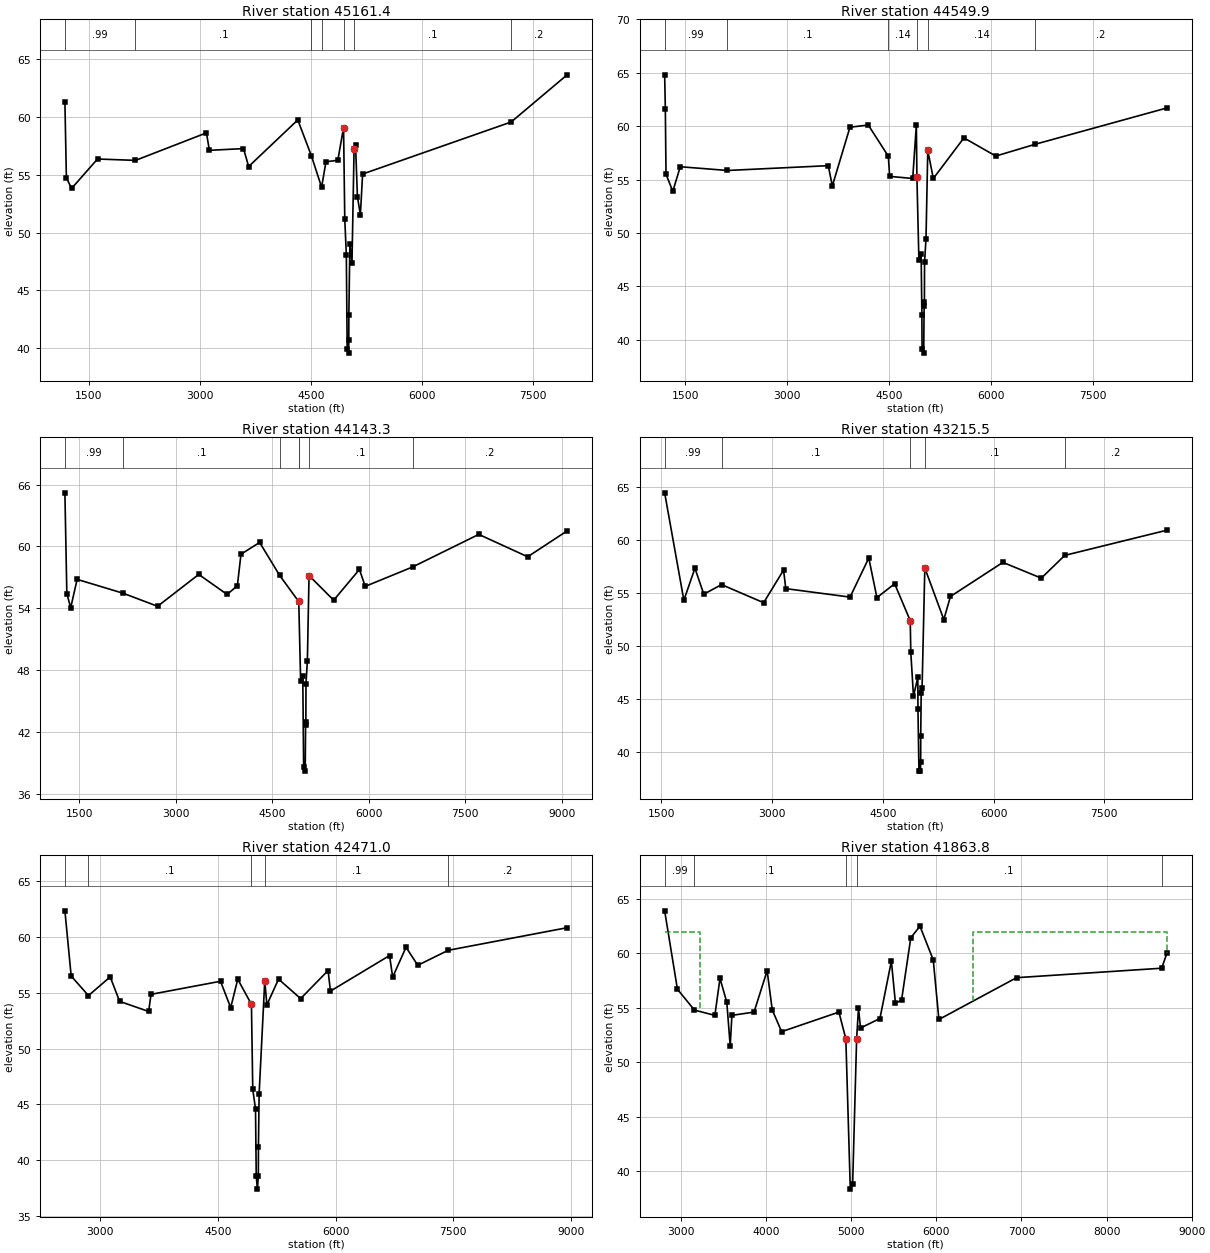
Type RM Length L Ch R = 1 ,45161.4 ,84.2,611.5,726.8
BEGIN DESCRIPTION:
Cross Section 45161.4
END DESCRIPTION:
XS GIS Cut Line= 6
      3131153.05     13881925.27      3128221.61     13880898.44
       3127684.9     13881140.27       3127630.7     13881253.89
      3127579.06     13881390.06      3124774.62     13881586.33
#Sta/Elev= 30
  1180.3   61.31  1200.3   54.74  1270.3   53.81  1620.3   56.36  2132.7   56.24
  3090.3   58.62  3130.3   57.11  3590.3   57.26  3660.3   55.71  4323.3   59.74
  4506.6   56.64  4644.5   53.92  4703.3   56.12  4863.3   56.25  4940.8   59.07
  4957.1   51.19  4978.2   48.07  4989.7   39.92  5008.6   39.57  5011.4   40.68
  5012.3   42.88  5026.1   49.05  5054.4   47.34  5082.8   57.25  5102.6   57.57
  5127.8   53.11  5167.9   51.53  5197.9   55.06  7202.6   59.56  7957.9   63.64
#Mann= 7 , 1 , 0
  1180.3     .99       0  2132.7      .1       0  4506.6     .14       0
  4644.5      .1       0  4940.8     .04       0  5082.8      .1       0
  7202.6      .2       0
Bank Sta=4940.8,5082.8
XS Rating Curve= 0
Exp/Cntr=.3,.1

Type RM Length L Ch R = 1 ,44549.9 ,128.7,406.6,456
BEGIN DESCRIPTION:
Cross Section 44549.9-Interpolated
END DESCRIPTION:
XS GIS Cut Line= 5
      3131141.92     13881855.25      3128221.33     13880803.43
      3127659.96      13880752.4      3127171.28     13880707.97
      3123932.06     13880636.67
#Sta/Elev= 30
  1195.3    64.8  1205.3    61.6  1215.3    55.5  1315.3    53.9  1425.3    56.2
    2119   55.85  3605.3    56.3  3665.3    54.4  3925.3    59.9  4195.3    60.1
  4490.7   57.18  4509.5    55.3  4849.5    55.1  4903.2    60.1  4911.5   55.22
  4940.5   47.52  4973.7   48.02  4984.6   42.31  4987.3   39.16  5011.6   38.76
  5017.5    43.2  5021.8    43.5  5023.9   47.25  5045.3   49.45  5071.3   57.72
  5153.2    55.1  5603.9    58.9  6073.9    57.2  6657.7   58.31  8593.9    61.7
#Mann= 6 , 1 , 0
  1195.3     .99       0    2119      .1       0  4490.7     .14       0
  4911.5     .04       0  5071.3     .14       0  6657.7      .2       0
Bank Sta=4911.5,5071.3
XS Rating Curve= 0
Exp/Cntr=.3,.1

Type RM Length L Ch R = 1 ,44143.3 ,430.3,927.8,1289.1
BEGIN DESCRIPTION:
Cross Section 44143.3
END DESCRIPTION:
XS GIS Cut Line= 6
      3131130.73     13881820.64      3128605.56     13880793.73
      3127887.16      13880488.9      3127549.44     13880314.01
      3125746.24     13880108.97      3123651.48     13879925.33
#Sta/Elev= 30
  1277.5    65.2  1307.5   55.44  1367.5   54.06  1467.5   56.81  2184.8   55.46
  2717.5    54.2  3357.5   57.29  3797.5   55.35  3957.5   56.19  4013.5   59.25
  4303.5   60.39  4615.1   57.19  4910.8   54.66  4911.5   54.68  4940.5   46.98
  4973.7   47.48  4987.3   38.62  5011.6   38.22  5017.5   42.66  5021.8   42.96
  5023.9   46.71  5045.3   48.91  5071.3   57.18  5454.2   54.79  5854.2   57.77
  5944.2   56.13    6680   58.01    7709   61.17    8469      59  9081.8   61.51
#Mann= 7 , 1 , 0
  1277.5     .99       0  2184.8      .1       0  4615.1     .14       0
  4910.8      .1       0  4911.5     .04       0  5071.3      .1       0
    6680      .2       0
Bank Sta=4911.5,5071.3
XS Rating Curve= 0
Exp/Cntr=.3,.1

Type RM Length L Ch R = 1 ,43215.5 ,819.6,744.5,603.8
BEGIN DESCRIPTION:
Cross Section 43215.5
END DESCRIPTION:
XS GIS Cut Line= 6
      3131066.27     13881509.26      3128623.01     13880305.08
      3128291.22     13879765.21       3128110.3     13879536.04
      3127290.11     13878981.21      3125278.04     13878195.59
#Sta/Elev= 30
  1546.9   64.47  1806.9   54.32  1956.9   57.35  2076.9   54.89  2316.9    55.8
  2886.9   54.09  3156.9   57.17  3186.9   55.42  4056.9   54.62  4310.8   58.31
  4420.8   54.57  4660.8   55.88    4872   52.39  4879.4   49.42  4915.8   45.25
  4974.7   47.05  4976.3   44.06  4989.8   38.21  5009.8   38.18  5013.3   39.08
  5013.9   41.48  5020.1   45.52  5032.2   46.03  5069.4   57.37  5326.4    52.5
  5416.4   54.68  6126.4    57.9  6646.7   56.41    6964   58.56  8346.7   60.94
#Mann= 5 , 1 , 0
  1546.9     .99       0  2316.9      .1       0    4872     .04       0
  5069.4      .1       0    6964      .2       0
Bank Sta=4872,5069.4
XS Rating Curve= 0
Exp/Cntr=.3,.1

Type RM Length L Ch R = 1 ,42471.0 ,263.2,607.2,886.4
BEGIN DESCRIPTION:
Cross Section 42471.0
END DESCRIPTION:
XS GIS Cut Line= 5
      3130510.33     13881144.11      3129225.99     13879632.54
      3128634.98     13879168.17      3127495.16     13878384.17
      3125540.06     13877203.55
#Sta/Elev= 30
  2547.4   62.32  2627.4   56.49  2847.4   54.74  3125.1   56.41  3245.1   54.22
  3615.1   53.32  3645.1   54.85    4531   56.02    4661   53.66    4751    56.2
  4925.4   53.96  4942.3   46.35  4977.3   44.61  4986.6   38.61  5001.1   37.43
  5013.5   38.59  5014.7   41.18  5023.4   45.95  5095.2   56.07  5122.4   53.91
    5271   56.21  5552.6   54.47  5902.6   56.98  5932.6   55.14    6686   58.32
    6726   56.39    6896   59.06    7046   57.45  7434.2   58.79  8949.9   60.81
#Mann= 5 , 1 , 0
  2547.4     .99       0  2847.4      .1       0  4925.4     .04       0
  5095.2      .1       0  7434.2      .2       0
Bank Sta=4925.4,5095.2
XS Rating Curve= 0
Exp/Cntr=.3,.1

Type RM Length L Ch R = 1 ,41863.8 ,586.2,578.4,493.1
BEGIN DESCRIPTION:
Cross Section 41863.8-Interpolated
END DESCRIPTION:
XS GIS Cut Line= 6
      3130488.62     13881096.02      3129472.91     13879541.25
      3129396.86     13879103.94      3129234.63     13878834.72
      3129042.82     13878272.09      3127532.88     13876045.56
#Sta/Elev= 30
  2808.1    63.9  2958.1    56.7  3158.2   54.78  3398.1    54.3  3458.1    57.7
  3538.1    55.5  3578.1    51.5  3598.1    54.3  3858.1    54.6  4012.1    58.4
  4072.1    54.8  4182.1    52.8  4855.2    54.6  4936.6   52.14    4989   38.34
  5016.4    38.8  5063.4   52.17  5085.2   54.96  5109.1   53.14  5337.1   54.01
  5471.4   59.28  5519.4   55.41  5591.4   55.71  5699.4   61.42  5807.4   62.49
  5963.4   59.39  6029.8   53.92  6941.8   57.76  8647.2   58.63  8708.1      60
#Mann= 5 , 1 , 0
  2808.1     .99       0  3158.2      .1       0  4936.6     .04       0
  5063.4      .1       0  8647.2      .2       0
#XS Ineff= 2 , 0
       0    3221      62    6435       0      62
Permanent Ineff=
       F       F
Bank Sta=4936.6,5063.4
XS Rating Curve= 0
Exp/Cntr=.5,.3

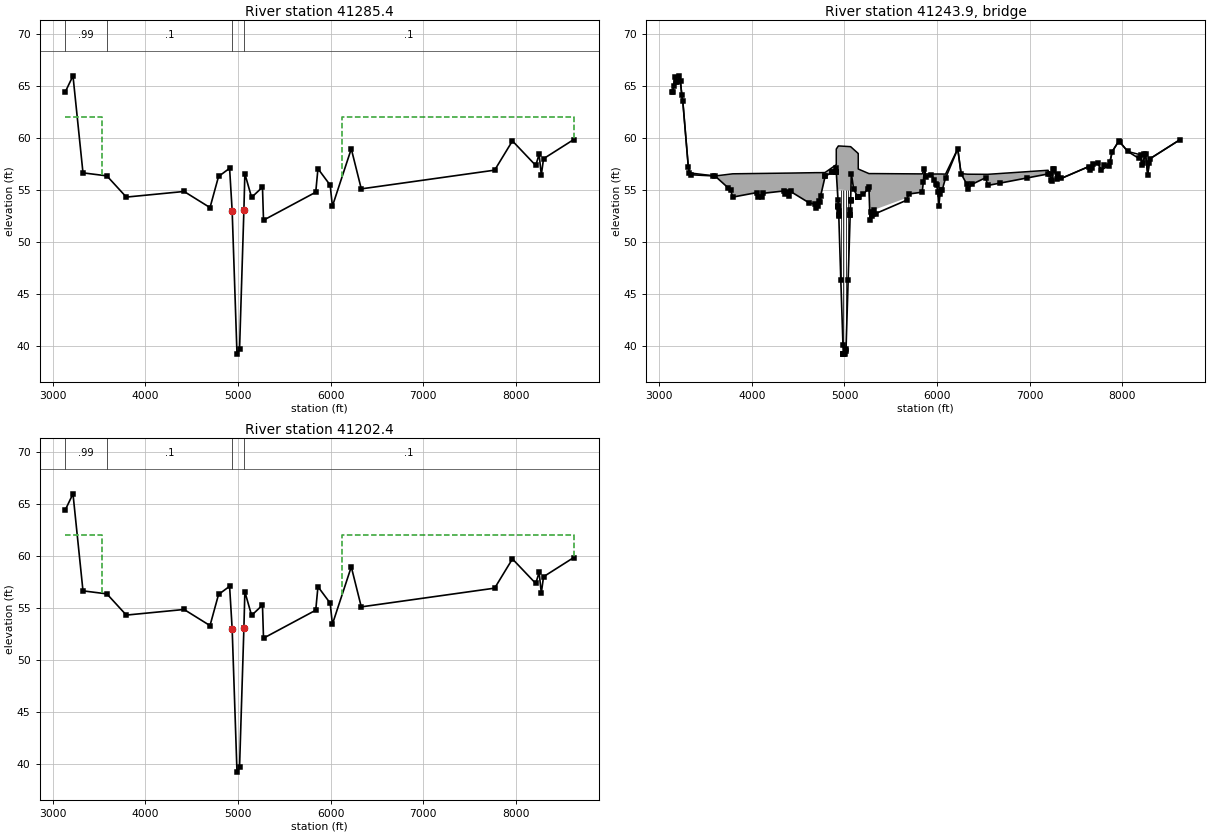
Type RM Length L Ch R = 1 ,41285.4 ,83,83,83
BEGIN DESCRIPTION:
Upstream Section of Bridge/Culvert/Weir
END DESCRIPTION:
XS GIS Cut Line= 5
      3130515.47     13880944.54      3130121.23     13880103.52
      3129871.82     13879209.78      3129590.75     13878335.71
      3128365.01     13875912.34
#Sta/Elev= 30
  3133.4   64.41  3217.4   65.97  3325.4   56.64  3583.4   56.35  3793.4   54.31
  4417.4   54.85  4697.4    53.3  4789.5   56.29    4909   57.08  4936.6   53.01
    4989   39.21  5016.4   39.67  5063.4   53.04  5073.9   56.56  5146.6   54.28
  5264.1   55.27  5275.4   52.09  5839.4   54.78  5863.4   57.04  5995.4   55.46
  6019.4   53.43  6223.4   58.95  6331.4    55.1    7772    56.9    7964   59.71
    8216   57.35    8252   58.42    8276   56.43    8300      58    8624   59.83
#Mann= 4 , 1 , 0
  3133.4     .99       0  3583.4      .1       0  4936.6     .04       0
  5063.4      .1       0
#XS Ineff= 2 , 0
       0    3531      62    6125       0      62
Permanent Ineff=
       F       F
Bank Sta=4936.6,5063.4
XS Rating Curve= 0
Exp/Cntr=.5,.3

Type RM Length L Ch R = 3 ,41243.9 ,,,
BEGIN DESCRIPTION:
JENSEN DRIVE
Structure ID: P18-15
END DESCRIPTION:
Bridge Culvert--1,0,-1,-1, 0
Deck Dist Width WeirC Skew NumUp NumDn MinLoCord MaxHiCord MaxSubmerge Is_Ogee
10,63,2.6,0, 60, 60, , , .95, 0, 1,1,,
  3133.4  3145.4  3169.4  3193.4  3217.4  3253.4  3313.4  3325.4  3601.4  3793.4
  4417.4  4697.4  4733.4  4789.5    4909 4911.19  4911.3 4933.91    4934 5066.19
  5066.3  5073.9  5099.9  5146.6  5148.6 5148.71  5264.1  5275.4  5287.4  5323.4
  5839.4  5863.4  5875.4  5935.4  5995.4  6019.4  6043.4  6091.4  6223.4  6259.4
  6331.4    6524    6548  7199.2    7244    7256    7292    7340    7736    7772
    7856    7892    7964    8060    8204    8216    8252    8276    8300    8624
   64.42   64.46   65.87   65.41   65.98   63.56   57.19   56.65   56.35   56.56
   56.63   56.67   56.67   56.68   57.42   57.44   58.94   59.24   59.24   59.17
   59.17   59.11    58.9   58.53   58.52   57.02   56.58   56.58   56.58   56.58
   56.55   57.06   56.55   56.54   56.54   56.54   56.54   56.53   58.97   56.58
   56.52   56.51   56.51    56.9   55.85   57.05    56.1   56.11   57.63   56.91
   57.34    58.7   59.72   58.71   58.37   57.36   58.43   56.44   58.01   59.84
   64.42   64.46   65.87   65.41   65.98   63.56   57.19   56.65   56.35   54.32
   54.86   53.31   53.86    56.3   57.09   56.77   56.75   53.42   55.04   54.97
   54.02   56.57   55.05   54.29    54.3    54.3   55.28    52.1   52.86   53.11
   54.79   57.05   56.22   56.48   55.47   53.44   55.02   56.14   58.96   56.57
   55.11   56.18   55.44   56.54   55.85   57.05    56.1   56.11   57.63   56.91
   57.34    58.7   59.72   58.71   58.37   57.36   58.43   56.44   58.01   59.84
  3133.4  3145.4  3169.4  3193.4  3217.4  3253.4  3313.4  3325.4  3601.4  3793.4
  4417.4  4697.4  4733.4  4789.5    4909 4911.19  4911.3 4933.91    4934 5066.19
  5066.3  5073.9  5099.9  5146.6  5148.6 5148.71  5264.1  5275.4  5287.4  5323.4
  5839.4  5863.4  5875.4  5935.4  5995.4  6019.4  6043.4  6091.4  6223.4  6259.4
  6331.4    6524    6548  7199.2    7244    7256    7292    7340    7736    7772
    7856    7892    7964    8060    8204    8216    8252    8276    8300    8624
   64.42   64.46   65.87   65.41   65.98   63.56   57.19   56.65   56.35   56.56
   56.63   56.67   56.67   56.68   57.42   57.44   58.94   59.24   59.24   59.17
   59.17   59.11    58.9   58.53   58.52   57.02   56.58   56.58   56.58   56.58
   56.55   57.06   56.55   56.54   56.54   56.54   56.54   56.53   58.97   56.58
   56.52   56.51   56.51    56.9   55.85   57.05    56.1   56.11   57.63   56.91
   57.34    58.7   59.72   58.71   58.37   57.36   58.43   56.44   58.01   59.84
    64.4   64.44   65.85   65.39   65.96   63.54   57.17   56.63   56.33    54.3
   54.84   53.29   53.84   56.28   57.07   56.75   56.73    53.4   55.02   54.95
      54   56.55   55.03   54.27   54.28   54.28   55.26   52.08   52.84   53.09
   54.77   57.03    56.2   56.46   55.45   53.42      55   56.12   58.94   56.55
   55.09   56.16   55.42   56.52   55.83   57.03   56.08   56.09   57.61   56.89
   57.32   58.68    59.7   58.69   58.35   57.34   58.41   56.42   57.99   59.82
Pier Skew, UpSta & Num, DnSta & Num=  ,4960.6, 2 ,4960.6, 2 , 0 , 0 , 0 ,,
     1.3     1.3
    45.1   56.12
     1.3     1.3
   45.08    56.1
Pier Skew, UpSta & Num, DnSta & Num=  ,4986.6, 2 ,4986.6, 2 , 0 , 0 , 0 ,,
     1.3     1.3
   38.25    56.2
     1.3     1.3
   38.23   56.18
Pier Skew, UpSta & Num, DnSta & Num=  ,5013.5, 2 ,5013.5, 2 , 0 , 0 , 0 ,,
     1.3     1.3
   38.47   56.12
     1.3     1.3
   38.45    56.1
Pier Skew, UpSta & Num, DnSta & Num=  ,5039.8, 2 ,5039.8, 2 , 0 , 0 , 0 ,,
     1.3     1.3
   45.16   56.05
     1.3     1.3
   45.14   56.03
Abutment Skew #Up #Dn= , 2 , 2
  4933.8  4938.5
   55.04   52.52
  4933.8  4938.5
   55.02    52.5
Abutment Skew #Up #Dn= , 2 , 2
  5061.9 5066.39
   52.58   54.97
  5061.9 5066.39
   52.56   54.95
BR Coef= 1 , 1 , 0 ,1.25, 0 ,,,.8,0,2,0,
WSPro=,,,, 1 ,,,, 0 ,,,, 0 ,,,,-1 ,-1 ,-1 , 0 , 0 , 0 , 0 , 0
BR U #Sta/Elev= 138
  3133.4   64.42  3145.4   64.46  3157.4   65.02  3169.4   65.87  3181.4    65.4
  3193.4   65.41  3217.4   65.98  3229.4   65.49  3241.4   64.13  3253.4   63.56
  3313.4   57.19  3325.4   56.65  3337.4   56.47  3583.4   56.36  3601.4   56.35
  3740.6   55.23  3769.4      55  3793.4   54.32  4057.4   54.76  4069.4   54.32
  4105.4   54.34  4117.4   54.68  4345.4   54.91  4357.4   54.61  4393.4   54.79
  4405.4   54.47  4417.4   54.86  4613.4   53.79  4685.4   53.61  4697.4   53.31
  4709.4   53.44  4721.4   53.99  4733.4   53.86  4741.9   54.41  4789.5    56.3
  4790.8   56.31  4864.9   56.72  4865.2   56.72    4909   57.09 4911.19   56.77
  4911.3   56.75 4911.41   56.73  4929.7   54.04  4933.8   53.43 4933.91   53.42
    4934    53.4  4936.6   53.02  4938.4   52.55  4938.5   52.52  4960.5    46.3
  4983.6   40.12  4986.6   39.26  4986.9   39.26    4989   39.22  4996.3   39.22
  5008.3   39.26  5013.5    39.5  5016.4   39.68  5039.8   46.34  5061.8   52.55
  5061.9   52.58  5063.4   53.05 5066.19   53.99  5066.3   54.02  5066.4   54.06
  5073.9   56.57  5099.9   55.05  5146.6   54.29 5148.49    54.3  5148.6    54.3
 5148.71    54.3  5157.6   54.34  5205.2   54.57  5250.4   55.11  5264.1   55.28
  5275.4    52.1  5287.4   52.86  5299.4   52.53  5311.4   52.66  5323.4   53.11
  5335.4   52.73  5671.4   54.02  5695.4   54.62  5839.4   54.79  5851.4   55.75
  5863.4   57.05  5875.4   56.22  5935.4   56.48  5971.4   56.01  5983.4   55.55
  5995.4   55.47  6007.4   54.85  6019.4   53.44  6031.4    54.6  6043.4   55.02
  6055.4   55.02  6091.4   56.14  6223.4   58.96  6259.4   56.57  6319.4   55.59
  6331.4   55.11    6380   55.56    6524   56.18    6548   55.44  6683.7   55.67
  6967.2   56.15  7199.2   56.54    7220   56.58    7232   55.93    7244   55.85
    7256   57.05    7268      57    7292    56.1    7304    56.5    7340   56.11
    7640   57.26    7652   56.94    7676    57.1    7688   57.48    7736   57.63
    7772   56.91    7808   57.41    7856   57.34    7868   57.68    7892    58.7
    7964   59.72    7976   59.59    8060   58.71    8180   58.04    8204   58.37
    8216   57.36    8228   57.58    8240   58.46    8252   58.43    8276   56.44
    8288   57.64    8300   58.01    8624   59.84
BR U #Mann= 4
  3133.4     .99  3583.4      .1  4936.6     .04  5063.4      .1
BR U Banks=4936.6,5063.4
BR D #Sta/Elev= 138
  3133.4    64.4  3145.4   64.44  3157.4      65  3169.4   65.85  3181.4   65.38
  3193.4   65.39  3217.4   65.96  3229.4   65.47  3241.4   64.11  3253.4   63.54
  3313.4   57.17  3325.4   56.63  3337.4   56.45  3583.4   56.34  3601.4   56.33
  3740.6   55.21  3769.4   54.98  3793.4    54.3  4057.4   54.74  4069.4    54.3
  4105.4   54.32  4117.4   54.66  4345.4   54.89  4357.4   54.59  4393.4   54.77
  4405.4   54.45  4417.4   54.84  4613.4   53.77  4685.4   53.59  4697.4   53.29
  4709.4   53.42  4721.4   53.97  4733.4   53.84  4741.9   54.39  4789.5   56.28
  4790.8   56.29  4864.9    56.7  4865.2    56.7    4909   57.07 4911.19   56.75
  4911.3   56.73 4911.41   56.71  4929.7   54.02  4933.8   53.41 4933.91    53.4
    4934   53.38  4936.6      53  4938.4   52.53  4938.5    52.5  4960.5   46.28
  4983.6    40.1  4986.6   39.24  4986.9   39.24    4989    39.2  4996.3    39.2
  5008.3   39.24  5013.5   39.48  5016.4   39.66  5039.8   46.32  5061.8   52.53
  5061.9   52.56  5063.4   53.03 5066.19   53.97  5066.3      54  5066.4   54.04
  5073.9   56.55  5099.9   55.03  5146.6   54.27 5148.49   54.28  5148.6   54.28
 5148.71   54.28  5157.6   54.32  5205.2   54.55  5250.4   55.09  5264.1   55.26
  5275.4   52.08  5287.4   52.84  5299.4   52.51  5311.4   52.64  5323.4   53.09
  5335.4   52.71  5671.4      54  5695.4    54.6  5839.4   54.77  5851.4   55.73
  5863.4   57.03  5875.4    56.2  5935.4   56.46  5971.4   55.99  5983.4   55.53
  5995.4   55.45  6007.4   54.83  6019.4   53.42  6031.4   54.58  6043.4      55
  6055.4      55  6091.4   56.12  6223.4   58.94  6259.4   56.55  6319.4   55.57
  6331.4   55.09    6380   55.54    6524   56.16    6548   55.42  6683.7   55.65
  6967.2   56.13  7199.2   56.52    7220   56.56    7232   55.91    7244   55.83
    7256   57.03    7268   56.98    7292   56.08    7304   56.48    7340   56.09
    7640   57.24    7652   56.92    7676   57.08    7688   57.46    7736   57.61
    7772   56.89    7808   57.39    7856   57.32    7868   57.66    7892   58.68
    7964    59.7    7976   59.57    8060   58.69    8180   58.02    8204   58.35
    8216   57.34    8228   57.56    8240   58.44    8252   58.41    8276   56.42
    8288   57.62    8300   57.99    8624   59.82
BR D #Mann= 4
  3133.4     .99  3583.4      .1  4936.6     .04  5063.4      .1
BR D Banks=4936.6,5063.4
BC Design=,, 0 ,, 0 ,,,,,,

Type RM Length L Ch R = 1 ,41202.4 ,16.7,16.7,16.7
BEGIN DESCRIPTION:
Downstream Section of Bridge/Culvert/Weir
END DESCRIPTION:
XS GIS Cut Line= 5
      3130593.08     13880915.13      3130198.85      13880074.1
      3129949.44     13879180.36      3129668.37     13878306.29
      3128442.62     13875882.93
#Sta/Elev= 30
  3133.4   64.43  3217.4   65.99  3325.4   56.66  3583.4   56.37  3793.4   54.33
  4417.4   54.87  4697.4   53.32  4789.5   56.31    4909    57.1  4936.6   53.03
    4989   39.23  5016.4   39.69  5063.4   53.06  5073.9   56.58  5146.6    54.3
  5264.1   55.29  5275.4   52.11  5839.4    54.8  5863.4   57.06  5995.4   55.48
  6019.4   53.45  6223.4   58.97  6331.4   55.12    7772   56.92    7964   59.73
    8216   57.37    8252   58.44    8276   56.45    8300   58.02    8624   59.85
#Mann= 4 , 1 , 0
  3133.4     .99       0  3583.4      .1       0  4936.6     .04       0
  5063.4      .1       0
#XS Ineff= 2 , 0
       0    3531      62    6125       0      62
Permanent Ineff=
       F       F
Bank Sta=4936.6,5063.4
XS Rating Curve= 0
Exp/Cntr=.5,.3