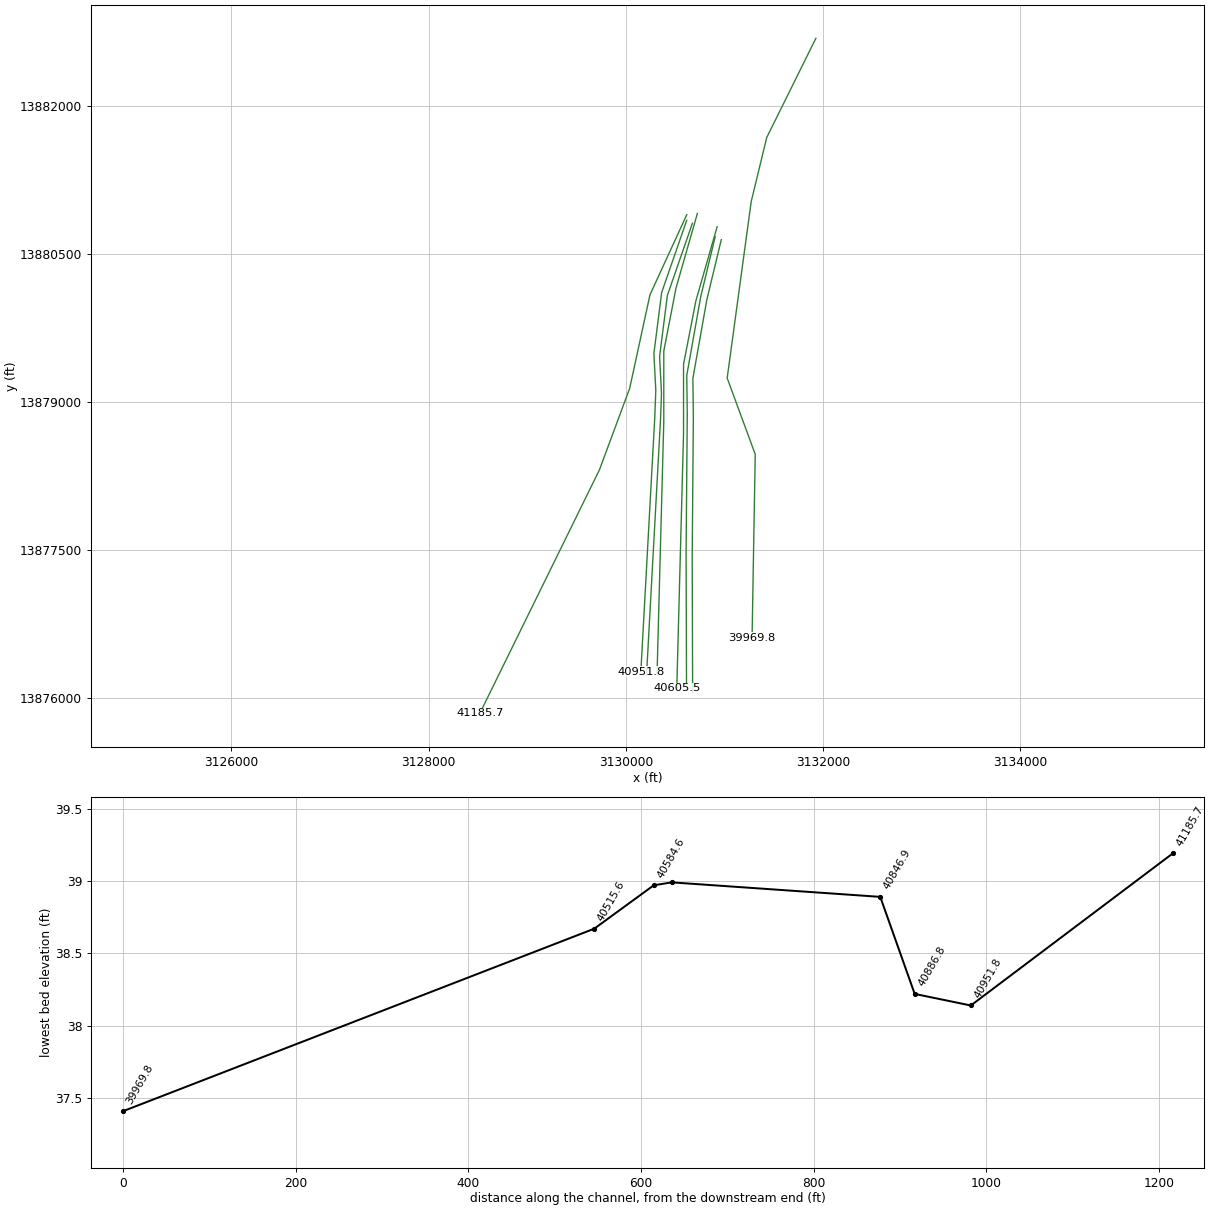
HEC-RAS study P118-00-00.PRJ: P118-00-00

--- P118-00-00.g01 (geometry) --- (continued)

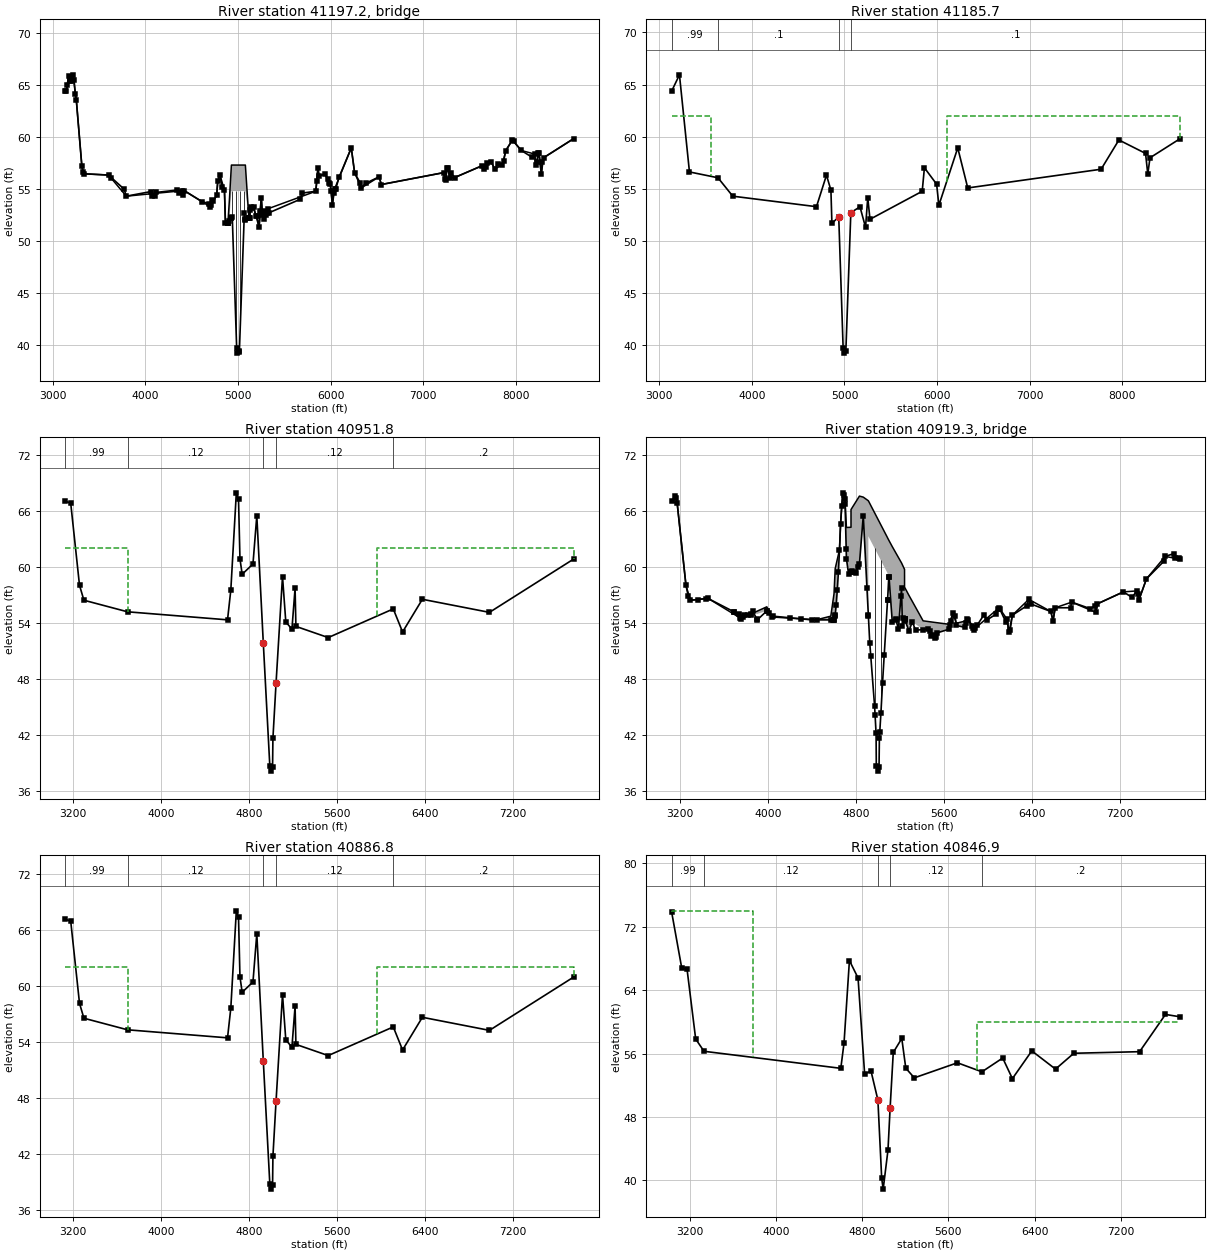
Type RM Length L Ch R = 3 ,41197.2 ,,,
BEGIN DESCRIPTION:
30" PIPELINE
END DESCRIPTION:
Bridge Culvert--1,0,-1,-1, 0
Deck Dist Width WeirC Skew NumUp NumDn MinLoCord MaxHiCord MaxSubmerge Is_Ogee
10,3,2.6,0, 60, 60, , , .95, 0, 1,1,,
  3133.4  3145.4  3169.4  3193.4  3217.4  3253.4  3313.4  3337.4  3601.4  3793.4
  4417.4  4697.4  4769.4  4781.4  4805.4  4853.4 4864.24 4890.74 4906.34 4928.44
 5079.44 5117.44 5128.34  5129.4  5167.4  5227.4  5251.4  5263.4  5275.4  5287.4
  5323.4  5839.4  5863.4  5875.4  5935.4  5995.4  6019.4  6043.4  6223.4  6259.4
  6331.4    6524    6548    7220    7244    7256    7292    7340    7736    7772
    7856    7892    7964    8060    8204    8216    8252    8276    8300    8624
   64.42   64.46   65.87   65.41   65.98   63.56   57.19   56.47   56.35   54.32
   54.86   53.31    54.4   55.79   56.34    54.9    51.7   51.75   53.89   57.31
   57.31   52.18   52.22   53.04    53.3   51.33   54.18   52.54    52.1   52.86
   53.11   54.79   57.05   56.22   56.48   55.47   53.44   55.02   58.96   56.57
   55.11   56.18   55.44   56.58   55.85   57.05    56.1   56.11   57.63   56.91
   57.34    58.7   59.72   58.71   58.37   57.36   58.43   56.44   58.01   59.84
   64.42   64.46   65.87   65.41   65.98   63.56   57.19   56.47   56.35   54.32
   54.86   53.31    54.4   55.79   56.34    54.9    51.7   51.74   51.92   54.81
   54.81   52.18   52.22   53.04    53.3   51.33   54.18   52.54    52.1   52.86
   53.11   54.79   57.05   56.22   56.48   55.47   53.44   55.02   58.96   56.57
   55.11   56.18   55.44   56.58   55.85   57.05    56.1   56.11   57.63   56.91
   57.34    58.7   59.72   58.71   58.37   57.36   58.43   56.44   58.01   59.84
  3133.4  3145.4  3169.4  3193.4  3217.4  3253.4  3313.4  3337.4  3601.4  3793.4
  4417.4  4697.4  4769.4  4781.4  4805.4  4853.4 4864.24 4890.74 4906.34 4928.44
 5079.44 5117.44 5128.34  5129.4  5167.4  5227.4  5251.4  5263.4  5275.4  5287.4
  5323.4  5839.4  5863.4  5875.4  5935.4  5995.4  6019.4  6043.4  6223.4  6259.4
  6331.4    6524    6548    7220    7244    7256    7292    7340    7736    7772
    7856    7892    7964    8060    8204    8216    8252    8276    8300    8624
   64.42   64.46   65.87   65.41   65.98   63.56   57.19   56.47   56.35   54.32
   54.86   53.31    54.4   55.79   56.34    54.9    51.7   51.75   53.89   57.31
   57.31   52.18   52.22   53.04    53.3   51.33   54.18   52.54    52.1   52.86
   53.11   54.79   57.05   56.22   56.48   55.47   53.44   55.02   58.96   56.57
   55.11   56.18   55.44   56.58   55.85   57.05    56.1   56.11   57.63   56.91
   57.34    58.7   59.72   58.71   58.37   57.36   58.43   56.44   58.01   59.84
   64.42   64.46   65.87   65.41   65.98   63.56   57.19   56.47   56.35   54.32
   54.86   53.31    54.4   55.79   56.34    54.9    51.7   51.74   51.92   54.81
   54.81   52.18   52.22   53.04    53.3   51.33   54.18   52.54    52.1   52.86
   53.11   54.79   57.05   56.22   56.48   55.47   53.44   55.02   58.96   56.57
   55.11   56.18   55.44   56.58   55.85   57.05    56.1   56.11   57.63   56.91
   57.34    58.7   59.72   58.71   58.37   57.36   58.43   56.44   58.01   59.84
Pier Skew, UpSta & Num, DnSta & Num=  ,4938.1, 2 ,4938.1, 2 , 0 , 0 , 0 ,,
       2       2
      51   55.81
       2       2
      51   55.81
Pier Skew, UpSta & Num, DnSta & Num=  ,4980.7, 2 ,4980.7, 2 , 0 , 0 , 0 ,,
       2       2
   39.71   55.81
       2       2
   39.71   55.81
Pier Skew, UpSta & Num, DnSta & Num=  ,5025.3, 2 ,5025.3, 2 , 0 , 0 , 0 ,,
       2       2
   40.81   55.81
       2       2
   40.81   55.81
Pier Skew, UpSta & Num, DnSta & Num=  ,5067.9, 2 ,5067.9, 2 , 0 , 0 , 0 ,,
       2       2
   51.34   55.81
       2       2
   51.34   55.81
BR Coef= 1 , 1 , 0 ,1.25, 0 ,,,.8,0,2,0,
WSPro=,,,, 1 ,,,, 0 ,,,, 0 ,,,,-1 ,-1 ,-1 , 0 , 0 , 0 , 0 , 0
BR U #Sta/Elev= 127
  3133.4   64.42  3145.4   64.46  3157.4   65.02  3169.4   65.87  3181.4    65.4
  3193.4   65.41  3217.4   65.98  3229.4   65.49  3241.4   64.13  3253.4   63.56
  3313.4   57.19  3325.4   56.65  3337.4   56.47  3601.4   56.35  3633.4   56.09
  3769.4      55  3793.4   54.32  4057.4   54.76  4069.4   54.32  4105.4   54.34
  4117.4   54.68  4345.4   54.91  4357.4   54.61  4393.4   54.79  4405.4   54.47
  4417.4   54.86  4613.4   53.79  4685.4   53.61  4697.4   53.31  4709.4   53.44
  4721.4   53.99  4733.4   53.86  4769.4    54.4  4781.4   55.79  4805.4   56.34
  4829.4   55.19  4853.4    54.9 4864.24    51.7 4890.14   51.73 4890.54   51.73
 4890.65   51.74 4890.74   51.74 4906.34   51.92 4923.94    52.2 4928.44   52.25
 4937.84   52.34 4985.24   39.78 4993.74   39.24 5005.74   39.36 5014.74   39.43
 5068.54   52.74 5079.44   52.08 5079.74   52.06 5117.23   52.18 5117.34   52.18
 5117.44   52.18 5128.34   52.22  5129.4   53.04  5141.4   53.24  5155.4   53.17
  5167.4    53.3  5191.4   52.44  5203.4   52.42  5227.4   51.33  5239.4   52.91
  5251.4   54.18  5263.4   52.54  5275.4    52.1  5287.4   52.86  5299.4   52.53
  5311.4   52.66  5323.4   53.11  5335.4   52.73  5671.4   54.02  5695.4   54.62
  5839.4   54.79  5851.4   55.75  5863.4   57.05  5875.4   56.22  5935.4   56.48
  5971.4   56.01  5983.4   55.55  5995.4   55.47  6007.4   54.85  6019.4   53.44
  6031.4    54.6  6043.4   55.02  6055.4   55.02  6091.4   56.14  6223.4   58.96
  6259.4   56.57  6319.4   55.59  6331.4   55.11    6380   55.56    6524   56.18
    6548   55.44    7220   56.58    7232   55.93    7244   55.85    7256   57.05
    7268      57    7292    56.1    7304    56.5    7340   56.11    7640   57.26
    7652   56.94    7676    57.1    7688   57.48    7736   57.63    7772   56.91
    7808   57.41    7856   57.34    7868   57.68    7892    58.7    7964   59.72
    7976   59.59    8060   58.71    8180   58.04    8204   58.37    8216   57.36
    8228   57.58    8240   58.46    8252   58.43    8276   56.44    8288   57.64
    8300   58.01    8624   59.84
BR U #Mann= 4
  3133.4     .99  3633.4      .1 4937.84    .045 5068.54      .1
BR U Banks=4937.84,5068.54
BR D #Sta/Elev= 127
  3133.4   64.42  3145.4   64.46  3157.4   65.02  3169.4   65.87  3181.4    65.4
  3193.4   65.41  3217.4   65.98  3229.4   65.49  3241.4   64.13  3253.4   63.56
  3313.4   57.19  3325.4   56.65  3337.4   56.47  3601.4   56.35  3633.4   56.09
  3769.4      55  3793.4   54.32  4057.4   54.76  4069.4   54.32  4105.4   54.34
  4117.4   54.68  4345.4   54.91  4357.4   54.61  4393.4   54.79  4405.4   54.47
  4417.4   54.86  4613.4   53.79  4685.4   53.61  4697.4   53.31  4709.4   53.44
  4721.4   53.99  4733.4   53.86  4769.4    54.4  4781.4   55.79  4805.4   56.34
  4829.4   55.19  4853.4    54.9 4864.24    51.7 4890.14   51.73 4890.54   51.73
 4890.65   51.74 4890.74   51.74 4906.34   51.92 4923.94    52.2 4928.44   52.25
 4937.84   52.34 4985.24   39.78 4993.74   39.24 5005.74   39.36 5014.74   39.43
 5068.54   52.74 5079.44   52.08 5079.74   52.06 5117.23   52.18 5117.34   52.18
 5117.44   52.18 5128.34   52.22  5129.4   53.04  5141.4   53.24  5155.4   53.17
  5167.4    53.3  5191.4   52.44  5203.4   52.42  5227.4   51.33  5239.4   52.91
  5251.4   54.18  5263.4   52.54  5275.4    52.1  5287.4   52.86  5299.4   52.53
  5311.4   52.66  5323.4   53.11  5335.4   52.73  5671.4   54.02  5695.4   54.62
  5839.4   54.79  5851.4   55.75  5863.4   57.05  5875.4   56.22  5935.4   56.48
  5971.4   56.01  5983.4   55.55  5995.4   55.47  6007.4   54.85  6019.4   53.44
  6031.4    54.6  6043.4   55.02  6055.4   55.02  6091.4   56.14  6223.4   58.96
  6259.4   56.57  6319.4   55.59  6331.4   55.11    6380   55.56    6524   56.18
    6548   55.44    7220   56.58    7232   55.93    7244   55.85    7256   57.05
    7268      57    7292    56.1    7304    56.5    7340   56.11    7640   57.26
    7652   56.94    7676    57.1    7688   57.48    7736   57.63    7772   56.91
    7808   57.41    7856   57.34    7868   57.68    7892    58.7    7964   59.72
    7976   59.59    8060   58.71    8180   58.04    8204   58.37    8216   57.36
    8228   57.58    8240   58.46    8252   58.43    8276   56.44    8288   57.64
    8300   58.01    8624   59.84
BR D #Mann= 4
  3133.4     .99  3633.4      .1 4937.84    .045 5068.54      .1
BR D Banks=4937.84,5068.54
BC Design=,, 0 ,, 0 ,,,,,,

Type RM Length L Ch R = 1 ,41185.7 ,233.9,233.9,233.9
BEGIN DESCRIPTION:
Downstream Section of Bridge/Culvert/Weir
END DESCRIPTION:
XS GIS Cut Line= 5
      3130618.21     13880898.81      3130245.18     13880087.87
      3130040.12     13879142.81      3129733.14     13878316.06
      3128520.06     13875849.17
#Sta/Elev= 30
  3133.4   64.37  3217.4   65.93  3325.4    56.6  3633.4   56.04  3793.4   54.27
  4697.4   53.26  4805.4   56.29  4853.4   54.85 4864.24   51.65 4937.84   52.29
 4985.24   39.73 4993.74   39.19 5014.74   39.38 5068.54   52.69  5167.4   53.25
  5227.4   51.28  5251.4   54.13  5275.4   52.05  5839.4   54.74  5863.4      57
  5995.4   55.42  6019.4   53.39  6223.4   58.91  6331.4   55.06    7772   56.86
    7964   59.67    8252   58.38    8276   56.39    8300   57.96    8624   59.79
#Mann= 4 , 1 , 0
  3133.4     .99       0  3633.4      .1       0 4937.84     .04       0
 5068.54      .1       0
#XS Ineff= 2 , 0
       0    3554      62    6102       0      62
Permanent Ineff=
       F       F
Bank Sta=4937.84,5068.54
XS Rating Curve= 0
Exp/Cntr=.5,.3

Type RM Length L Ch R = 1 ,40951.8 ,65,65,65
BEGIN DESCRIPTION:
Upstream Section of Bridge/Culvert/Weir
END DESCRIPTION:
XS GIS Cut Line= 6
      3130617.91     13880842.81      3130363.96     13880112.05
      3130284.98     13879492.67      3130304.33     13879121.61
      3130294.45     13878854.83       3130152.9     13876272.36
#Sta/Elev= 30
  3126.1   67.04  3176.1   66.84  3256.1   58.04  3296.1   56.44    3693    55.2
  4602.3   54.34  4632.3   57.54  4682.3   67.94  4702.3   67.24 4715.34   60.88
 4735.43   59.22 4833.66   60.32 4868.54   65.49  4927.7   51.85 4987.12   38.65
 4999.57   38.14 5012.01   38.61 5015.05   41.64 5043.76    47.6 5102.31   58.98
 5132.24   54.12 5188.01   53.34 5216.63   57.73  5224.2   53.64    5518   52.44
  6109.6   55.51  6194.2   53.04  6374.2   56.54  6984.2   55.14    7749   60.84
#Mann= 5 , 1 , 0
  3126.1     .99       0    3693     .12       0  4927.7     .04       0
 5043.76     .12       0  6109.6      .2       0
#XS Ineff= 2 , 0
       0    3693      62    5963       0      62
Permanent Ineff=
       F       F
Bank Sta=4927.7,5043.76
XS Rating Curve= 0
Exp/Cntr=.5,.3

Type RM Length L Ch R = 3 ,40919.3 ,,,
BEGIN DESCRIPTION:
ACCESS ROAD FOR US HWY 59 SOUTH, SKEW ANGLE OF 30 DEGREES
Structure ID: P18-14
END DESCRIPTION:
Bridge Culvert--1,0,-1,-1, 0
Deck Dist Width WeirC Skew NumUp NumDn MinLoCord MaxHiCord MaxSubmerge Is_Ogee
10,45,2.6,0, 60, 60, , , .95, 0, 1,1,,
  3126.1  3176.1  3256.1  3296.1  3456.1  3756.1  3991.2  4034.7  4443.2  4573.2
  4602.3  4613.2  4652.3  4662.3  4682.3  4702.3 4715.34 4735.43 4756.89    4757
 4833.66 4868.54 4914.82 4914.91 5089.24 5089.35 5102.31 5132.24 5188.01 5216.63
  5224.2  5243.9 5244.01  5284.2  5314.2  5412.6    5518    5648  5684.2  5714.2
  5794.2  5814.2  5884.2  6104.2  6174.2  6194.2  6224.2  6374.2  6574.2  6594.2
  6614.2  6764.2  6984.2  6994.2  7234.2  7354.2  7374.2  7444.2  7614.2    7749
      67    66.8      58    56.4   56.61   54.45    55.7   54.61   54.31    54.7
   57.09    59.8   61.81   64.61   67.91   67.21    64.2   64.21   64.22   66.12
   67.56   67.45   67.06   67.06    63.1   63.09    62.8   62.15   60.99    60.4
   60.21   59.71   57.81   56.92   56.29    54.2   54.03   53.83   55.01   53.94
   54.17   54.41   53.39    55.6    54.4      53    54.8    56.5    55.2    54.2
    55.6    56.2    55.1      56    57.3    57.4    56.4    58.7    61.1    60.8
      67    66.8      58    56.4    56.6    54.4   55.26    54.6    54.3    54.3
    54.3   54.81    61.8    64.6    67.9    67.2   60.84   59.18   59.46   59.46
   60.28   65.45   54.78   63.26    59.3   56.42   58.94   54.08    53.3   57.69
    53.6    54.4    54.4    53.1    54.1   53.26    52.4    53.3      55    53.7
    53.5    54.4   53.38    55.6    54.4      53    54.8    56.5    55.2    54.2
    55.6    56.2    55.1      56    57.3    57.4    56.4    58.7    61.1    60.8
  3126.1  3176.1  3256.1  3296.1  3456.1  3756.1  3991.2  4034.7  4443.2  4573.2
  4602.3  4613.2  4652.3  4662.3  4682.3  4702.3 4715.34 4735.43 4756.89    4757
 4833.66 4868.54 4914.82 4914.91 5089.24 5089.35 5102.31 5132.24 5188.01 5216.63
  5224.2  5243.9 5244.01  5284.2  5314.2  5412.6    5518    5648  5684.2  5714.2
  5794.2  5814.2  5884.2  6104.2  6174.2  6194.2  6224.2  6374.2  6574.2  6594.2
  6614.2  6764.2  6984.2  6994.2  7234.2  7354.2  7374.2  7444.2  7614.2    7749
      67    66.8      58    56.4   56.61   54.45    55.7   54.61   54.31    54.7
   57.09    59.8   61.81   64.61   67.91   67.21    64.2   64.21   64.22   66.12
   67.56   67.45   67.06   67.06    63.1   63.09    62.8   62.15   60.99    60.4
   60.21   59.71   57.81   56.92   56.29    54.2   54.03   53.83   55.01   53.94
   54.17   54.41   53.39    55.6    54.4      53    54.8    56.5    55.2    54.2
    55.6    56.2    55.1      56    57.3    57.4    56.4    58.7    61.1    60.8
   66.95   66.75   57.95   56.35   56.55   54.35   55.21   54.55   54.25   54.25
   54.25   54.76   61.75   64.55   67.85   67.15   60.79   59.13   59.41   59.41
   60.23    65.4   54.73   63.21   59.25   56.37   58.89   54.03   53.25   57.64
   53.55   54.35   54.35   53.05   54.05   53.21   52.35   53.25   54.95   53.65
   53.45   54.35   53.33   55.55   54.35   52.95   54.75   56.45   55.15   54.15
   55.55   56.15   55.05   55.95   57.25   57.35   56.35   58.65   61.05   60.75
Pier Skew, UpSta & Num, DnSta & Num=  ,4971.6, 2 ,4971.6, 2 , 0 , 0 , 0 ,,
     1.4     1.4
   43.92   62.99
     1.4     1.4
   43.87   62.94
Pier Skew, UpSta & Num, DnSta & Num=  ,5029.1, 2 ,5029.1, 2 , 0 , 0 , 0 ,,
     1.4     1.4
   43.18   61.68
     1.4     1.4
   43.13   61.63
Abutment Skew #Up #Dn= , 2 , 2
 4914.71 4937.01
   63.26   50.38
 4914.71 4937.01
   63.21   50.33
Abutment Skew #Up #Dn= , 2 , 2
 5058.81 5089.44
   50.49    59.3
 5058.81 5089.44
   50.44   59.25
BR Coef= 1 , 1 , 0 ,1.25, 0 ,,,.8,0,2,0,
WSPro=,,,, 1 ,,,, 0 ,,,, 0 ,,,,-1 ,-1 ,-1 , 0 , 0 , 0 , 0 , 0
BR U #Sta/Elev= 154
  3126.1      67  3156.1    67.6  3166.1    67.4  3176.1    66.8  3256.1      58
  3276.1    56.9  3296.1    56.4  3361.1   56.48  3441.1   56.58  3456.1    56.6
  3691.2   55.17    3693   55.16  3736.1    54.9  3751.2   54.52  3756.1    54.4
  3771.2   54.61  3784.7    54.8  3821.2    54.8  3844.7    54.8  3851.2   54.93
  3864.7    55.2  3901.2   54.38  3904.7    54.3  3991.2   55.26  3994.7    55.3
  4011.2   55.01  4034.7    54.6  4044.7    54.7  4201.2   54.52  4301.2   54.41
  4402.3    54.3  4443.2    54.3  4573.2    54.3  4593.2    54.3  4602.3    54.3
  4603.2   54.34  4612.3    54.7  4613.2   54.81  4622.3    55.9  4632.3    57.5
  4642.3    59.4  4652.3    61.8  4662.3    64.6  4672.3    66.5  4682.3    67.9
  4692.3    67.7  4702.3    67.2  4703.2   66.76  4713.2   61.88 4715.34   60.84
 4735.43   59.18 4756.89   59.46    4757   59.46 4757.11   59.46 4764.93   59.56
  4793.8   59.41 4804.69   59.35  4824.2   59.98 4833.66   60.28 4868.54   65.45
  4902.2   57.69 4914.82   54.78 4914.91   54.76  4927.7   51.81 4937.01   50.38
 4971.55   45.07 4976.16   44.06 4985.04   42.14 4987.12   38.61 4999.57    38.1
 5012.01   38.57 5015.05    41.6 5018.79   42.29 5029.06   44.32 5043.76   47.56
 5058.81   50.49 5089.24    56.4 5089.35   56.42 5102.31   58.94  5102.7   58.88
 5132.24   54.08 5165.47   54.35  5167.2   54.27 5188.01    53.3  5211.5    56.9
 5216.63   57.69  5224.2    53.6  5234.2    54.5 5243.79    54.4  5243.9    54.4
 5244.01    54.4  5244.2    54.4  5251.8   54.15  5284.2    53.1  5314.2    54.1
  5344.2    53.2  5412.6   53.26    5458    53.3    5478    53.1    5488    52.6
    5508    52.7    5518    52.4    5528    52.5    5538    52.9    5648    53.3
  5654.2    53.7  5664.2   54.13  5684.2      55  5704.2    54.7  5714.2    53.7
  5794.2    53.5  5804.2   53.95  5814.2    54.4  5824.2    54.3  5854.2   53.64
  5864.2   53.42  5874.2    53.2  5884.2   53.38  5904.2   53.73  5964.2    54.8
  5994.2    54.3  6074.2    54.9  6094.2    55.5  6104.2    55.6  6109.6   55.47
  6164.2    54.1  6174.2    54.4  6194.2      53  6204.2    53.2  6224.2    54.8
  6354.2    55.8  6374.2    56.5  6394.2      56  6574.2    55.2  6594.2    54.2
  6614.2    55.6  6754.2    55.6  6764.2    56.2  6934.2    55.5  6974.2    55.8
  6984.2    55.1  6994.2      56  7234.2    57.3  7314.2    56.7  7354.2    57.4
  7364.2    57.1  7374.2    56.4  7444.2    58.7  7604.2    60.6  7614.2    61.1
  7694.2    61.4  7704.2    60.9  7744.2    60.9    7749    60.8
BR U #Mann= 5
  3126.1     .99    3693     .12  4927.7     .04 5043.76     .12  6109.6      .2
BR U Banks=4927.7,5043.76
BR D #Sta/Elev= 154
  3126.1   66.95  3156.1   67.55  3166.1   67.35  3176.1   66.75  3256.1   57.95
  3276.1   56.85  3296.1   56.35  3361.1   56.43  3441.1   56.53  3456.1   56.55
  3691.2   55.12    3693   55.11  3736.1   54.85  3751.2   54.47  3756.1   54.35
  3771.2   54.56  3784.7   54.75  3821.2   54.75  3844.7   54.75  3851.2   54.88
  3864.7   55.15  3901.2   54.33  3904.7   54.25  3991.2   55.21  3994.7   55.25
  4011.2   54.96  4034.7   54.55  4044.7   54.65  4201.2   54.47  4301.2   54.36
  4402.3   54.25  4443.2   54.25  4573.2   54.25  4593.2   54.25  4602.3   54.25
  4603.2   54.29  4612.3   54.65  4613.2   54.76  4622.3   55.85  4632.3   57.45
  4642.3   59.35  4652.3   61.75  4662.3   64.55  4672.3   66.45  4682.3   67.85
  4692.3   67.65  4702.3   67.15  4703.2   66.71  4713.2   61.83 4715.34   60.79
 4735.43   59.13 4756.89   59.41    4757   59.41 4757.11   59.41 4764.93   59.51
  4793.8   59.36 4804.69    59.3  4824.2   59.93 4833.66   60.23 4868.54    65.4
  4902.2   57.64 4914.82   54.73 4914.91   54.71  4927.7   51.76 4937.01   50.33
 4971.55   45.02 4976.16   44.01 4985.04   42.09 4987.12   38.56 4999.57   38.05
 5012.01   38.52 5015.05   41.55 5018.79   42.24 5029.06   44.27 5043.76   47.51
 5058.81   50.44 5089.24   56.35 5089.35   56.37 5102.31   58.89  5102.7   58.83
 5132.24   54.03 5165.47    54.3  5167.2   54.22 5188.01   53.25  5211.5   56.85
 5216.63   57.64  5224.2   53.55  5234.2   54.45 5243.79   54.35  5243.9   54.35
 5244.01   54.35  5244.2   54.35  5251.8    54.1  5284.2   53.05  5314.2   54.05
  5344.2   53.15  5412.6   53.21    5458   53.25    5478   53.05    5488   52.55
    5508   52.65    5518   52.35    5528   52.45    5538   52.85    5648   53.25
  5654.2   53.65  5664.2   54.08  5684.2   54.95  5704.2   54.65  5714.2   53.65
  5794.2   53.45  5804.2    53.9  5814.2   54.35  5824.2   54.25  5854.2   53.59
  5864.2   53.37  5874.2   53.15  5884.2   53.33  5904.2   53.68  5964.2   54.75
  5994.2   54.25  6074.2   54.85  6094.2   55.45  6104.2   55.55  6109.6   55.42
  6164.2   54.05  6174.2   54.35  6194.2   52.95  6204.2   53.15  6224.2   54.75
  6354.2   55.75  6374.2   56.45  6394.2   55.95  6574.2   55.15  6594.2   54.15
  6614.2   55.55  6754.2   55.55  6764.2   56.15  6934.2   55.45  6974.2   55.75
  6984.2   55.05  6994.2   55.95  7234.2   57.25  7314.2   56.65  7354.2   57.35
  7364.2   57.05  7374.2   56.35  7444.2   58.65  7604.2   60.55  7614.2   61.05
  7694.2   61.35  7704.2   60.85  7744.2   60.85    7749   60.75
BR D #Mann= 5
  3126.1     .99    3693     .12  4927.7     .04 5043.76     .12  6109.6      .2
BR D Banks=4927.7,5043.76
BC Design=,, 0 ,, 0 ,,,,,,

Type RM Length L Ch R = 1 ,40886.8 ,39.9,39.9,39.9
BEGIN DESCRIPTION:
Downstream Section of Bridge/Culvert/Weir
END DESCRIPTION:
XS GIS Cut Line= 6
      3130675.65     13880812.95       3130421.7     13880082.19
      3130342.72     13879462.81      3130362.07     13879091.75
      3130352.19     13878824.97      3130210.63     13876242.49
#Sta/Elev= 30
  3126.1   67.12  3176.1   66.92  3256.1   58.12  3296.1   56.52    3693   55.28
  4602.3   54.42  4632.3   57.62  4682.3   68.02  4702.3   67.32 4715.34   60.96
 4735.43    59.3 4833.66    60.4 4868.54   65.57  4927.7   51.93 4987.12   38.73
 4999.57   38.22 5012.01   38.69 5015.05   41.72 5043.76   47.68 5102.31   59.06
 5132.24    54.2 5188.01   53.42 5216.63   57.81  5224.2   53.72    5518   52.52
  6109.6   55.59  6194.2   53.12  6374.2   56.62  6984.2   55.22    7749   60.92
#Mann= 5 , 1 , 0
  3126.1     .99       0    3693     .12       0  4927.7     .04       0
 5043.76     .12       0  6109.6      .2       0
#XS Ineff= 2 , 0
       0    3693      62    5963       0      62
Permanent Ineff=
       F       F
Bank Sta=4927.7,5043.76
XS Rating Curve= 0
Exp/Cntr=.5,.3

Type RM Length L Ch R = 1 ,40846.9 ,241.4,241.4,241.4
BEGIN DESCRIPTION:
Upstream Section of Bridge/Culvert/Weir
END DESCRIPTION:
XS GIS Cut Line= 6
       3130726.1     13880912.02      3130510.12     13880159.95
      3130385.42     13879519.15      3130385.42     13879163.14
      3130385.42     13878811.87      3130316.89     13876239.75
#Sta/Elev= 30
  3033.4   73.83  3126.1   66.83  3176.1   66.63  3256.1   57.83  3333.4   56.28
  4602.3   54.13  4632.3   57.33  4682.3   67.73  4762.3   65.53 4823.48   53.41
 4882.29    53.8 4946.41   50.14 4981.64   40.26 4995.48   38.89 5040.02   43.82
 5060.03   49.17 5089.09   56.13 5168.08    57.9 5205.23   54.15  5284.2   52.93
  5684.2   54.83  5911.4   53.69  6104.2   55.43  6194.2   52.83  6374.2   56.33
  6594.2   54.03  6764.2   56.03  7374.2   56.23  7614.2   60.93    7749   60.63
#Mann= 5 , 1 , 0
  3033.4     .99       0  3333.4     .12       0 4946.41     .04       0
 5060.03     .12       0  5911.4      .2       0
#XS Ineff= 2 , 0
       0    3790      74    5866       0      60
Permanent Ineff=
       F       F
Bank Sta=4946.41,5060.03
XS Rating Curve= 0
Exp/Cntr=.5,.3

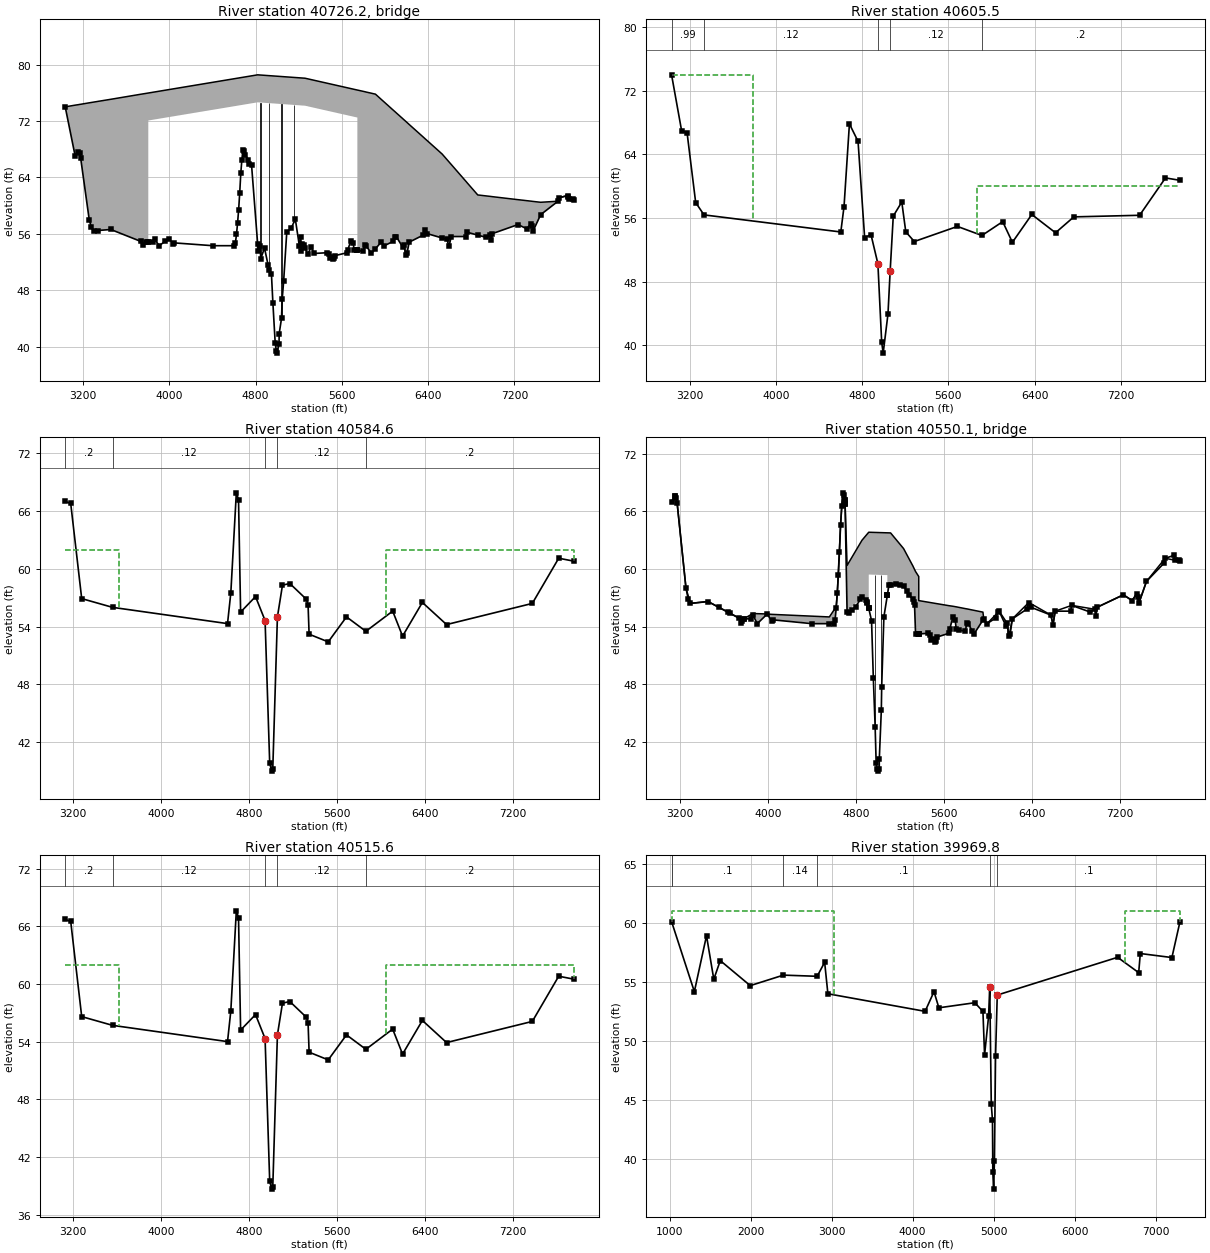
Type RM Length L Ch R = 3 ,40726.2 ,,,
BEGIN DESCRIPTION:
US HWY 59, SKEW ANGLE OF 30 DEGREES
Structure ID: P18-13
END DESCRIPTION:
Bridge Culvert--1,0,-1,-1, 0
Deck Dist Width WeirC Skew NumUp NumDn MinLoCord MaxHiCord MaxSubmerge Is_Ogee
10,221.4,2.6,0, 59, 59, , , .95, 0, 1,1,,
  3033.4  3126.1  3156.1  3166.1  3176.1  3256.1  3276.1  3296.1  3456.1  3736.1
  3756.1  3784.7 3804.21  3804.3  4818.8    5258 5743.74 5743.85  5794.2  5814.2
  5824.2  5874.2  5911.4  5964.2  5994.2  6074.2  6094.2  6104.2  6164.2  6174.2
  6194.2  6204.2  6224.2  6354.2  6374.2  6394.2  6530.4  6574.2  6594.2  6614.2
  6754.2  6764.2  6860.4  6934.2  6974.2  6984.2  6994.2  7234.2  7314.2  7354.2
  7364.2  7374.2  7444.2  7604.2  7614.2  7694.2  7704.2  7744.2    7749
      74   74.24   74.31   74.34   74.36   74.57   74.62   74.67   75.07   75.79
   75.84   75.91   75.96   75.96   78.54   78.06   76.38   76.38   76.21   76.14
    76.1   75.93    75.8   75.07   74.66   73.56   73.29   73.15   72.33   72.19
   71.92   71.78    71.5   69.72   69.44   69.17    67.3   66.53   66.18   65.83
   63.37   63.19    61.5   61.37    61.3   61.28   61.26   60.83   60.69   60.62
    60.6   60.58   60.46   60.61   61.11   61.41    60.9    60.9    60.8
      74      67    67.6    67.4    66.8      58    56.9    56.4    56.6    54.9
    54.4    54.8    54.8   72.06   74.64   74.16   72.48   53.63    53.5    54.4
    54.3    53.2   53.86    54.8    54.3    54.9    55.5    55.6    54.1    54.4
      53    53.2    54.8    55.8    56.5      56   55.39    55.2    54.2    55.6
    55.6    56.2    55.8    55.5    55.8    55.1      56    57.3    56.7    57.4
    57.1    56.4    58.7    60.6    61.1    61.4    60.9    60.9    60.8
  3033.4  3126.1  3156.1  3166.1  3176.1  3256.1  3276.1  3296.1  3456.1  3736.1
  3756.1  3784.7 3804.21  3804.3  4818.8    5258 5743.74 5743.85  5794.2  5814.2
  5824.2  5874.2  5911.4  5964.2  5994.2  6074.2  6094.2  6104.2  6164.2  6174.2
  6194.2  6204.2  6224.2  6354.2  6374.2  6394.2  6530.4  6574.2  6594.2  6614.2
  6754.2  6764.2  6860.4  6934.2  6974.2  6984.2  6994.2  7234.2  7314.2  7354.2
  7364.2  7374.2  7444.2  7604.2  7614.2  7694.2  7704.2  7744.2    7749
      74   74.24   74.31   74.34   74.36   74.57   74.62   74.67   75.07   75.79
   75.84   75.91   75.96   75.96   78.54   78.06   76.38   76.38   76.21   76.14
    76.1   75.93    75.8   75.07   74.66   73.56   73.29   73.15   72.33   72.19
   71.92   71.78    71.5   69.72   69.44   69.17    67.3   66.53   66.18   65.83
   63.37   63.19    61.5   61.37    61.3   61.28   61.26   60.83   60.69   60.62
    60.6   60.58   60.46   60.61   61.11   61.41    60.9    60.9    60.8
   73.94   66.94   67.54   67.34   66.74   57.94   56.84   56.34   56.54   54.84
   54.34   54.74   54.74      72   74.58    74.1   72.42   53.57   53.44   54.34
   54.24   53.14    53.8   54.74   54.24   54.84   55.44   55.54   54.04   54.34
   52.94   53.14   54.74   55.74   56.44   55.94   55.33   55.14   54.14   55.54
   55.54   56.14   55.74   55.44   55.74   55.04   55.94   57.24   56.64   57.34
   57.04   56.34   58.64   60.54   61.04   61.34   60.84   60.84   60.74
Pier Skew, UpSta & Num, DnSta & Num=  ,4846, 2 ,4846, 2 , 0 , 0 , 0 ,,
       4       4
    51.5   75.61
       4       4
   51.44   75.55
Pier Skew, UpSta & Num, DnSta & Num=  ,4922.7, 2 ,4922.7, 2 , 0 , 0 , 0 ,,
       4       4
   49.75   75.53
       4       4
   49.69   75.47
Pier Skew, UpSta & Num, DnSta & Num=  ,5039.9, 2 ,5039.9, 2 , 0 , 0 , 0 ,,
       4       4
   42.78    75.4
       4       4
   42.72   75.34
Pier Skew, UpSta & Num, DnSta & Num=  ,5156.2, 2 ,5156.2, 2 , 0 , 0 , 0 ,,
       4       4
    56.6   75.27
       4       4
   56.54   75.21
Abutment Skew #Up #Dn= , 2 , 2
  3804.1 3960.61
   72.06   54.92
  3804.1 3960.61
      72   54.86
BR Coef= 1 , 1 , 0 ,1.25, 0 ,,,.8,0,2,0,
WSPro=,,,, 1 ,,,, 0 ,,,, 0 ,,,,-1 ,-1 ,-1 , 0 , 0 , 0 , 0 , 0
BR U #Sta/Elev= 123
  3033.4      74  3126.1      67  3156.1    67.6  3166.1    67.4  3176.1    66.8
  3256.1      58  3276.1    56.9  3296.1    56.4  3333.4   56.45  3456.1    56.6
  3736.1    54.9  3756.1    54.4  3784.7    54.8 3804.21    54.8  3804.3    54.8
  3844.7    54.8  3864.7    55.2  3904.7    54.3 3960.61   54.92  3994.7    55.3
  4034.7    54.6  4044.7    54.7  4402.3    54.3  4602.3    54.3  4612.3    54.7
  4622.3    55.9  4632.3    57.5  4642.3    59.4  4652.3    61.8  4662.3    64.6
  4672.3    66.5  4682.3    67.9  4692.3    67.7  4702.3    67.2  4732.3    66.5
  4742.3    65.9  4762.3    65.7  4818.8   54.51 4823.48   53.58  4844.1   54.31
 4846.01   52.41 4882.29   53.97 4914.48   51.63 4922.66   50.79 4946.41   50.31
 4960.07   46.17 4981.64   40.43 4992.08   39.39 4995.48   39.06 5016.79    40.3
 5018.36   41.82 5040.02   43.99  5046.2   46.68 5060.03   49.34 5089.09    56.3
 5129.63   56.78 5168.08   58.07 5205.23   54.32 5219.15   55.49  5224.2    53.6
  5234.2    54.5  5244.2    54.4    5258   53.95  5284.2    53.1  5314.2    54.1
  5344.2    53.2    5458    53.3    5478    53.1    5488    52.6    5508    52.7
    5518    52.4    5528    52.5    5538    52.9    5648    53.3  5654.2    53.7
  5684.2      55  5704.2    54.7  5714.2    53.7 5743.24   53.63 5743.74   53.63
 5743.85   53.63  5794.2    53.5  5814.2    54.4  5824.2    54.3  5874.2    53.2
  5911.4   53.86  5964.2    54.8  5994.2    54.3  6074.2    54.9  6094.2    55.5
  6104.2    55.6  6164.2    54.1  6174.2    54.4  6194.2      53  6204.2    53.2
  6224.2    54.8  6354.2    55.8  6374.2    56.5  6394.2      56  6530.4   55.39
  6574.2    55.2  6594.2    54.2  6614.2    55.6  6754.2    55.6  6764.2    56.2
  6860.4    55.8  6934.2    55.5  6974.2    55.8  6984.2    55.1  6994.2      56
  7234.2    57.3  7314.2    56.7  7354.2    57.4  7364.2    57.1  7374.2    56.4
  7444.2    58.7  7604.2    60.6  7614.2    61.1  7694.2    61.4  7698.4   61.19
  7704.2    60.9  7744.2    60.9    7749    60.8
BR U #Mann= 5
  3033.4     .99  3333.4     .12 4946.41     .04 5060.03     .12  5911.4      .2
BR U Banks=4946.41,5060.03
BR D #Sta/Elev= 123
  3033.4   73.94  3126.1   66.94  3156.1   67.54  3166.1   67.34  3176.1   66.74
  3256.1   57.94  3276.1   56.84  3296.1   56.34  3333.4   56.39  3456.1   56.54
  3736.1   54.84  3756.1   54.34  3784.7   54.74 3804.21   54.74  3804.3   54.74
  3844.7   54.74  3864.7   55.14  3904.7   54.24 3960.61   54.86  3994.7   55.24
  4034.7   54.54  4044.7   54.64  4402.3   54.24  4602.3   54.24  4612.3   54.64
  4622.3   55.84  4632.3   57.44  4642.3   59.34  4652.3   61.74  4662.3   64.54
  4672.3   66.44  4682.3   67.84  4692.3   67.64  4702.3   67.14  4732.3   66.44
  4742.3   65.84  4762.3   65.64  4818.8   54.45 4823.48   53.52  4844.1   54.25
 4846.01   52.35 4882.29   53.91 4914.48   51.57 4922.66   50.73 4946.41   50.25
 4960.07   46.11 4981.64   40.37 4992.08   39.33 4995.48      39 5016.79   40.24
 5018.36   41.76 5040.02   43.93  5046.2   46.62 5060.03   49.28 5089.09   56.24
 5129.63   56.72 5168.08   58.01 5205.23   54.26 5219.15   55.43  5224.2   53.54
  5234.2   54.44  5244.2   54.34    5258   53.89  5284.2   53.04  5314.2   54.04
  5344.2   53.14    5458   53.24    5478   53.04    5488   52.54    5508   52.64
    5518   52.34    5528   52.44    5538   52.84    5648   53.24  5654.2   53.64
  5684.2   54.94  5704.2   54.64  5714.2   53.64 5743.24   53.57 5743.74   53.57
 5743.85   53.57  5794.2   53.44  5814.2   54.34  5824.2   54.24  5874.2   53.14
  5911.4    53.8  5964.2   54.74  5994.2   54.24  6074.2   54.84  6094.2   55.44
  6104.2   55.54  6164.2   54.04  6174.2   54.34  6194.2   52.94  6204.2   53.14
  6224.2   54.74  6354.2   55.74  6374.2   56.44  6394.2   55.94  6530.4   55.33
  6574.2   55.14  6594.2   54.14  6614.2   55.54  6754.2   55.54  6764.2   56.14
  6860.4   55.74  6934.2   55.44  6974.2   55.74  6984.2   55.04  6994.2   55.94
  7234.2   57.24  7314.2   56.64  7354.2   57.34  7364.2   57.04  7374.2   56.34
  7444.2   58.64  7604.2   60.54  7614.2   61.04  7694.2   61.34  7698.4   61.13
  7704.2   60.84  7744.2   60.84    7749   60.74
BR D #Mann= 5
  3033.4     .99  3333.4     .12 4946.41     .04 5060.03     .12  5911.4      .2
BR D Banks=4946.41,5060.03
BC Design=,, 0 ,, 0 ,,,,,,

Type RM Length L Ch R = 1 ,40605.5 ,20.9,20.9,20.9
BEGIN DESCRIPTION:
Downstream Section of Bridge/Culvert/Weir
END DESCRIPTION:
XS GIS Cut Line= 6
      3130926.28     13880777.11       3130710.3     13880025.03
       3130585.6     13879384.23       3130585.6     13879028.22
       3130585.6     13878676.95      3130517.08     13876104.84
#Sta/Elev= 30
  3033.4   73.93  3126.1   66.93  3176.1   66.73  3256.1   57.93  3333.4   56.38
  4602.3   54.23  4632.3   57.43  4682.3   67.83  4762.3   65.63 4823.48   53.51
 4882.29    53.9 4946.41   50.24 4981.64   40.36 4995.48   38.99 5040.02   43.92
 5060.03   49.27 5089.09   56.23 5168.08      58 5205.23   54.25  5284.2   53.03
  5684.2   54.93  5911.4   53.79  6104.2   55.53  6194.2   52.93  6374.2   56.43
  6594.2   54.13  6764.2   56.13  7374.2   56.33  7614.2   61.03    7749   60.73
#Mann= 5 , 1 , 0
  3033.4     .99       0  3333.4     .12       0 4946.41     .04       0
 5060.03     .12       0  5911.4      .2       0
#XS Ineff= 2 , 0
       0    3790      74    5866       0      60
Permanent Ineff=
       F       F
Bank Sta=4946.41,5060.03
XS Rating Curve= 0
Exp/Cntr=.5,.3

Type RM Length L Ch R = 1 ,40584.6 ,69,69,69
BEGIN DESCRIPTION:
Upstream Section of Bridge/Culvert/Weir
END DESCRIPTION:
XS GIS Cut Line= 6
      3130906.57     13880676.68      3130759.94     13880068.78
      3130618.45     13879272.62      3130623.39     13878877.39
      3130611.53     13877465.38      3130616.01     13876083.79
#Sta/Elev= 30
  3126.1   67.01  3176.1   66.81  3276.1   56.91  3556.8      56  4602.3   54.31
  4632.3   57.51  4682.3   67.91  4702.3   67.21 4721.34   55.51 4856.97   57.12
  4943.8   54.63 4985.65   39.86 5002.35   38.97 5013.83   39.19 5056.03   55.01
 5102.05   58.31 5168.87   58.48 5320.33   56.83 5334.86   56.23  5344.2   53.21
    5518   52.41  5684.2   55.01  5860.6   53.51  6104.2   55.61  6194.2   53.01
  6374.2   56.51  6594.2   54.21  7374.2   56.41  7614.2   61.11    7749   60.81
#Mann= 5 , 1 , 0
  3126.1      .2       0  3556.8     .12       0  4943.8     .04       0
 5056.03     .12       0  5860.6      .2       0
#XS Ineff= 2 , 0
       0    3614      62    6042       0      62
Permanent Ineff=
       F       F
Bank Sta=4943.8,5056.03
XS Rating Curve= 0
Exp/Cntr=.5,.3

Type RM Length L Ch R = 3 ,40550.1 ,,,
BEGIN DESCRIPTION:
ACCESS ROAD FOR US HWY 59 NORTH, SKEW ANGLE OF 30 DEGREES
Structure ID: P18-12
END DESCRIPTION:
Bridge Culvert--1,0,-1,-1, 0
Deck Dist Width WeirC Skew NumUp NumDn MinLoCord MaxHiCord MaxSubmerge Is_Ogee
10,49,2.6,0, 60, 60, , , .95, 0, 1,1,,
  3126.1  3156.1  3176.1  3256.1  3296.1  3456.1  3766.8  3864.7  3904.7  3994.7
  4034.7  4560.1  4602.3  4622.3  4632.3  4662.3  4682.3  4702.3 4721.34 4856.97
  4918.3 4918.39  5087.5 5087.61    5117 5235.25 5320.33 5334.86  5344.2  5373.2
 5373.31    5518    5648  5684.2  5714.2  5794.2  5814.2  5874.2  5956.8  5964.2
  5994.2  6104.2  6174.2  6194.2  6224.2  6374.2  6574.2  6594.2  6614.2  6764.2
  6974.2  6984.2  6994.2  7234.2  7314.2  7354.2  7374.2  7444.2  7614.2    7749
      67    67.6   66.81   58.01   56.41   56.61    54.7   55.36   55.34   55.31
   55.27      55   55.72   56.06   57.51   64.61   67.91   67.21   60.36   62.98
   63.81   63.81   63.75   63.75   63.74   62.11   60.29   59.94   59.72    59.2
    56.7   56.42   56.17   56.11   56.05   55.87   55.83   55.69    55.5    54.8
    54.3    55.6    54.4      53    54.8    56.5    55.2    54.2    55.6    56.2
    55.8    55.1      56    57.3    56.7    57.4    56.4    58.7    61.1    60.8
      67    67.6    66.8      58    56.4    56.6   54.55    55.2    54.3    55.3
    54.6    54.3    54.3    55.9    57.5    64.6    67.9    67.2    55.5   57.11
    55.9   59.41   59.35   57.26   58.34   58.22   56.82   56.22    53.2   53.23
   53.23    52.4    53.3      55    53.7    53.5    54.4    53.2   54.67    54.8
    54.3    55.6    54.4      53    54.8    56.5    55.2    54.2    55.6    56.2
    55.8    55.1      56    57.3    56.7    57.4    56.4    58.7    61.1    60.8
  3126.1  3156.1  3176.1  3256.1  3296.1  3456.1  3766.8  3864.7  3904.7  3994.7
  4034.7  4560.1  4602.3  4622.3  4632.3  4662.3  4682.3  4702.3 4721.34 4856.97
  4918.3 4918.39  5087.5 5087.61    5117 5235.25 5320.33 5334.86  5344.2  5373.2
 5373.31    5518    5648  5684.2  5714.2  5794.2  5814.2  5874.2  5956.8  5964.2
  5994.2  6104.2  6174.2  6194.2  6224.2  6374.2  6574.2  6594.2  6614.2  6764.2
  6974.2  6984.2  6994.2  7234.2  7314.2  7354.2  7374.2  7444.2  7614.2    7749
      67    67.6   66.81   58.01   56.41   56.61    54.7   55.36   55.34   55.31
   55.27      55   55.72   56.06   57.51   64.61   67.91   67.21   60.36   62.98
   63.81   63.81   63.75   63.75   63.74   62.11   60.29   59.94   59.72    59.2
    56.7   56.42   56.17   56.11   56.05   55.87   55.83   55.69    55.5    54.8
    54.3    55.6    54.4      53    54.8    56.5    55.2    54.2    55.6    56.2
    55.8    55.1      56    57.3    56.7    57.4    56.4    58.7    61.1    60.8
   66.73   67.33   66.53   57.73   56.13   56.33   54.28   54.93   54.03   55.03
   54.33   54.03   54.03   55.63   57.23   64.33   67.63   66.93   55.23   56.84
   55.63   59.14   59.08   56.99   58.07   57.95   56.55   55.95   52.93   52.96
   52.96   52.13   53.03   54.73   53.43   53.23   54.13   52.93    54.4   54.53
   54.03   55.33   54.13   52.73   54.53   56.23   54.93   53.93   55.33   55.93
   55.53   54.83   55.73   57.03   56.43   57.13   56.13   58.43   60.83   60.53
Pier Skew, UpSta & Num, DnSta & Num=  ,4976.4, 2 ,4976.4, 2 , 0 , 0 , 0 ,,
     1.4     1.4
   42.31   60.39
     1.4     1.4
   42.04   60.12
Pier Skew, UpSta & Num, DnSta & Num=  ,5032.8, 2 ,5032.8, 2 , 0 , 0 , 0 ,,
     1.4     1.4
   44.13   60.37
     1.4     1.4
   43.86    60.1
BR Coef= 1 , 1 , 0 ,1.25, 0 ,,,.8,0,2,0,
WSPro=,,,, 1 ,,,, 0 ,,,, 0 ,,,,-1 ,-1 ,-1 , 0 , 0 , 0 , 0 , 0
BR U #Sta/Elev= 134
  3126.1      67  3156.1    67.6  3156.8   67.59  3166.1    67.4  3176.1    66.8
  3256.1      58  3276.1    56.9  3296.1    56.4  3456.1    56.6  3556.8   55.99
  3636.8    55.5  3656.8   55.38  3736.1    54.9  3756.1    54.4  3766.8   54.55
  3784.7    54.8  3786.8    54.8  3844.7    54.8  3864.7    55.2  3904.7    54.3
  3994.7    55.3  4034.7    54.6  4044.7    54.7  4402.3    54.3  4560.1    54.3
  4602.3    54.3  4612.3    54.7  4622.3    55.9  4632.3    57.5  4642.3    59.4
  4652.3    61.8  4662.3    64.6  4672.3    66.5  4682.3    67.9  4692.3    67.7
  4702.1   67.21  4702.3    67.2 4702.89   66.84    4703   66.77 4703.11    66.7
 4721.34    55.5 4738.65    55.4  4766.7    55.7  4800.6   56.07    4842   56.83
 4856.97   57.11  4890.5   56.71 4905.87   56.52  4906.2    56.5  4918.3    55.9
 4918.39   55.89 4918.48   55.89  4943.8   54.62 4960.07   48.63 4976.42    43.6
 4985.65   39.85  4990.6   39.22 5002.35   38.96 5013.83   39.18 5014.35   40.21
  5032.8   45.32 5036.02   47.76 5056.03      55 5087.42   57.25  5087.5   57.26
 5087.61   57.26 5102.05    58.3    5117   58.34 5168.87   58.47  5200.5   58.35
 5235.25   58.22  5264.9   57.67 5283.62   57.33 5320.33   56.82    5327   56.54
 5334.86   56.22  5344.2    53.2  5365.6   53.22 5373.09   53.23  5373.2   53.23
 5373.31   53.23    5458    53.3    5478    53.1    5488    52.6    5508    52.7
    5518    52.4    5528    52.5    5538    52.9    5648    53.3  5654.2    53.7
  5684.2      55  5704.2    54.7  5714.2    53.7  5739.5   53.64  5794.2    53.5
  5814.2    54.4  5824.2    54.3  5860.6    53.5  5874.2    53.2  5956.8   54.67
  5964.2    54.8  5994.2    54.3  6074.2    54.9  6094.2    55.5  6104.2    55.6
  6164.2    54.1  6174.2    54.4  6194.2      53  6204.2    53.2  6224.2    54.8
  6354.2    55.8  6374.2    56.5  6394.2      56  6574.2    55.2  6594.2    54.2
  6614.2    55.6  6754.2    55.6  6764.2    56.2  6934.2    55.5  6974.2    55.8
  6984.2    55.1  6994.2      56  7234.2    57.3  7314.2    56.7  7354.2    57.4
  7364.2    57.1  7374.2    56.4  7444.2    58.7  7604.2    60.6  7614.2    61.1
  7694.2    61.4  7704.2    60.9  7744.2    60.9    7749    60.8
BR U #Mann= 5
  3126.1      .2  3556.8     .12  4943.8     .04 5056.03     .12  5860.6      .2
BR U Banks=4943.8,5056.03
BR D #Sta/Elev= 134
  3126.1   66.73  3156.1   67.33  3156.8   67.32  3166.1   67.13  3176.1   66.53
  3256.1   57.73  3276.1   56.63  3296.1   56.13  3456.1   56.33  3556.8   55.72
  3636.8   55.23  3656.8   55.11  3736.1   54.63  3756.1   54.13  3766.8   54.28
  3784.7   54.53  3786.8   54.53  3844.7   54.53  3864.7   54.93  3904.7   54.03
  3994.7   55.03  4034.7   54.33  4044.7   54.43  4402.3   54.03  4560.1   54.03
  4602.3   54.03  4612.3   54.43  4622.3   55.63  4632.3   57.23  4642.3   59.13
  4652.3   61.53  4662.3   64.33  4672.3   66.23  4682.3   67.63  4692.3   67.43
  4702.1   66.94  4702.3   66.93 4702.89   66.57    4703    66.5 4703.11   66.43
 4721.34   55.23 4738.65   55.13  4766.7   55.43  4800.6    55.8    4842   56.56
 4856.97   56.84  4890.5   56.44 4905.87   56.25  4906.2   56.23  4918.3   55.63
 4918.39   55.62 4918.48   55.62  4943.8   54.35 4960.07   48.36 4976.42   43.33
 4985.65   39.58  4990.6   38.95 5002.35   38.69 5013.83   38.91 5014.35   39.94
  5032.8   45.05 5036.02   47.49 5056.03   54.73 5087.42   56.98  5087.5   56.99
 5087.61   56.99 5102.05   58.03    5117   58.07 5168.87    58.2  5200.5   58.08
 5235.25   57.95  5264.9    57.4 5283.62   57.06 5320.33   56.55    5327   56.27
 5334.86   55.95  5344.2   52.93  5365.6   52.95 5373.09   52.96  5373.2   52.96
 5373.31   52.96    5458   53.03    5478   52.83    5488   52.33    5508   52.43
    5518   52.13    5528   52.23    5538   52.63    5648   53.03  5654.2   53.43
  5684.2   54.73  5704.2   54.43  5714.2   53.43  5739.5   53.37  5794.2   53.23
  5814.2   54.13  5824.2   54.03  5860.6   53.23  5874.2   52.93  5956.8    54.4
  5964.2   54.53  5994.2   54.03  6074.2   54.63  6094.2   55.23  6104.2   55.33
  6164.2   53.83  6174.2   54.13  6194.2   52.73  6204.2   52.93  6224.2   54.53
  6354.2   55.53  6374.2   56.23  6394.2   55.73  6574.2   54.93  6594.2   53.93
  6614.2   55.33  6754.2   55.33  6764.2   55.93  6934.2   55.23  6974.2   55.53
  6984.2   54.83  6994.2   55.73  7234.2   57.03  7314.2   56.43  7354.2   57.13
  7364.2   56.83  7374.2   56.13  7444.2   58.43  7604.2   60.33  7614.2   60.83
  7694.2   61.13  7704.2   60.63  7744.2   60.63    7749   60.53
BR D #Mann= 5
  3126.1      .2  3556.8     .12  4943.8     .04 5056.03     .12  5860.6      .2
BR D Banks=4943.8,5056.03
BC Design=,, 0 ,, 0 ,,,,,,

Type RM Length L Ch R = 1 ,40515.6 ,545.8,545.8,545.8
BEGIN DESCRIPTION:
Downstream Section of Bridge/Culvert/Weir
END DESCRIPTION:
XS GIS Cut Line= 6
      3130968.45     13880646.16      3130821.82     13880038.26
      3130680.33      13879242.1      3130685.27     13878846.87
      3130673.41     13877434.86      3130677.89     13876053.26
#Sta/Elev= 30
  3126.1   66.71  3176.1   66.51  3276.1   56.61  3556.8    55.7  4602.3   54.01
  4632.3   57.21  4682.3   67.61  4702.3   66.91 4721.34   55.21 4856.97   56.82
  4943.8   54.33 4985.65   39.56 5002.35   38.67 5013.83   38.89 5056.03   54.71
 5102.05   58.01 5168.87   58.18 5320.33   56.53 5334.86   55.93  5344.2   52.91
    5518   52.11  5684.2   54.71  5860.6   53.21  6104.2   55.31  6194.2   52.71
  6374.2   56.21  6594.2   53.91  7374.2   56.11  7614.2   60.81    7749   60.51
#Mann= 5 , 1 , 0
  3126.1      .2       0  3556.8     .12       0  4943.8     .04       0
 5056.03     .12       0  5860.6      .2       0
#XS Ineff= 2 , 0
       0    3614      62    6042       0      62
Permanent Ineff=
       F       F
Bank Sta=4943.8,5056.03
XS Rating Curve= 0
Exp/Cntr=.5,.3

Type RM Length L Ch R = 1 ,39969.8 ,831.3,781.2,449.8
BEGIN DESCRIPTION:
Cross Section 39969.8-Interpolated
END DESCRIPTION:
XS GIS Cut Line= 6
      3131927.43     13882685.47      3131428.98     13881680.75
      3131271.88      13881032.7      3131028.12     13879245.13
      3131312.51     13878473.22      3131280.46     13876613.53
#Sta/Elev= 30
    1026   60.06    1306   54.15    1456   58.89    1546    55.2    1626   56.78
    1996   54.66  2405.5   55.55    2822   55.45  2914.4   56.64  2954.4   53.97
  4154.4   52.48  4264.4   54.15  4324.4   52.78  4768.5   53.21  4868.5   52.47
  4888.5   48.78  4938.5   52.08  4952.4   54.55  4971.4   44.59  4986.2   43.26
  4990.5   38.84  5000.4   37.41  5010.5   39.82    5024   48.66  5045.2   53.86
  6531.1   57.06  6791.1   55.76  6811.1   57.38  7201.1   57.04  7301.1   60.09
#Mann= 6 , 1 , 0
    1026      .2       0    1026      .1       0  2405.5     .14       0
    2822      .1       0  4952.4    .045       0  5045.2      .1       0
#XS Ineff= 2 , 0
       0    3034      61    6622       0      61
Permanent Ineff=
       F       F
Bank Sta=4952.4,5045.2
XS Rating Curve= 0
Exp/Cntr=.3,.1