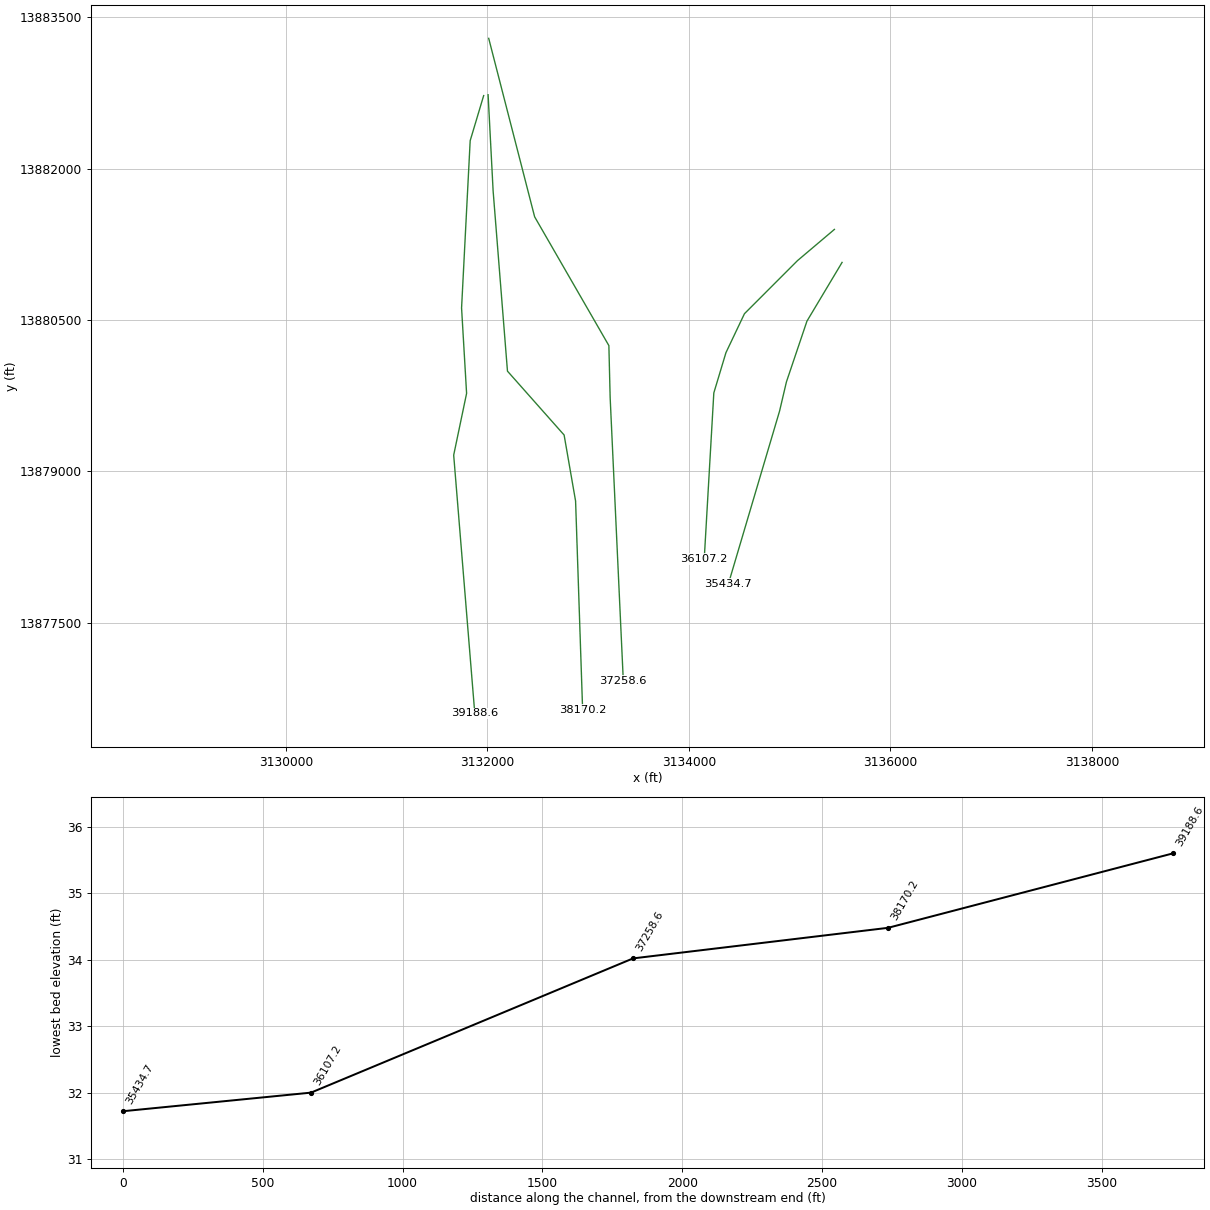
HEC-RAS study P118-00-00.PRJ: P118-00-00

--- P118-00-00.g01 (geometry) --- (continued)

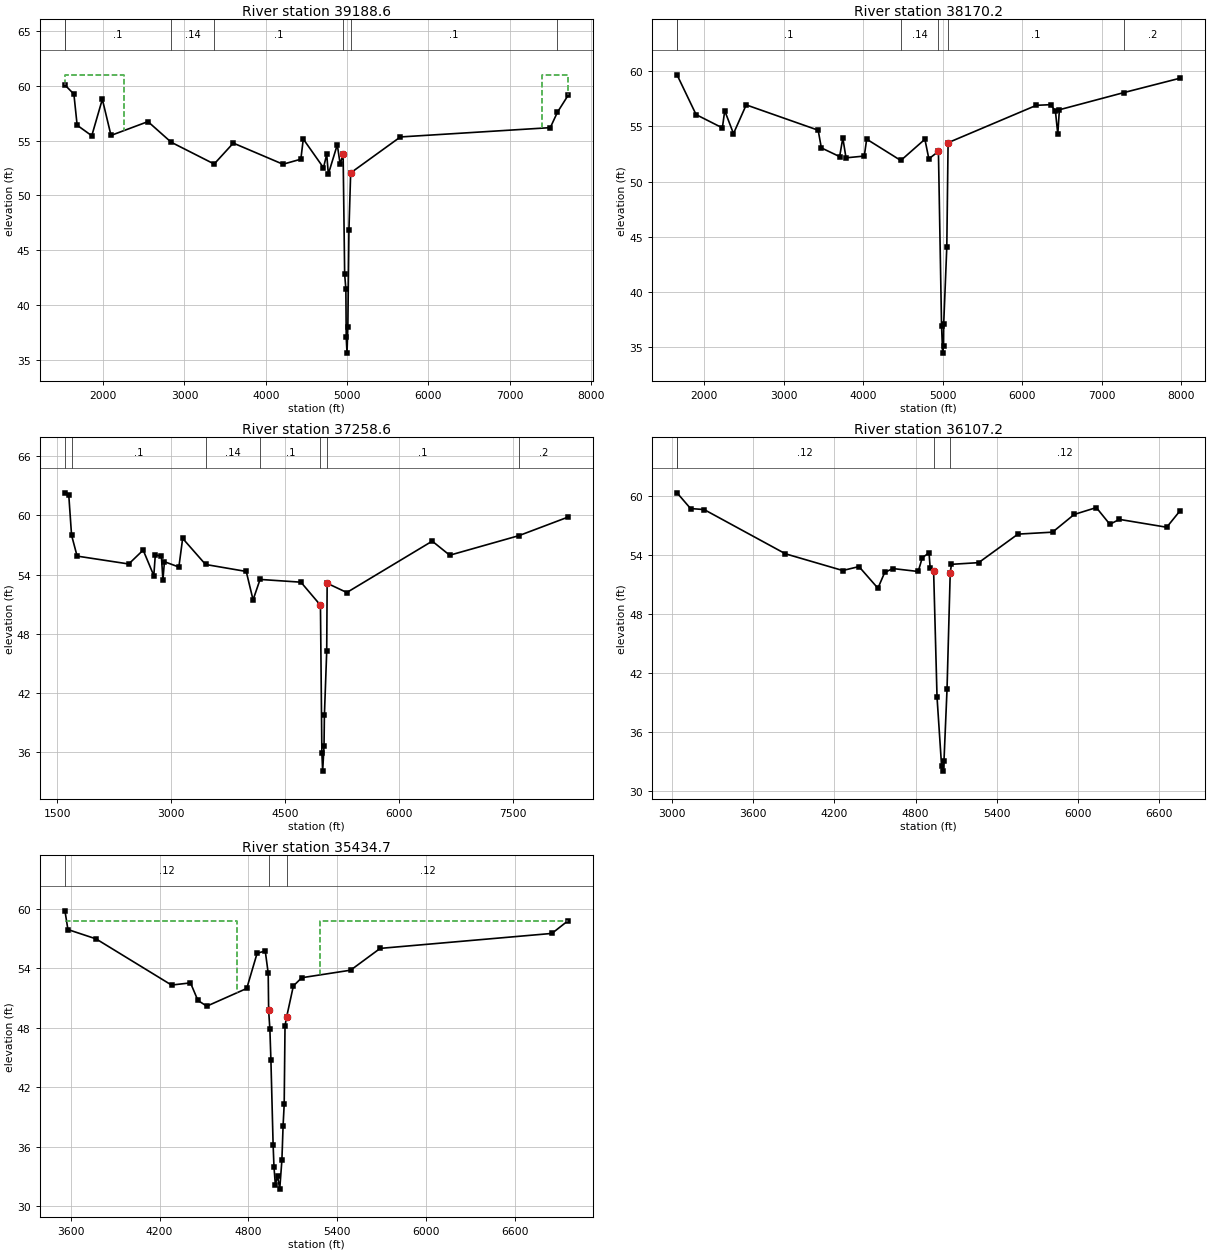
Type RM Length L Ch R = 1 ,39188.6 ,419.1,1018.4,1273
BEGIN DESCRIPTION:
Cross Section 39188.6
END DESCRIPTION:
XS GIS Cut Line= 6
      3131962.43     13882724.36      3131828.56     13882277.28
      3131743.16     13880619.11      3131792.98     13879772.24
      3131664.88     13879160.21      3131874.28     13876599.96
#Sta/Elev= 30
  1529.7   60.07  1639.7   59.24  1679.7    56.4  1859.7   55.44  1989.7   58.77
  2096.4   55.47  2551.3   56.73  2836.6   54.85  3365.8   52.86  3601.3   54.77
  4212.2   52.84  4432.2    53.3  4462.2   55.14  4710.6   52.52  4750.6   53.74
  4770.6   51.94  4880.6   54.62  4915.5   52.87  4952.4   53.74  4971.4   42.78
  4986.2   41.45  4990.5   37.03  5000.4    35.6  5010.5   38.01    5024   46.85
  5045.2   52.05    5657   55.33  7501.6   56.18  7589.6   57.59  7721.6   59.14
#Mann= 7 , 1 , 0
  1529.7      .2       0  1529.7      .1       0  2836.6     .14       0
  3365.8      .1       0  4952.4    .045       0  5045.2      .1       0
  7589.6      .2       0
#XS Ineff= 2 , 0
       0    2253      61    7403       0      61
Permanent Ineff=
       F       F
Bank Sta=4952.4,5045.2
XS Rating Curve= 0
Exp/Cntr=.3,.1

Type RM Length L Ch R = 1 ,38170.2 ,947.2,911.6,734.4
BEGIN DESCRIPTION:
Cross Section 38170.2
END DESCRIPTION:
XS GIS Cut Line= 6
      3132006.47     13882732.74      3132056.29     13881779.12
      3132198.62     13879992.85      3132760.83     13879359.47
       3132874.7     13878704.75      3132944.49     13876635.97
#Sta/Elev= 30
    1660   59.66    1900   56.06    2230   54.86    2260   56.41    2370   54.34
    2530   56.94  3434.9   54.65  3474.9   53.05  3704.9   52.26  3744.9   53.95
  3784.9   52.15  4014.9   52.31  4044.9   53.84  4474.1   51.91  4776.9   53.83
  4826.9   52.06  4947.2   52.73  4986.5   36.97    5000   34.48  5011.5   35.08
  5013.5   37.11  5052.5   44.09  5068.8   53.52  6178.3    56.9  6358.3   56.96
  6418.3   56.38  6448.3   54.29  6468.3    56.5  7282.9   58.06  7988.3   59.36
#Mann= 6 , 1 , 0
    1660      .2       0    1660      .1       0  4474.1     .14       0
  4947.2    .045       0  5068.8      .1       0  7282.9      .2       0
Bank Sta=4947.2,5068.8
XS Rating Curve= 0
Exp/Cntr=.3,.1

Type RM Length L Ch R = 1 ,37258.6 ,1553.9,1151.4,1054.3
BEGIN DESCRIPTION:
Cross Section 37258.6
END DESCRIPTION:
XS GIS Cut Line= 5
      3132012.38     13883292.01      3132468.22     13881522.71
      3133205.06     13880245.86      3133217.72     13879730.96
      3133348.24       13876924.
#Sta/Elev= 30
  1603.5    62.3  1653.5    62.1  1690.5      58  1763.5   55.87  2443.5   55.07
  2633.5   56.48  2773.5   53.89  2793.5   56.01  2873.5   55.83  2893.5   53.47
  2913.5    55.3  3103.5   54.76  3153.5   57.67  3454.9   55.02  3990.6   54.31
  4080.6   51.42  4172.6    53.5  4710.6   53.22  4967.8   50.88  4986.6   35.82
    4997   34.02  5014.8   36.55  5019.7   39.68  5050.2   46.19  5056.1   53.11
  5314.8   52.17  6439.8   57.39  6669.8   55.96  7581.4   57.95  8229.8   59.84
#Mann= 7 , 1 , 0
  1603.5      .2       0  1690.5      .1       0  3454.9     .14       0
  4172.6      .1       0  4967.8    .045       0  5056.1      .1       0
  7581.4      .2       0
Bank Sta=4967.8,5056.1
XS Rating Curve= 0
Exp/Cntr=.3,.1

Type RM Length L Ch R = 1 ,36107.2 ,674,672.5,661.7
BEGIN DESCRIPTION:
Cross Section 36107.2
END DESCRIPTION:
XS GIS Cut Line= 6
      3135443.26     13881397.76      3135076.03     13881087.51
       3134550.5     13880561.98      3134366.89     13880175.75
      3134246.58     13879776.86      3134151.46     13878130.57
#Sta/Elev= 30
  3037.2    60.3  3137.2    58.7  3237.2    58.6  3837.9    54.1  4261.2    52.4
  4381.2    52.8  4521.2    50.6  4571.2    52.2  4631.2    52.6  4818.8    52.3
  4848.8    53.7  4898.8    54.2 4907.46   52.61 4932.76   52.31 4957.96    39.5
 4991.66   32.49 4999.96      32 5009.06   32.99 5031.66   40.31 5055.36   52.19
 5064.66   53.03  5265.4    53.2  5555.4    56.1    5811    56.3    5971    58.1
  6134.6    58.8  6234.6    57.1  6304.6    57.6  6654.6    56.8  6754.6    58.5
#Mann= 4 , 1 , 0
  3037.2      .2       0  3037.2     .12       0 4932.76    .045       0
 5055.36     .12       0
Bank Sta=4932.76,5055.36
XS Rating Curve= 0
Exp/Cntr=.3,.1

Type RM Length L Ch R = 1 ,35434.7 ,391.1,389,362.5
BEGIN DESCRIPTION:
Cross Section 35434.7-Interpolated
END DESCRIPTION:
XS GIS Cut Line= 5
       3135519.4     13881070.71      3135170.78     13880488.42
      3134967.13     13879885.96      3134899.25     13879597.46
      3134390.77     13877882.77
#Sta/Elev= 30
  3561.2    59.8  3581.2   57.91  3771.2   56.97  4281.2   52.31  4409.3   52.53
  4459.3   50.76  4519.3   50.18  4789.3   51.97  4859.3   55.52  4914.2   55.75
  4934.2   53.52  4937.2   49.76  4945.5   47.87  4952.5   44.76  4967.4   36.21
  4973.2   33.98  4982.4   32.18  4997.4   33.04  5012.1   31.72  5026.8   34.66
  5034.8   38.12  5042.2   40.26  5047.9   48.22  5059.3   49.13  5104.2   52.22
  5160.7   53.05  5490.7   53.81  5690.7   56.01  6850.7   57.52  6960.7   58.81
#Mann= 3 , 1 , 0
  3561.2     .12       0  4937.2    .045       0  5059.3     .12       0
#XS Ineff= 2 , 0
       0    4721    58.8    5287       0    58.8
Permanent Ineff=
       F       F
Bank Sta=4937.2,5059.3
XS Rating Curve= 0
Exp/Cntr=.5,.3