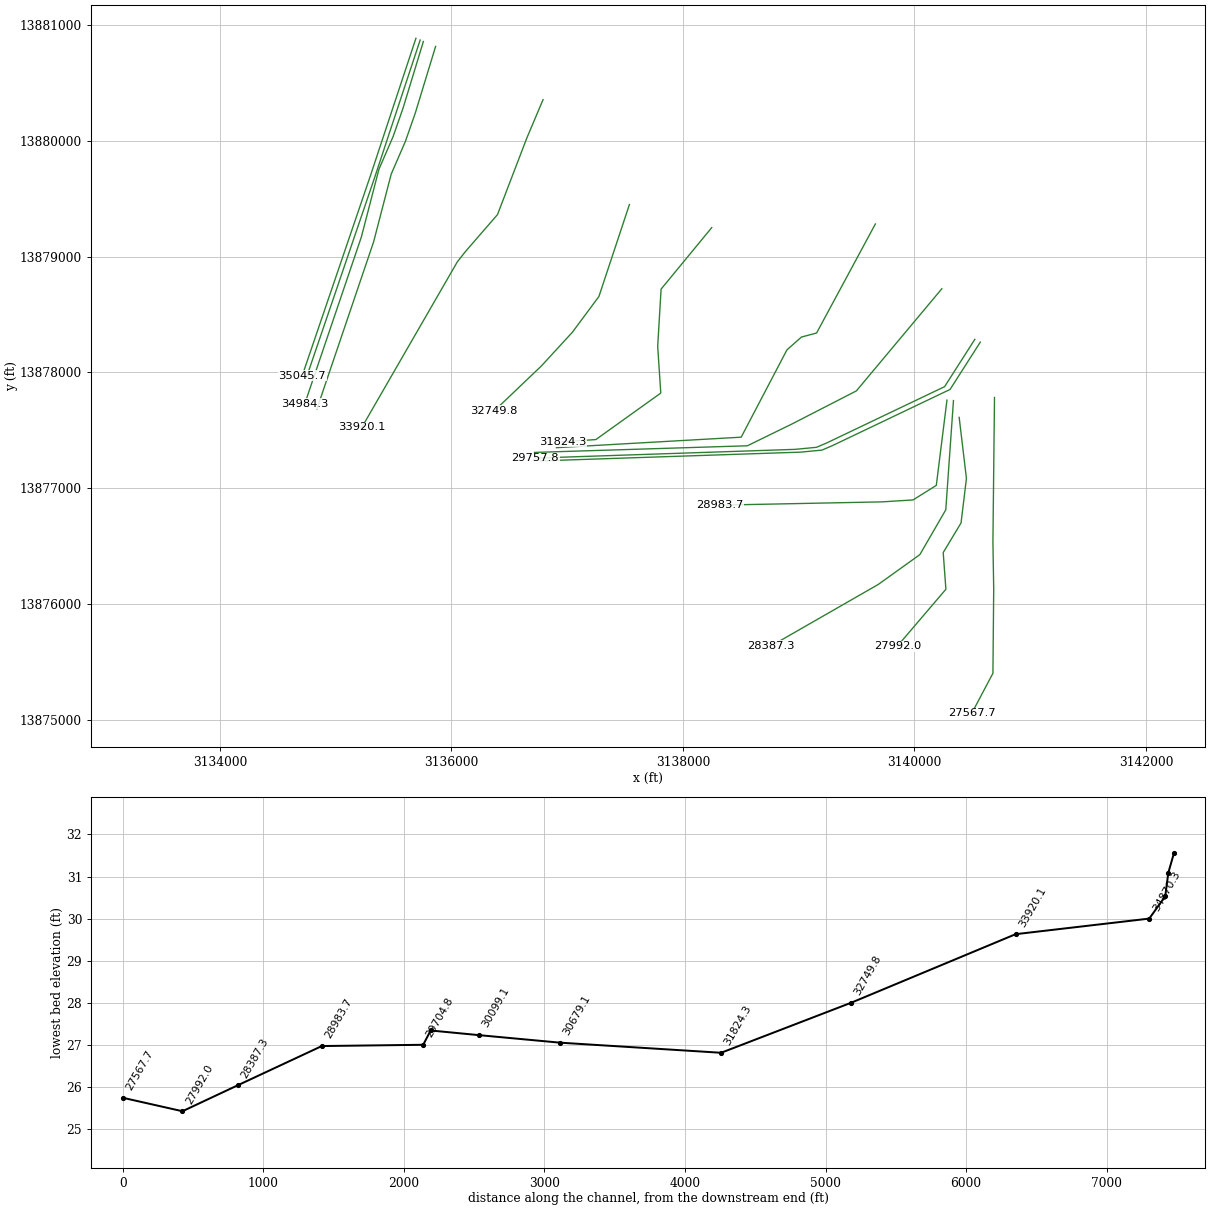
HEC-RAS study P118-00-00.PRJ: P118-00-00

--- P118-00-00.g01 (geometry) --- (continued)

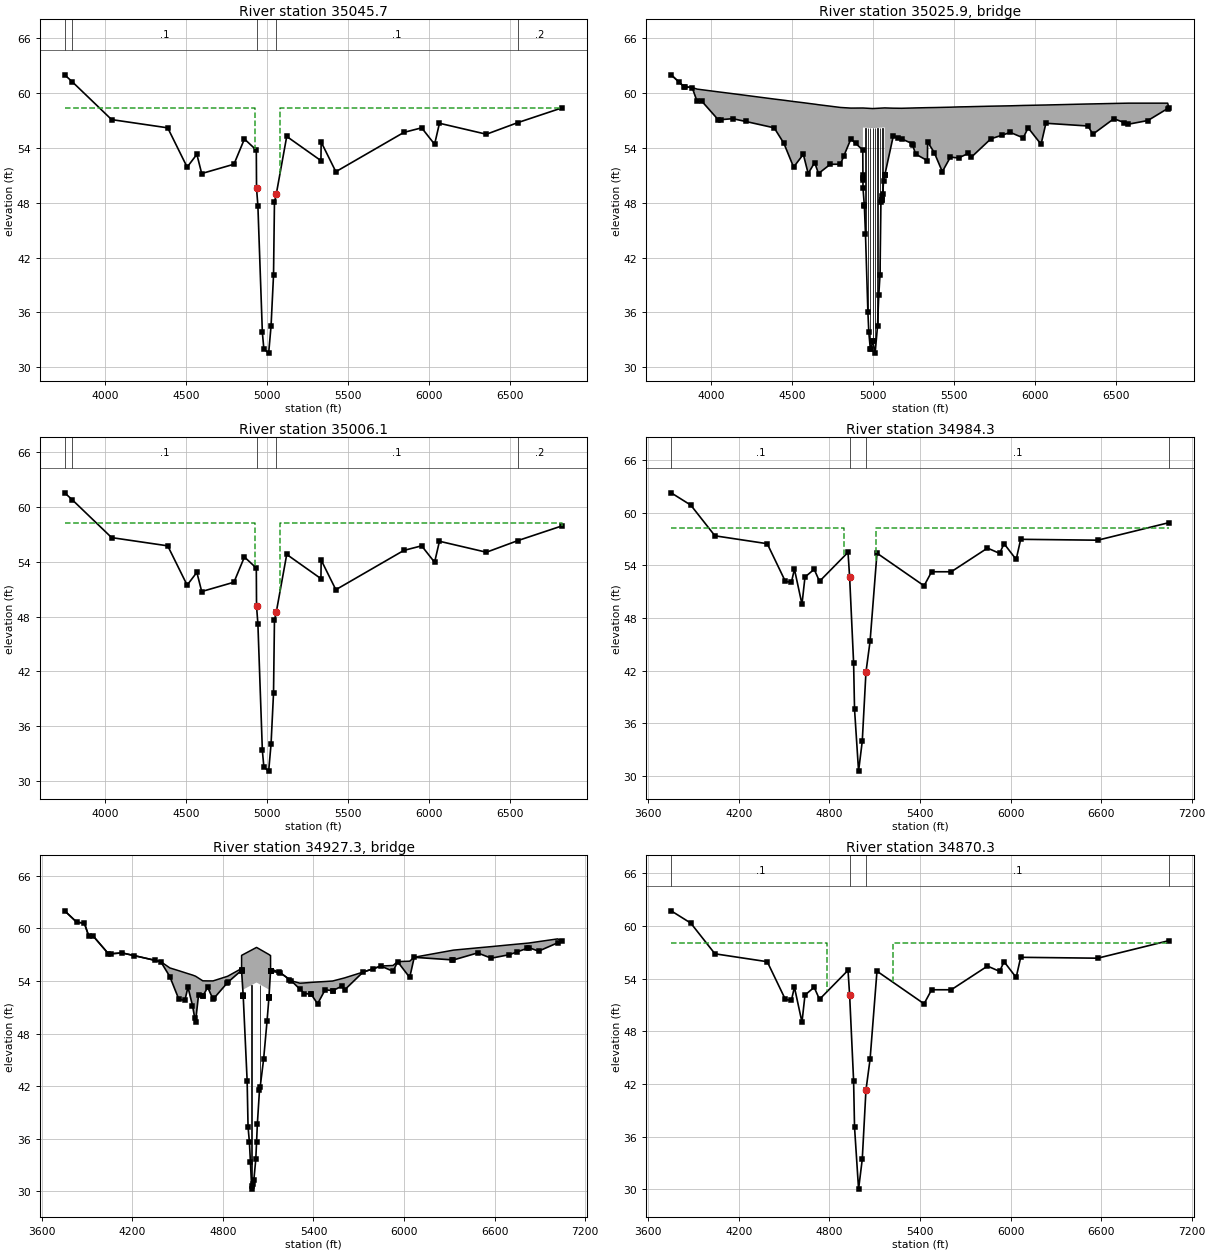
Type RM Length L Ch R = 1 ,35045.7 ,39.6,39.6,39.6
BEGIN DESCRIPTION:
Upstream Section of Bridge/Culvert/Weir
END DESCRIPTION:
XS GIS Cut Line= 3
      3135693.39     13880886.41      3135300.33     13879699.38
      3134711.25      13877972.3
#Sta/Elev= 30
    3752      62  3799.3   61.23    4042    57.1  4388.5    56.2  4508.5    51.9
  4568.5    53.3  4598.5    51.2  4797.8   52.22  4862.3   54.98  4935.8   53.77
  4937.2   49.59  4945.5    47.7  4973.2   33.81  4982.4   32.01  5012.1   31.55
  5026.8   34.49  5042.2   40.09  5047.9   48.05  5059.3   48.96  5123.7   55.26
  5335.1   52.61  5336.3   54.65  5427.2    51.4  5847.2    55.7  5957.2    56.2
  6037.2    54.4  6067.2    56.7  6357.2    55.5    6551   56.77  6827.2    58.4
#Mann= 5 , 1 , 0
    3752      .2       0  3799.3      .1       0  4937.2    .045       0
  5059.3      .1       0    6551      .2       0
#XS Ineff= 2 , 0
       0  4926.4    58.4  5081.7       0    58.4
Permanent Ineff=
       F       F
Bank Sta=4937.2,5059.3
XS Rating Curve= 0
Exp/Cntr=.5,.3

Type RM Length L Ch R = 3 ,35025.9 ,,,
BEGIN DESCRIPTION:
SOUTHERN PACIFIC RAILROAD
Structure ID: P18-11,,,,
END DESCRIPTION:
Bridge Culvert--1,0,-1,-1, 0
Deck Dist Width WeirC Skew NumUp NumDn MinLoCord MaxHiCord MaxSubmerge Is_Ogee
10,19.6,2.6,0, 48, 48, , , .95, 0, 1,1,,
    3752    3832    3882    3912    3942    4042    4132  4388.5  4448.5  4508.5
  4568.5  4598.5  4638.5  4662.3  4735.2  4797.8  4862.3  4935.8 4936.81  4936.9
  4997.4 5071.29  5071.4  5123.7  5176.9  5240.5  5262.2  5335.1  5336.3  5377.2
  5427.2  5477.2  5527.2  5587.2  5607.2  5727.2  5847.2  5927.2  5957.2  6037.2
  6067.2  6327.2  6357.2  6487.2  6577.2  6697.2  6819.3  6827.2
      62    60.7   60.61   60.44   60.37   60.14   59.94   59.35   59.22   59.08
   58.95   58.88   58.79   58.73   58.57   58.43   58.36   58.37   58.37   58.37
   58.31   58.38   58.38   58.35   58.34   58.37   58.38   58.41   58.41   58.42
   58.44   58.46   58.49   58.51   58.52   58.57   58.61   58.65   58.66   58.69
    58.7   58.81   58.82   58.87    58.9    58.9    58.9    58.4
      62    60.7    60.6    59.1    59.1    57.1    57.2    56.2    54.5    51.9
    53.3    51.2    52.4    51.2   52.21   52.22   54.98   53.77   50.75   56.23
   56.17   56.24      51   55.26   54.98   54.48   53.33   52.61   54.65    53.5
    51.4      53    52.9    53.4      53      55    55.7    55.1    56.2    54.4
    56.7    56.4    55.5    57.2    56.6      57   58.31    58.4
    3752    3832    3882    3912    3942    4042    4132  4388.5  4448.5  4508.5
  4568.5  4598.5  4638.5  4662.3  4735.2  4797.8  4862.3  4935.8 4936.81  4936.9
  4997.4 5071.29  5071.4  5123.7  5176.9  5240.5  5262.2  5335.1  5336.3  5377.2
  5427.2  5477.2  5527.2  5587.2  5607.2  5727.2  5847.2  5927.2  5957.2  6037.2
  6067.2  6327.2  6357.2  6487.2  6577.2  6697.2  6819.3  6827.2
      62    60.7   60.61   60.44   60.37   60.14   59.94   59.35   59.22   59.08
   58.95   58.88   58.79   58.73   58.57   58.43   58.36   58.37   58.37   58.37
   58.31   58.38   58.38   58.35   58.34   58.37   58.38   58.41   58.41   58.42
   58.44   58.46   58.49   58.51   58.52   58.57   58.61   58.65   58.66   58.69
    58.7   58.81   58.82   58.87    58.9    58.9    58.9    58.4
    61.8    60.5    60.4    58.9    58.9    56.9      57      56    54.3    51.7
    53.1      51    52.2      51   52.01   52.02   54.78   53.57   50.55   56.03
   55.97   56.04    50.8   55.06   54.78   54.28   53.13   52.41   54.45    53.3
    51.2    52.8    52.7    53.2    52.8    54.8    55.5    54.9      56    54.2
    56.5    56.2    55.3      57    56.4    56.8   58.11    58.2
Pier Skew, UpSta & Num, DnSta & Num=  ,4952.5, 2 ,4952.5, 2 , 0 , 0 , 0 ,,
       1       1
    43.3   57.21
       1       1
    43.1   57.01
Pier Skew, UpSta & Num, DnSta & Num=  ,4967.4, 2 ,4967.4, 2 , 0 , 0 , 0 ,,
       1       1
   34.85    57.2
       1       1
   34.65      57
Pier Skew, UpSta & Num, DnSta & Num=  ,4982.4, 2 ,4982.4, 2 , 0 , 0 , 0 ,,
       1       1
   31.01   57.19
       1       1
   30.81   56.99
Pier Skew, UpSta & Num, DnSta & Num=  ,4997.3, 2 ,4997.3, 2 , 0 , 0 , 0 ,,
       1       1
   31.82   57.17
       1       1
   31.62   56.97
Pier Skew, UpSta & Num, DnSta & Num=  ,5012.1, 2 ,5012.1, 2 , 0 , 0 , 0 ,,
       1       1
    30.6   57.18
       1       1
    30.4   56.98
Pier Skew, UpSta & Num, DnSta & Num=  ,5026.8, 2 ,5026.8, 2 , 0 , 0 , 0 ,,
       1       1
   33.39    57.2
       1       1
   33.19      57
Pier Skew, UpSta & Num, DnSta & Num=  ,5042.2, 2 ,5042.2, 2 , 0 , 0 , 0 ,,
       1       1
   38.95   57.21
       1       1
   38.75   57.01
Pier Skew, UpSta & Num, DnSta & Num=  ,5057.4, 2 ,5057.4, 2 , 0 , 0 , 0 ,,
       1       1
    47.7   57.23
       1       1
    47.5   57.03
Abutment Skew #Up #Dn= , 2 , 2
  4936.7  4945.5
   56.23    47.7
  4936.7  4945.5
   56.03    47.5
Abutment Skew #Up #Dn= , 2 , 2
  5051.7 5071.49
   48.32   56.24
  5051.7 5071.49
   48.12   56.04
BR Coef= 1 , 1 , 0 ,1.25, 0 ,,,.8,0,2,0,
WSPro=,,,, 1 ,,,, 0 ,,,, 0 ,,,,-1 ,-1 ,-1 , 0 , 0 , 0 , 0 , 0
BR U #Sta/Elev= 79
    3752      62  3799.3   61.23    3832    60.7  3839.3   60.69    3882    60.6
    3912    59.1    3942    59.1    4042    57.1    4062    57.1    4132    57.2
    4212    56.9  4388.5    56.2  4448.5    54.5  4508.5    51.9  4568.5    53.3
  4598.5    51.2  4638.5    52.4  4662.3    51.2  4735.2   52.21  4797.8   52.22
  4817.8   53.08  4862.3   54.98  4891.4    54.5  4935.8   53.77  4936.7   51.08
 4936.81   50.75  4936.9   50.49  4937.2   49.59  4945.4   47.72  4945.5    47.7
  4952.5   44.59  4967.4   36.04  4973.2   33.81  4982.4   32.01  4985.9      32
  4997.4   32.87  4997.9   32.83  5012.1   31.55  5026.8   34.49  5034.8   37.95
  5042.2   40.09  5047.9   48.05  5051.6   48.31  5051.7   48.32  5057.4   48.74
  5059.3   48.96  5064.1   50.41 5071.29      51  5071.4      51  5071.5   51.01
  5123.7   55.26    5156   55.09  5176.9   54.98  5240.5   54.48    5243   54.35
  5262.2   53.33  5335.1   52.61  5336.3   54.65  5377.2    53.5  5427.2    51.4
  5477.2      53  5527.2    52.9  5587.2    53.4  5607.2      53  5727.2      55
  5797.2    55.4  5847.2    55.7  5927.2    55.1  5957.2    56.2  6037.2    54.4
  6067.2    56.7  6327.2    56.4  6357.2    55.5  6487.2    57.2    6551   56.77
  6577.2    56.6  6697.2      57  6819.3   58.31  6827.2    58.4
BR U #Mann= 5
    3752      .2  3799.3      .1  4937.2    .045  5059.3      .1    6551      .2
BR U Banks=4937.2,5059.3
BR D #Sta/Elev= 79
    3752    61.8  3799.3   61.03    3832    60.5  3839.3   60.49    3882    60.4
    3912    58.9    3942    58.9    4042    56.9    4062    56.9    4132      57
    4212    56.7  4388.5      56  4448.5    54.3  4508.5    51.7  4568.5    53.1
  4598.5      51  4638.5    52.2  4662.3      51  4735.2   52.01  4797.8   52.02
  4817.8   52.88  4862.3   54.78  4891.4    54.3  4935.8   53.57  4936.7   50.88
 4936.81   50.55  4936.9   50.29  4937.2   49.39  4945.4   47.52  4945.5    47.5
  4952.5   44.39  4967.4   35.84  4973.2   33.61  4982.4   31.81  4985.9    31.8
  4997.4   32.67  4997.9   32.63  5012.1   31.35  5026.8   34.29  5034.8   37.75
  5042.2   39.89  5047.9   47.85  5051.6   48.11  5051.7   48.12  5057.4   48.54
  5059.3   48.76  5064.1   50.21 5071.29    50.8  5071.4    50.8  5071.5   50.81
  5123.7   55.06    5156   54.89  5176.9   54.78  5240.5   54.28    5243   54.15
  5262.2   53.13  5335.1   52.41  5336.3   54.45  5377.2    53.3  5427.2    51.2
  5477.2    52.8  5527.2    52.7  5587.2    53.2  5607.2    52.8  5727.2    54.8
  5797.2    55.2  5847.2    55.5  5927.2    54.9  5957.2      56  6037.2    54.2
  6067.2    56.5  6327.2    56.2  6357.2    55.3  6487.2      57    6551   56.57
  6577.2    56.4  6697.2    56.8  6819.3   58.11  6827.2    58.2
BR D #Mann= 5
    3752      .2  3799.3      .1  4937.2    .045  5059.3      .1    6551      .2
BR D Banks=4937.2,5059.3
BC Design=,, 0 ,, 0 ,,,,,,

Type RM Length L Ch R = 1 ,35006.1 ,21.8,21.8,21.8
BEGIN DESCRIPTION:
Downstream Section of Bridge/Culvert/Weir
END DESCRIPTION:
XS GIS Cut Line= 3
      3135730.12     13880871.61      3135337.07     13879684.58
      3134747.98      13877957.5
#Sta/Elev= 30
    3752   61.54  3799.3   60.77    4042   56.64  4388.5   55.74  4508.5   51.44
  4568.5   52.84  4598.5   50.74  4797.8   51.76  4862.3   54.52  4935.8   53.31
  4937.2   49.13  4945.5   47.24  4973.2   33.35  4982.4   31.55  5012.1   31.09
  5026.8   34.03  5042.2   39.63  5047.9   47.59  5059.3    48.5  5123.7    54.8
  5335.1   52.15  5336.3   54.19  5427.2   50.94  5847.2   55.24  5957.2   55.74
  6037.2   53.94  6067.2   56.24  6357.2   55.04    6551   56.31  6827.2   57.94
#Mann= 5 , 1 , 0
    3752      .2       0  3799.3      .1       0  4937.2    .045       0
  5059.3      .1       0    6551      .2       0
#XS Ineff= 2 , 0
       0  4926.4    58.2  5081.7       0    58.2
Permanent Ineff=
       F       F
Bank Sta=4937.2,5059.3
XS Rating Curve= 0
Exp/Cntr=.5,.3

Type RM Length L Ch R = 1 ,34984.3 ,114,114,114
BEGIN DESCRIPTION:
Upstream Section of Bridge/Culvert/Weir
END DESCRIPTION:
XS GIS Cut Line= 6
       3135757.8      13880859.2      3135582.39     13880283.98
      3135496.52     13880038.14      3135374.11     13879755.97
       3135222.3     13879170.94      3134733.17     13877729.23
#Sta/Elev= 30
    3752   62.26    3882   60.86    4042   57.36  4388.5   56.46  4508.5   52.16
  4548.5   52.06  4568.5   53.56  4618.5   49.56  4638.5   52.66  4699.4   53.54
  4734.6   52.17  4923.5   55.48  4934.2   52.63  4960.5   42.88  4966.6   37.61
  4993.4   30.53  5017.8   33.93  5042.3   41.82  5069.6   45.34  5115.3   55.38
  5427.2   51.66  5477.2   53.26  5607.2   53.26  5847.2   55.96  5927.2   55.36
  5957.2   56.46  6037.2   54.66  6067.2   56.96  6577.2   56.86  7049.1   58.86
#Mann= 4 , 1 , 0
    3752      .1       0  4934.2    .045       0  5042.3      .1       0
  7049.1      .2       0
#XS Ineff= 2 , 0
       0    4896    58.2    5111       0    58.2
Permanent Ineff=
       F       F
Bank Sta=4934.2,5042.3
XS Rating Curve= 0
Exp/Cntr=.5,.3

Type RM Length L Ch R = 3 ,34927.3 ,,,
BEGIN DESCRIPTION:
HIRSCH STREET
Structure ID: P18-10
END DESCRIPTION:
Bridge Culvert--1,0,-1,-1, 0
Deck Dist Width WeirC Skew NumUp NumDn MinLoCord MaxHiCord MaxSubmerge Is_Ogee
10,94,2.6,0, 54, 54, , , .95, 0, 1,1,,
    3752    3832    3882    3912    3942    4042    4132  4388.5  4448.5  4508.5
  4548.5  4568.5  4598.5  4618.5  4638.5  4666.7  4699.4  4734.6  4831.3  4923.5
 4923.59  4923.7  4934.4  4934.5  5022.8 5104.99  5105.1  5115.3  5115.6 5115.71
  5179.5  5253.7  5310.1  5340.3  5383.8  5427.2  5477.2  5527.2  5587.2  5607.2
  5727.2  5847.2  5927.2  5957.2  6037.2  6067.2  6327.2  6487.2  6577.2  6697.2
  6827.2  6890.8  7016.7  7049.1
      62    60.7    60.6    59.1    59.1    57.1    57.2   56.21   55.49   55.17
   54.95   54.84   54.68   54.55   54.33   54.02   54.01   54.01   54.54   55.42
   55.42   56.92   57.02   57.02   57.83   57.02   57.02    56.9    56.9    55.4
   54.95   54.02   53.75   53.78   53.84   53.89   53.94      54   54.27   54.36
   55.01   55.71   55.77   56.21   56.26   56.71   57.52   57.78   57.92   58.12
   58.33   58.49    58.8    58.6
      62    60.7    60.6    59.1    59.1    57.1    57.2    56.2    54.5    51.9
    51.8    53.3    51.2    49.3    52.4   52.27   53.28   51.91   53.83   55.22
    55.2   55.17   52.31   53.02   53.83   53.02   52.18   55.12   55.12   55.12
   54.94   54.01   53.07   52.56    52.5    51.4      53    52.9    53.4      53
      55    55.7    55.1    56.2    54.4    56.7    56.4    57.2    56.6      57
    57.8    57.4   58.35    58.6
    3752    3832    3882    3912    3942    4042    4132  4388.5  4448.5  4508.5
  4548.5  4568.5  4598.5  4618.5  4638.5  4666.7  4699.4  4734.6  4831.3  4923.5
 4923.59  4923.7  4934.4  4934.5  5022.8 5104.99  5105.1  5115.3  5115.6 5115.71
  5179.5  5253.7  5310.1  5340.3  5383.8  5427.2  5477.2  5527.2  5587.2  5607.2
  5727.2  5847.2  5927.2  5957.2  6037.2  6067.2  6327.2  6487.2  6577.2  6697.2
  6827.2  6890.8  7016.7  7049.1
      62    60.7    60.6    59.1    59.1    57.1    57.2   56.21   55.49   55.17
   54.95   54.84   54.68   54.55   54.33   54.02   54.01   54.01   54.54   55.42
   55.42   56.92   57.02   57.02   57.83   57.02   57.02    56.9    56.9    55.4
   54.95   54.02   53.75   53.78   53.84   53.89   53.94      54   54.27   54.36
   55.01   55.71   55.77   56.21   56.26   56.71   57.52   57.78   57.92   58.12
   58.33   58.49    58.8    58.6
   61.73   60.43   60.33   58.83   58.83   56.83   56.93   55.93   54.23   51.63
   51.53   53.03   50.93   49.03   52.13      52   53.01   51.64   53.56   54.95
   54.93    54.9   52.04   52.75   53.56   52.75   51.91   54.85   54.85   54.85
   54.67   53.74    52.8   52.29   52.23   51.13   52.73   52.63   53.13   52.73
   54.73   55.43   54.83   55.93   54.13   56.43   56.13   56.93   56.33   56.73
   57.53   57.13   58.08   58.33
Pier Skew, UpSta & Num, DnSta & Num=  ,4989.8, 2 ,4989.8, 2 , 0 , 0 , 0 ,,
     1.5     1.5
   29.59   54.54
     1.5     1.5
   29.32   54.27
Pier Skew, UpSta & Num, DnSta & Num=  ,5046.7, 2 ,5046.7, 2 , 0 , 0 , 0 ,,
     1.5     1.5
   40.84    54.6
     1.5     1.5
   40.57   54.33
BR Coef= 1 , 1 , 0 ,1.25, 0 ,,,.8,-1,2,0,
WSPro=,,,, 1 ,,,, 0 ,,,, 0 ,,,,-1 ,-1 ,-1 , 0 , 0 , 0 , 0 , 0
BR U #Sta/Elev= 91
    3752      62    3832    60.7    3882    60.6    3912    59.1    3942    59.1
    4042    57.1    4062    57.1    4132    57.2    4212    56.9  4353.4   56.34
  4388.5    56.2  4448.5    54.5  4508.5    51.9  4548.5    51.8  4568.5    53.3
  4598.5    51.2  4613.8   49.75  4618.5    49.3  4638.5    52.4  4666.7   52.27
  4667.8    52.3  4699.4   53.28  4734.6   51.91  4740.2   52.02  4830.3   53.81
  4831.3   53.83  4923.5   55.22 4923.59    55.2  4923.7   55.17 4923.81   55.14
  4934.2   52.37 4934.31   52.34  4934.4   52.31  4934.5   52.29  4934.6   52.26
  4960.5   42.62  4966.6   37.35  4975.6   35.61  4982.1   33.41  4989.8   30.67
  4993.4   30.27  4997.6    30.9  5005.1   31.35  5017.8   33.67  5022.8    35.6
  5028.3   37.73  5042.3   41.56  5046.7    41.9  5069.6   45.08  5092.4   49.44
  5104.7   52.07  5104.8   52.09 5104.99   52.14  5105.1   52.18  5105.2   52.21
  5115.3   55.12 5115.49   55.12  5115.6   55.12 5115.71   55.12  5168.9   54.97
  5179.5   54.94  5240.7   54.17  5253.7   54.01  5310.1   53.07  5340.3   52.56
  5383.7    52.5  5383.8    52.5  5427.2    51.4  5477.2      53  5526.7    52.9
  5527.2    52.9  5587.2    53.4  5607.2      53  5727.2      55  5797.2    55.4
  5847.2    55.7  5927.2    55.1  5957.2    56.2  6037.2    54.4  6067.2    56.7
  6316.7   56.41  6327.2    56.4  6487.2    57.2  6577.2    56.6  6697.2      57
  6746.7    57.3  6816.7   57.74  6827.2    57.8  6890.8    57.4  7016.7   58.35
  7049.1    58.6
BR U #Mann= 4
    3752      .1  4934.2    .045  5042.3      .1  7049.1      .2
BR U Banks=4934.2,5042.3
BR D #Sta/Elev= 91
    3752   61.73    3832   60.43    3882   60.33    3912   58.83    3942   58.83
    4042   56.83    4062   56.83    4132   56.93    4212   56.63  4353.4   56.07
  4388.5   55.93  4448.5   54.23  4508.5   51.63  4548.5   51.53  4568.5   53.03
  4598.5   50.93  4613.8   49.48  4618.5   49.03  4638.5   52.13  4666.7      52
  4667.8   52.03  4699.4   53.01  4734.6   51.64  4740.2   51.75  4830.3   53.54
  4831.3   53.56  4923.5   54.95 4923.59   54.93  4923.7    54.9 4923.81   54.87
  4934.2    52.1 4934.31   52.07  4934.4   52.04  4934.5   52.02  4934.6   51.99
  4960.5   42.35  4966.6   37.08  4975.6   35.34  4982.1   33.14  4989.8    30.4
  4993.4      30  4997.6   30.63  5005.1   31.08  5017.8    33.4  5022.8   35.33
  5028.3   37.46  5042.3   41.29  5046.7   41.63  5069.6   44.81  5092.4   49.17
  5104.7    51.8  5104.8   51.82 5104.99   51.87  5105.1   51.91  5105.2   51.94
  5115.3   54.85 5115.49   54.85  5115.6   54.85 5115.71   54.85  5168.9    54.7
  5179.5   54.67  5240.7    53.9  5253.7   53.74  5310.1    52.8  5340.3   52.29
  5383.7   52.23  5383.8   52.23  5427.2   51.13  5477.2   52.73  5526.7   52.63
  5527.2   52.63  5587.2   53.13  5607.2   52.73  5727.2   54.73  5797.2   55.13
  5847.2   55.43  5927.2   54.83  5957.2   55.93  6037.2   54.13  6067.2   56.43
  6316.7   56.14  6327.2   56.13  6487.2   56.93  6577.2   56.33  6697.2   56.73
  6746.7   57.03  6816.7   57.47  6827.2   57.53  6890.8   57.13  7016.7   58.08
  7049.1   58.33
BR D #Mann= 4
    3752      .1  4934.2    .045  5042.3      .1  7049.1      .2
BR D Banks=4934.2,5042.3
BC Design=,, 0 ,, 0 ,,,,,,

Type RM Length L Ch R = 1 ,34870.3 ,950.2,950.2,950.2
BEGIN DESCRIPTION:
Downstream Section of Bridge/Culvert/Weir
END DESCRIPTION:
XS GIS Cut Line= 6
      3135863.54      13880816.6      3135688.13     13880241.38
      3135602.26     13879995.54      3135479.85     13879713.37
      3135328.04     13879128.34      3134838.91     13877686.63
#Sta/Elev= 30
    3752   61.73    3882   60.33    4042   56.83  4388.5   55.93  4508.5   51.63
  4548.5   51.53  4568.5   53.03  4618.5   49.03  4638.5   52.13  4699.4   53.01
  4734.6   51.64  4923.5   54.95  4934.2    52.1  4960.5   42.35  4966.6   37.08
  4993.4      30  5017.8    33.4  5042.3   41.29  5069.6   44.81  5115.3   54.85
  5427.2   51.13  5477.2   52.73  5607.2   52.73  5847.2   55.43  5927.2   54.83
  5957.2   55.93  6037.2   54.13  6067.2   56.43  6577.2   56.33  7049.1   58.33
#Mann= 4 , 1 , 0
    3752      .1       0  4934.2    .045       0  5042.3      .1       0
  7049.1      .2       0
#XS Ineff= 2 , 0
       0    4786    58.1    5220       0    58.1
Permanent Ineff=
       F       F
Bank Sta=4934.2,5042.3
XS Rating Curve= 0
Exp/Cntr=.5,.3

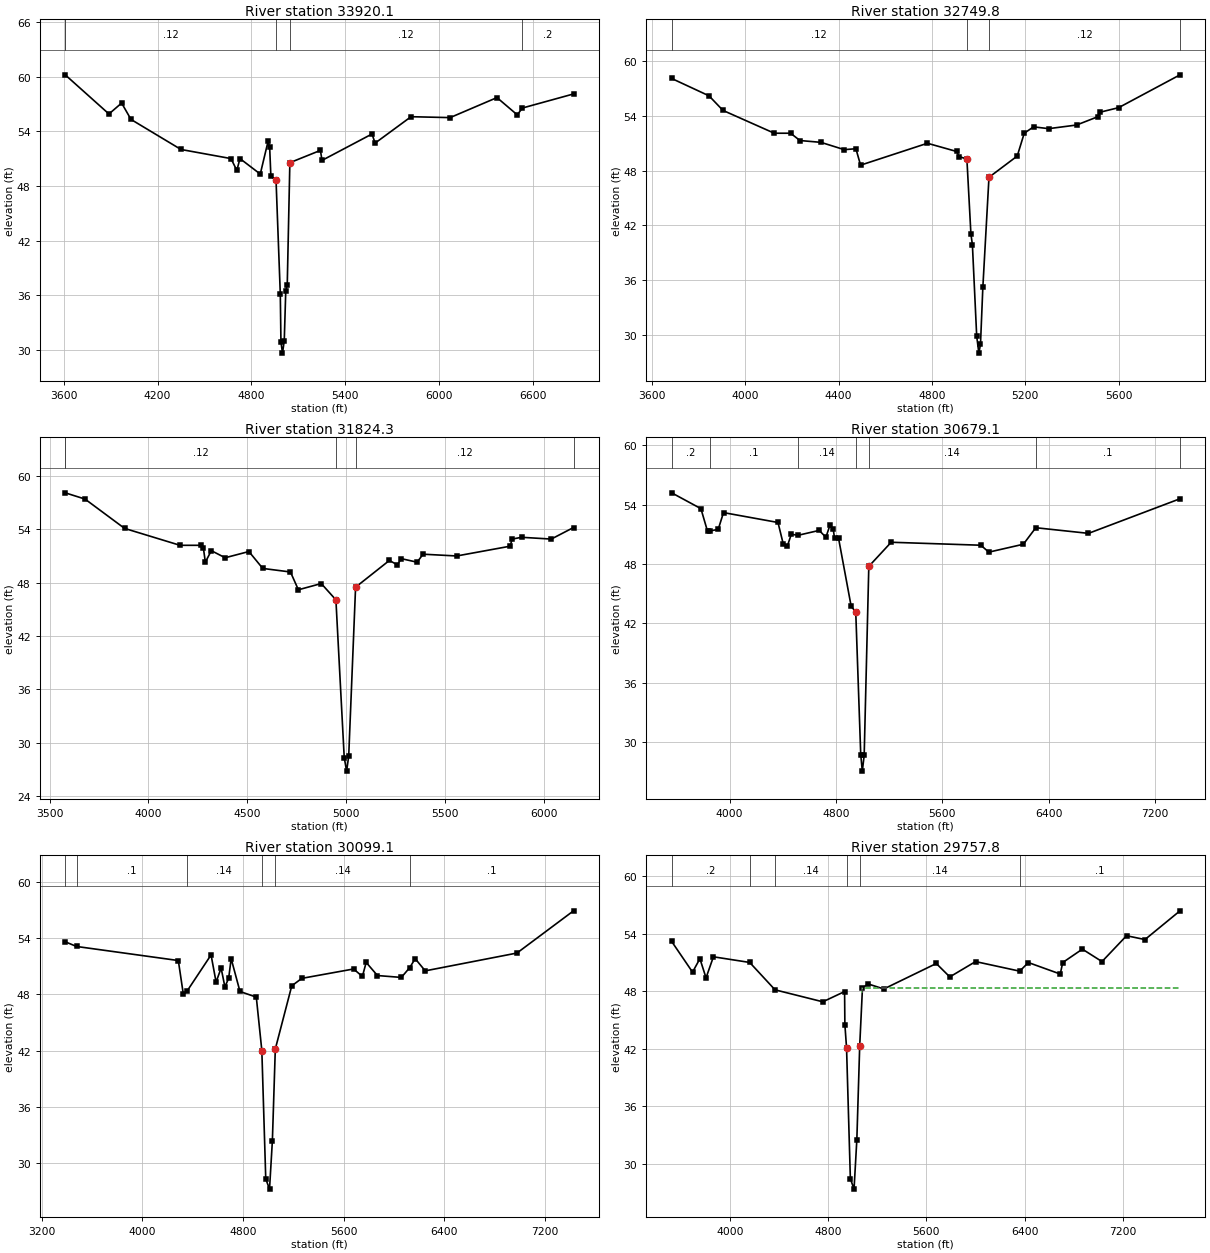
Type RM Length L Ch R = 1 ,33920.1 ,1155.8,1170.3,1172.7
BEGIN DESCRIPTION:
Cross Section 33920.1
END DESCRIPTION:
XS GIS Cut Line= 6
      3136791.69     13880357.03      3136651.15      13880024.4
      3136398.16     13879363.83      3136121.75     13879045.25
      3136051.48     13878956.24      3135226.93     13877527.07
#Sta/Elev= 30
  3608.6    60.2  3888.6    55.9  3969.7    57.1  4029.7    55.3  4349.7      52
  4669.7      51  4707.1    49.7  4727.1      51  4857.1    49.3  4907.1    52.9
  4917.1    52.3    4925   49.05    4958   48.64  4985.3   36.14  4989.4   30.87
  4999.4   29.63  5010.6   30.98  5020.3   36.47  5029.8   37.14  5046.5   50.55
  5242.2    51.9  5252.2    50.8  5572.2    53.7  5592.2    52.7  5822.2    55.6
  6072.2    55.5  6372.2    57.7  6502.2    55.8  6534.2   56.55  6862.2    58.1
#Mann= 5 , 1 , 0
  3608.6      .2       0  3608.6     .12       0    4958    .045       0
  5046.5     .12       0  6534.2      .2       0
Bank Sta=4958,5046.5
XS Rating Curve= 0
Exp/Cntr=.3,.1

Type RM Length L Ch R = 1 ,32749.8 ,787.8,925.5,1026.2
BEGIN DESCRIPTION:
Cross Section 32749.8
END DESCRIPTION:
XS GIS Cut Line= 5
      3137537.68     13879450.55      3137274.24     13878656.41
      3137044.68      13878347.2      3136777.64     13878056.74
      3136370.05     13877667.89
#Sta/Elev= 30
    3684    58.1    3844    56.2    3904    54.6    4124    52.1    4194    52.1
    4234    51.3    4324    51.1    4424    50.3    4474    50.4    4494    48.6
  4780.7      51  4905.8    50.1  4916.7   49.54  4949.9   49.27  4967.2   41.03
  4973.5   39.89  4991.9   29.87  5001.2      28  5008.2   28.97  5018.3   35.21
  5044.6   47.27  5165.8    49.6  5195.8    52.1  5235.8    52.8  5300.4    52.6
  5420.4      53  5510.4    53.9  5520.4    54.4  5600.4    54.9  5863.7    58.5
#Mann= 4 , 1 , 0
    3684     .12       0  4949.9    .045       0  5044.6     .12       0
  5863.7      .2       0
Bank Sta=4949.9,5044.6
XS Rating Curve= 0
Exp/Cntr=.3,.1

Type RM Length L Ch R = 1 ,31824.3 ,1157.4,1145.2,998.7
BEGIN DESCRIPTION:
Cross Section 31824.3
END DESCRIPTION:
XS GIS Cut Line= 6
      3138248.71     13879251.39      3137811.24      13878720.2
      3137781.99     13878225.61      3137808.59     13877822.12
      3137247.89      13877420.5      3136957.89     13877401.02
#Sta/Elev= 30
  3579.2    58.1  3679.2    57.4  3879.2    54.1  4159.2    52.2  4267.3    52.2
  4277.3    51.9  4287.3    50.3  4317.3    51.6  4387.3    50.8  4507.3    51.5
  4577.3    49.6  4717.3    49.2  4757.3    47.2  4872.8    47.9  4946.9   46.07
  4988.9   28.34    5001   26.81  5011.6   28.51  5046.3   47.49  5217.2    50.5
  5257.2      50  5277.2    50.7  5357.2    50.3  5387.2    51.2  5557.2      51
  5827.2    52.1  5837.2    52.9    5885    53.1    6035    52.9  6147.5    54.2
#Mann= 5 , 1 , 0
  3579.2      .2       0  3579.2     .12       0  4946.9    .045       0
  5046.3     .12       0  6147.5      .2       0
Bank Sta=4946.9,5046.3
XS Rating Curve= 0
Exp/Cntr=.3,.1

Type RM Length L Ch R = 1 ,30679.1 ,629.9,580,490.2
BEGIN DESCRIPTION:
Cross Section 30679.1
END DESCRIPTION:
XS GIS Cut Line= 6
      3139662.36     13879283.12      3139154.57     13878340.97
      3139023.68     13878306.06       3138898.6     13878195.53
      3138503.22     13877441.14      3136907.43     13877350.47
#Sta/Elev= 30
  3564.5    55.2  3784.5    53.6  3834.5    51.3  3852.6   51.35  3914.5    51.5
  3954.5    53.2  4364.5    52.2  4404.5      50  4434.5    49.8  4464.5      51
  4517.3   50.91  4674.8    51.4  4724.8    50.7  4754.8    51.9  4780.2    51.5
  4790.2    50.6  4820.2    50.6  4915.2   43.71  4949.5   43.16    4987   28.73
  4998.8   27.05  5012.9   28.64  5047.8   47.76  5216.1    50.2  5890.7    49.9
  5950.7    49.2  6210.7      50  6304.1   51.67  6700.7    51.1  7389.2    54.6
#Mann= 7 , 1 , 0
  3564.5      .2       0  3852.6      .1       0  4517.3     .14       0
  4949.5    .045       0  5047.8     .14       0  6304.1      .1       0
  7389.2      .2       0
#XS Ineff= 2 , 0
       0  3954.5    53.2               0
Permanent Ineff=
       F       F
Bank Sta=4949.5,5047.8
XS Rating Curve= 0
Exp/Cntr=.3,.1

Type RM Length L Ch R = 1 ,30099.1 ,353.7,341.3,305.1
BEGIN DESCRIPTION:
Cross Section 30099.1-Interpolated
END DESCRIPTION:
XS GIS Cut Line= 5
      3140236.49     13878723.48      3139498.27     13877841.01
      3138945.06     13877556.76       3138556.9     13877366.81
      3136717.83     13877309.47
#Sta/Elev= 30
  3385.6    53.6  3475.8    53.1  4285.6    51.6  4325.6      48  4353.1    48.3
  4546.1    52.2  4586.1    49.3  4626.1    50.8  4656.1    48.8  4686.1    49.7
  4706.1    51.8  4776.1    48.3  4906.1    47.7 4950.14      42  4981.3   28.32
 5011.23   27.23 5034.03   32.39 5057.32   42.17  5188.1    48.9  5268.1    49.7
  5680.2    50.7  5750.2    49.9  5780.2    51.4  5870.2      50  6060.2    49.8
    6127   50.85  6170.2    51.8  6250.2    50.5  6980.2    52.4  7430.2    56.9
#Mann= 6 , 1 , 0
  3385.6      .2       0  3475.8      .1       0  4353.1     .14       0
 4950.14    .045       0 5057.32     .14       0    6127      .1       0
Bank Sta=4950.14,5057.32
XS Rating Curve= 0
Exp/Cntr=.5,.3

Type RM Length L Ch R = 1 ,29757.8 ,53,53,53
BEGIN DESCRIPTION:
Upstream Section of Bridge/Culvert/Weir
END DESCRIPTION:
XS GIS Cut Line= 6
       3140521.5     13878286.28       3140260.3     13877877.59
      3139242.02     13877391.31      3139154.07     13877353.72
      3138970.53     13877335.97      3136724.01     13877260.39
#Sta/Elev= 30
  3525.5    53.2  3695.5      50  3755.5    51.4  3805.5    49.4  3865.5    51.6
  4161.2   51.01  4367.7   48.15 4756.95    46.9 4934.24   47.97 4936.53   44.53
 4950.14   42.11  4981.3   28.43 5011.23   27.34 5034.03    32.5 5057.32   42.28
 5079.95   48.38 5127.18   48.76 5254.12   48.24  5681.3    50.9  5791.3    49.5
  6001.3    51.1    6361    50.1  6431.3      51  6691.3    49.8  6711.3      51
  6871.3    52.4  7031.3    51.1  7231.3    53.8  7381.3    53.4  7666.8    56.4
#Mann= 6 , 1 , 0
  3525.5      .2       0  4161.2      .1       0  4367.7     .14       0
 4950.14    .045       0 5057.32     .14       0    6361      .1       0
#XS Ineff= 2 , 0
       0    4925    47.1    5078       0    48.3
Permanent Ineff=
       F       F
Bank Sta=4950.14,5057.32
XS Rating Curve= 0
Exp/Cntr=.5,.3

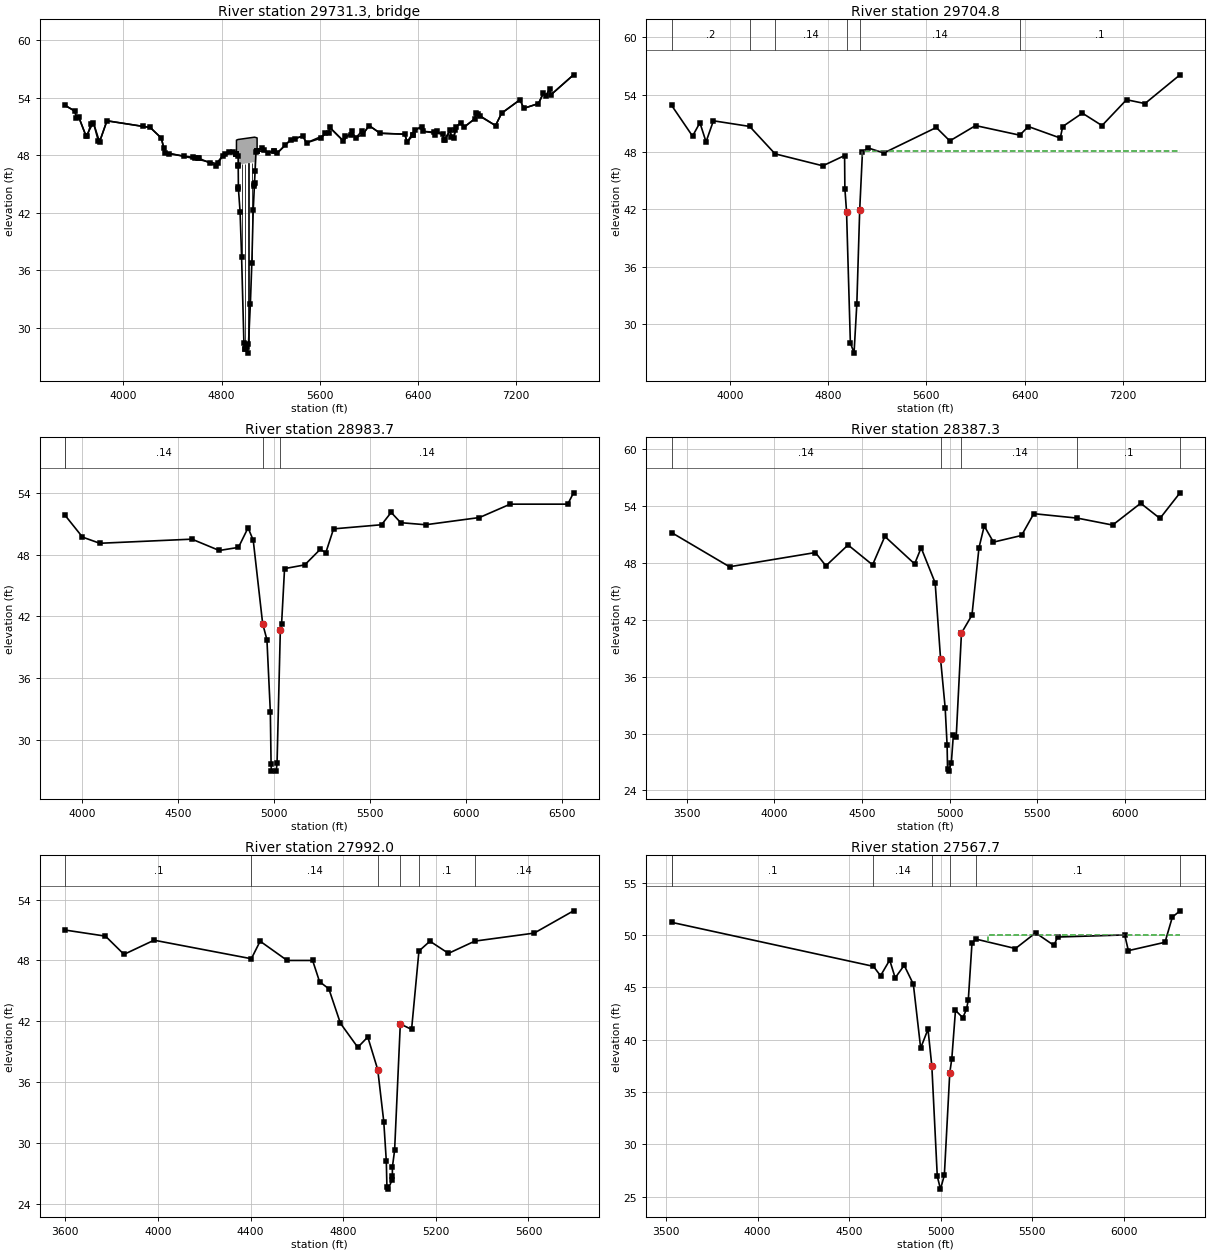
Type RM Length L Ch R = 3 ,29731.3 ,,,
BEGIN DESCRIPTION:
PARKER ROAD, SKEW ANGLE OF 35 DEGREES
Structure ID: P18-8
END DESCRIPTION:
Bridge Culvert--1,0,-1,-1, 0
Deck Dist Width WeirC Skew NumUp NumDn MinLoCord MaxHiCord MaxSubmerge Is_Ogee
10,33,2.6,0, 60, 60, , , .95, 0, 1,1,,
  3525.5  3605.5  3615.5  3635.5  3695.5  3755.5  3805.5  3865.5  4218.2  4308.2
  4338.2 4756.95 4807.63 4894.96 4920.69  4920.8 4934.24 4934.88 5067.54 5067.65
 5079.95  5088.8 5088.91 5254.12  5361.3  5461.3  5491.3  5671.3  5681.3  5791.3
  5861.3  5891.3  5951.3  6001.3  6091.3  6291.3  6311.3  6371.3  6431.3  6441.3
  6601.3  6611.3  6661.3  6671.3  6691.3  6711.3  6751.3  6771.3  6861.3  6871.3
  7031.3  7081.3  7231.3  7261.3  7381.3  7421.3  7441.3  7471.3  7481.3  7666.8
    53.2    52.6    51.9      52      50    51.4    49.4    51.6    50.9    49.8
   48.32   47.14   47.94   48.34    48.1   49.58   49.65   49.65   49.89   49.89
   49.85   49.81   48.46   48.25   49.61      50    49.3    50.3    50.9    49.5
    50.5    49.8    50.2    51.1    50.3    50.2    49.4    50.6      51    50.5
    50.2    49.6    50.6    49.9    49.8      51    51.4    50.9    51.8    52.4
    51.1    52.4    53.8    52.9    53.4    54.5    54.2    54.9    54.3    56.4
    53.2    52.6    51.9      52      50    51.4    49.4    51.6    50.9    49.8
    48.2    46.9   47.93   48.33   48.09   48.09   47.97   47.01   47.29   45.06
   48.38   48.45   48.45   48.24    49.6      50    49.3    50.3    50.9    49.5
    50.5    49.8    50.2    51.1    50.3    50.2    49.4    50.6      51    50.5
    50.2    49.6    50.6    49.9    49.8      51    51.4    50.9    51.8    52.4
    51.1    52.4    53.8    52.9    53.4    54.5    54.2    54.9    54.3    56.4
  3525.5  3605.5  3615.5  3635.5  3695.5  3755.5  3805.5  3865.5  4218.2  4308.2
  4338.2 4756.95 4807.63 4894.96 4920.69  4920.8 4934.24 4934.88 5067.54 5067.65
 5079.95  5088.8 5088.91 5254.12  5361.3  5461.3  5491.3  5671.3  5681.3  5791.3
  5861.3  5891.3  5951.3  6001.3  6091.3  6291.3  6311.3  6371.3  6431.3  6441.3
  6601.3  6611.3  6661.3  6671.3  6691.3  6711.3  6751.3  6771.3  6861.3  6871.3
  7031.3  7081.3  7231.3  7261.3  7381.3  7421.3  7441.3  7471.3  7481.3  7666.8
    53.2    52.6    51.9      52      50    51.4    49.4    51.6    50.9    49.8
   48.32   47.14   47.94   48.34    48.1   49.58   49.65   49.65   49.89   49.89
   49.85   49.81   48.46   48.25   49.61      50    49.3    50.3    50.9    49.5
    50.5    49.8    50.2    51.1    50.3    50.2    49.4    50.6      51    50.5
    50.2    49.6    50.6    49.9    49.8      51    51.4    50.9    51.8    52.4
    51.1    52.4    53.8    52.9    53.4    54.5    54.2    54.9    54.3    56.4
   52.86   52.26   51.56   51.66   49.66   51.06   49.06   51.26   50.56   49.46
   47.86   46.56   47.59   47.99   47.75   47.75   47.63   46.67   46.95   44.72
   48.04   48.11   48.11    47.9   49.26   49.66   48.96   49.96   50.56   49.16
   50.16   49.46   49.86   50.76   49.96   49.86   49.06   50.26   50.66   50.16
   49.86   49.26   50.26   49.56   49.46   50.66   51.06   50.56   51.46   52.06
   50.76   52.06   53.46   52.56   53.06   54.16   53.86   54.56   53.96   56.06
Pier Skew, UpSta & Num, DnSta & Num=  ,4962.5, 2 ,4962.5, 2 , 0 , 0 , 0 ,,
     1.5     1.5
   36.02   48.19
     1.5     1.5
   35.68   47.85
Pier Skew, UpSta & Num, DnSta & Num=  ,4989.9, 2 ,4989.9, 2 , 0 , 0 , 0 ,,
     1.5     1.5
    26.8   48.32
     1.5     1.5
   26.46   47.98
Pier Skew, UpSta & Num, DnSta & Num=  ,5018.6, 2 ,5018.6, 2 , 0 , 0 , 0 ,,
     1.5     1.5
   27.23   48.37
     1.5     1.5
   26.89   48.03
Pier Skew, UpSta & Num, DnSta & Num=  ,5045.8, 2 ,5045.8, 2 , 0 , 0 , 0 ,,
     1.5     1.5
   35.47   48.32
     1.5     1.5
   35.13   47.98
Abutment Skew #Up #Dn= , 2 , 2
 4934.77 4936.53
   47.05   44.53
 4934.77 4936.53
   46.71   44.19
Abutment Skew #Up #Dn= , 2 , 2
 5066.58 5067.74
   44.78   47.29
 5066.58 5067.74
   44.44   46.95
BR Coef= 1 , 1 , 0 ,1.25, 0 ,,,.8,0,2,0,
WSPro=,,,, 1 ,,,, 0 ,,,, 0 ,,,,-1 ,-1 ,-1 , 0 , 0 , 0 , 0 , 0
BR U #Sta/Elev= 116
  3525.5    53.2  3605.5    52.6  3615.5    51.9  3635.5      52  3695.5      50
  3705.5      50  3735.5    51.3  3755.5    51.4  3795.5    49.5  3805.5    49.4
  3865.5    51.6  4161.2   51.01  4218.2    50.9  4308.2    49.8  4326.8   48.81
  4338.2    48.2  4367.7   48.15  4496.8   47.91  4566.8   47.78  4586.8   47.75
  4606.8   47.71  4612.4    47.7  4702.7    47.2 4756.95    46.9  4769.8   47.16
 4807.63   47.93  4826.5   48.09 4858.96   48.37 4894.96   48.33  4918.7   48.11
 4920.69   48.09  4920.8   48.09 4920.91   48.09 4934.24   47.97 4934.88   47.01
 4934.97   46.87 4936.43   44.68 4936.53   44.53 4950.14   42.11 4962.53   37.38
  4981.3   28.43 4989.91   27.79 4991.96   27.81 5001.39   28.12  5003.8   27.93
 5011.23   27.34  5018.7   28.34 5034.03    32.5 5045.84   36.74 5057.32   42.28
 5066.58   44.78 5067.54   45.03 5067.65   45.06  5072.4   46.34 5079.95   48.38
 5088.69   48.45  5088.8   48.45 5088.91   48.45 5127.18   48.76  5148.4   48.54
 5175.73   48.26  5224.5   48.44  5228.7   48.46 5254.12   48.24  5319.5   49.07
  5361.3    49.6  5394.2   49.73  5461.3      50  5491.3    49.3  5611.3    49.8
  5641.3    50.3  5671.3    50.3  5681.3    50.9  5791.3    49.5  5801.3      50
  5851.3    50.1  5861.3    50.5  5891.3    49.8  5941.3    50.5  5951.3    50.2
  6001.3    51.1  6091.3    50.3  6291.3    50.2  6311.3    49.4    6361    50.1
  6361.3    50.1  6371.3    50.6  6431.3      51  6441.3    50.5  6531.3    50.4
  6541.3    50.1  6551.3    50.5  6601.3    50.2  6611.3    49.6  6621.3    49.6
  6661.3    50.6  6671.3    49.9  6691.3    49.8  6701.3    50.6  6711.3      51
  6751.3    51.4  6771.3    50.9  6861.3    51.8  6871.3    52.4  6891.3    52.3
  6901.3    52.1  7031.3    51.1  7081.3    52.4  7231.3    53.8  7261.3    52.9
  7381.3    53.4  7421.3    54.5  7441.3    54.2  7471.3    54.9  7481.3    54.3
  7666.8    56.4
BR U #Mann= 6
  3525.5      .2  4161.2      .1  4367.7     .14 4950.14    .045 5057.32     .14
    6361      .1
BR U Banks=4950.14,5057.32
BR D #Sta/Elev= 116
  3525.5   52.86  3605.5   52.26  3615.5   51.56  3635.5   51.66  3695.5   49.66
  3705.5   49.66  3735.5   50.96  3755.5   51.06  3795.5   49.16  3805.5   49.06
  3865.5   51.26  4161.2   50.67  4218.2   50.56  4308.2   49.46  4326.8   48.47
  4338.2   47.86  4367.7   47.81  4496.8   47.57  4566.8   47.44  4586.8   47.41
  4606.8   47.37  4612.4   47.36  4702.7   46.86 4756.95   46.56  4769.8   46.82
 4807.63   47.59  4826.5   47.75 4858.96   48.03 4894.96   47.99  4918.7   47.77
 4920.69   47.75  4920.8   47.75 4920.91   47.75 4934.24   47.63 4934.88   46.67
 4934.97   46.53 4936.43   44.34 4936.53   44.19 4950.14   41.77 4962.53   37.04
  4981.3   28.09 4989.91   27.45 4991.96   27.47 5001.39   27.78  5003.8   27.59
 5011.23      27  5018.7      28 5034.03   32.16 5045.84    36.4 5057.32   41.94
 5066.58   44.44 5067.54   44.69 5067.65   44.72  5072.4      46 5079.95   48.04
 5088.69   48.11  5088.8   48.11 5088.91   48.11 5127.18   48.42  5148.4    48.2
 5175.73   47.92  5224.5    48.1  5228.7   48.12 5254.12    47.9  5319.5   48.73
  5361.3   49.26  5394.2   49.39  5461.3   49.66  5491.3   48.96  5611.3   49.46
  5641.3   49.96  5671.3   49.96  5681.3   50.56  5791.3   49.16  5801.3   49.66
  5851.3   49.76  5861.3   50.16  5891.3   49.46  5941.3   50.16  5951.3   49.86
  6001.3   50.76  6091.3   49.96  6291.3   49.86  6311.3   49.06    6361   49.76
  6361.3   49.76  6371.3   50.26  6431.3   50.66  6441.3   50.16  6531.3   50.06
  6541.3   49.76  6551.3   50.16  6601.3   49.86  6611.3   49.26  6621.3   49.26
  6661.3   50.26  6671.3   49.56  6691.3   49.46  6701.3   50.26  6711.3   50.66
  6751.3   51.06  6771.3   50.56  6861.3   51.46  6871.3   52.06  6891.3   51.96
  6901.3   51.76  7031.3   50.76  7081.3   52.06  7231.3   53.46  7261.3   52.56
  7381.3   53.06  7421.3   54.16  7441.3   53.86  7471.3   54.56  7481.3   53.96
  7666.8   56.06
BR D #Mann= 6
  3525.5      .2  4161.2      .1  4367.7     .14 4950.14    .045 5057.32     .14
    6361      .1
BR D Banks=4950.14,5057.32
BC Design=,, 0 ,, 0 ,,,,,,

Type RM Length L Ch R = 1 ,29704.8 ,721.1,721.1,721.1
BEGIN DESCRIPTION:
Downstream Section of Bridge/Culvert/Weir
END DESCRIPTION:
XS GIS Cut Line= 6
      3140568.74     13878262.24      3140307.54     13877853.55
      3139289.26     13877367.27      3139201.31     13877329.68
      3139017.77     13877311.93      3136771.25     13877236.36
#Sta/Elev= 30
  3525.5   52.86  3695.5   49.66  3755.5   51.06  3805.5   49.06  3865.5   51.26
  4161.2   50.67  4367.7   47.81 4756.95   46.56 4934.24   47.63 4936.53   44.19
 4950.14   41.77  4981.3   28.09 5011.23      27 5034.03   32.16 5057.32   41.94
 5079.95   48.04 5127.18   48.42 5254.12    47.9  5681.3   50.56  5791.3   49.16
  6001.3   50.76    6361   49.76  6431.3   50.66  6691.3   49.46  6711.3   50.66
  6871.3   52.06  7031.3   50.76  7231.3   53.46  7381.3   53.06  7666.8   56.06
#Mann= 6 , 1 , 0
  3525.5      .2       0  4161.2      .1       0  4367.7     .14       0
 4950.14    .045       0 5057.32     .14       0    6361      .1       0
#XS Ineff= 2 , 0
       0    4925      47    5078       0    48.1
Permanent Ineff=
       F       F
Bank Sta=4950.14,5057.32
XS Rating Curve= 0
Exp/Cntr=.5,.3

Type RM Length L Ch R = 1 ,28983.7 ,467.6,596.4,749.8
BEGIN DESCRIPTION:
Cross Section 28983.7
END DESCRIPTION:
XS GIS Cut Line= 5
      3140280.76     13877761.28      3140188.68     13877024.63
      3139987.77     13876899.06       3139719.9     13876882.32
      3138320.21     13876854.14
#Sta/Elev= 30
  3912.1    51.8  4002.1    49.7  4092.1    49.1  4572.1    49.5  4714.5    48.4
  4814.5    48.7  4864.5    50.6  4891.4    49.4  4940.5    41.3  4962.8   39.73
  4980.5   32.76  4984.4   27.69  4985.8   26.97  5011.1   26.97  5015.5   27.75
  5032.6   40.66  5039.1   41.25  5054.6   46.64  5159.8      47  5239.8    48.5
  5269.8    48.2  5309.8    50.5  5559.8    50.9  5609.8    52.1  5659.8    51.1
  5789.8    50.9  6069.8    51.6  6229.8    52.9  6529.8    52.9  6559.8      54
#Mann= 4 , 1 , 0
  3912.1      .2       0  3912.1     .14       0  4940.5    .045       0
  5032.6     .14       0
#XS Ineff= 2 , 0
       0                  5609.8       0    52.1
Permanent Ineff=
       F       F
Bank Sta=4940.5,5032.6
XS Rating Curve= 0
Exp/Cntr=.3,.1

Type RM Length L Ch R = 1 ,28387.3 ,216.7,395.3,477.5
BEGIN DESCRIPTION:
Cross Section 28387.3-Interpolated
END DESCRIPTION:
XS GIS Cut Line= 5
      3140336.92     13877757.46      3140270.44     13876813.44
      3140046.42     13876426.51      3139686.65     13876168.56
      3138763.45     13875639.08
#Sta/Elev= 30
  3414.6    51.2  3744.6    47.6  4234.6    49.1  4294.6    47.7  4420.9    49.9
  4560.9    47.8  4630.9    50.8  4800.9    47.9    4838    49.6    4918    45.9
    4949   37.84  4975.1   32.71  4986.1    28.8  4988.7   26.26  4994.4   26.04
  5010.2   26.91  5021.9   29.87    5038    29.6    5068    40.6    5128    42.5
    5168    49.6    5198    51.9  5250.7    50.2  5410.7    50.9  5480.7    53.2
  5729.7   52.73  5930.7      52  6090.7    54.3  6200.7    52.7    6315    55.4
#Mann= 5 , 1 , 0
  3414.6     .14       0    4949    .045       0    5068     .14       0
  5729.7      .1       0    6315      .2       0
#XS Ineff= 2 , 0
       0  4610.9    49.3    5198       0    51.9
Permanent Ineff=
       F       F
Bank Sta=4949,5068
XS Rating Curve= 0
Exp/Cntr=.3,.1

Type RM Length L Ch R = 1 ,27992.0 ,433.6,424.3,420.5
BEGIN DESCRIPTION:
Cross Section 27992.0
END DESCRIPTION:
XS GIS Cut Line= 6
      3140386.17     13877612.43      3140448.95      13877084.4
      3140402.41     13876700.45      3140248.25     13876444.48
      3140271.52     13876127.43      3139852.26     13875636.26
#Sta/Elev= 30
  3599.2      51  3773.1    50.4  3853.1    48.6  3983.1      50  4403.1   48.17
  4441.1    49.9  4557.8      48  4667.8      48  4697.8    45.9  4737.8    45.2
  4787.8    41.8  4862.9   39.42    4906   40.44    4949   37.22  4975.1   32.09
  4986.1   28.18  4988.7   25.64  4994.4   25.42  5010.2   26.29  5012.2   26.72
  5012.4   27.62  5021.9   29.25  5046.5   41.73  5095.2   41.19    5127   48.93
  5174.5    49.9  5254.5    48.7  5368.5   49.91  5624.7    50.7  5794.7    52.9
#Mann= 6 , 1 , 0
  3599.2      .1       0  4403.1     .14       0    4949    .045       0
  5046.5     .14       0    5127      .1       0  5368.5     .14       0
#XS Ineff= 2 , 0
       0  3983.1      50               0
Permanent Ineff=
       F       F
Bank Sta=4949,5046.5
XS Rating Curve= 0
Exp/Cntr=.3,.1

Type RM Length L Ch R = 1 ,27567.7 ,256.1,250.7,249.6
BEGIN DESCRIPTION:
Cross Section 27567.7-Interpolated
END DESCRIPTION:
XS GIS Cut Line= 5
      3140691.31     13877784.16      3140677.73     13876535.12
      3140684.52     13876127.83      3140677.73     13875401.49
      3140494.45     13875055.29
#Sta/Elev= 30
    3531    51.2  4632.4      47    4671    46.1    4721    47.6    4751    45.9
  4800.1    47.1  4850.1    45.3  4890.1    39.2  4930.1      41 4951.13   37.46
 4980.73   26.97 4998.23   25.74 5019.33   27.07 5048.93   36.84  5060.1    38.2
  5080.1    42.8  5120.1    42.1  5140.1    42.9  5150.1    43.8  5170.1    49.2
    5190   49.61  5407.5    48.7  5517.5    50.2  5617.5      49  5637.5    49.8
  6003.8      50  6023.8    48.5  6223.8    49.3  6263.8    51.7  6305.6    52.3
#Mann= 7 , 1 , 0
    3531      .2       0    3531      .1       0  4632.4     .14       0
 4951.13    .045       0 5048.93     .14       0    5190      .1       0
  6305.6      .2       0
#XS Ineff= 2 , 0
       0                  5257.5       0      50
Permanent Ineff=
       F       F
Bank Sta=4951.13,5048.93
XS Rating Curve= 0
Exp/Cntr=.5,.3