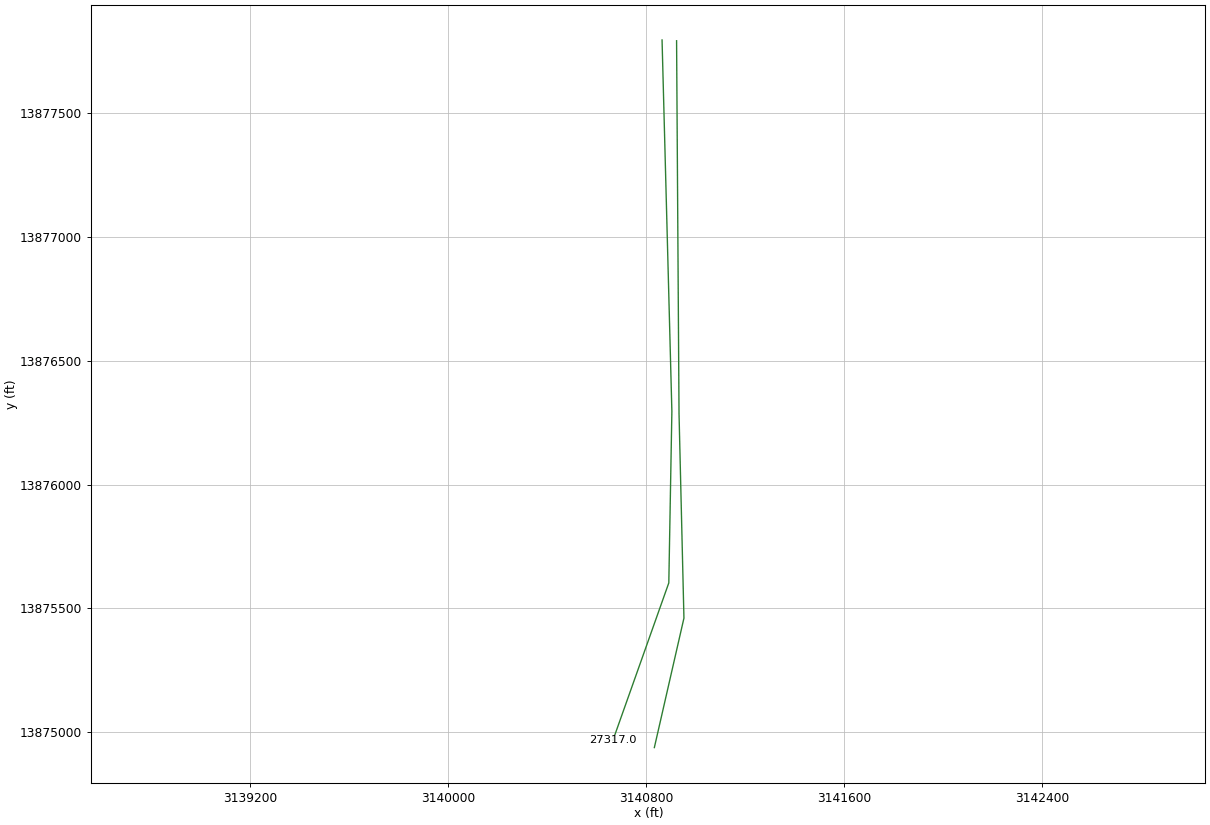
HEC-RAS study P118-00-00.PRJ: P118-00-00

--- P118-00-00.g01 (geometry) --- (continued)

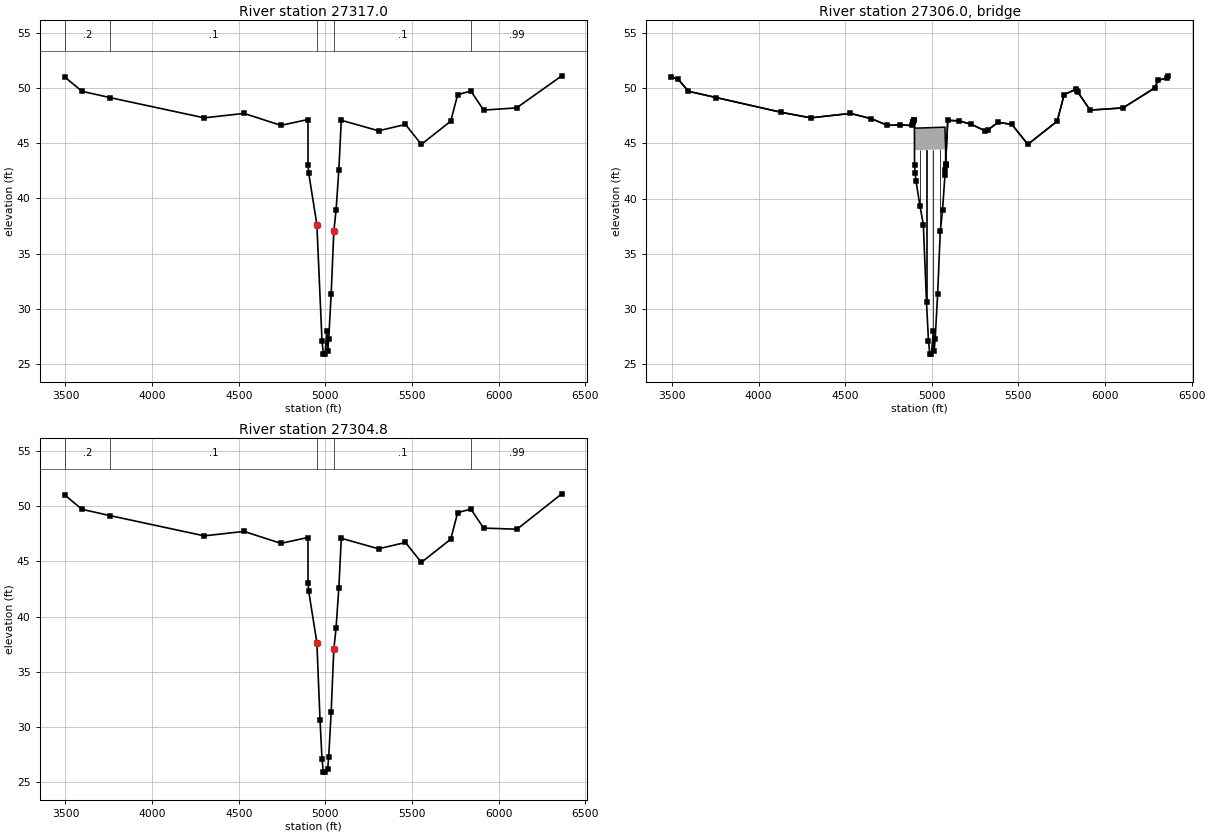
Type RM Length L Ch R = 1 ,27317.0 ,12.2,12.2,12.2
BEGIN DESCRIPTION:
Upstream Section of Bridge/Culvert/Weir
END DESCRIPTION:
XS GIS Cut Line= 4
      3140865.22     13877796.16      3140904.91     13876295.13
       3140892.5     13875602.56      3140666.58     13874966.11
#Sta/Elev= 30
  3495.3   50.99  3595.3   49.69  3757.1   49.12  4300.7   47.29  4530.7   47.69
 4743.83   46.61 4899.73   47.14 4900.33   43.02 4904.23   42.27 4951.13   37.64
 4980.73   27.15 4988.43   25.94 4998.23   25.92 5009.03   28.05 5013.43   26.23
 5019.33   27.25 5033.73   31.35 5048.93   37.02 5061.83   38.92 5078.03   42.58
 5092.13   47.07 5307.03   46.12  5462.6   46.69  5554.3   44.89  5723.9   46.99
  5763.9   49.39    5840   49.71  5913.9   47.99  6103.9   48.19  6364.9   51.09
#Mann= 5 , 1 , 0
  3495.3      .2       0  3757.1      .1       0 4951.13    .045       0
 5048.93      .1       0    5840     .99       0
#XS Ineff= 2 , 0
       0    4890    45.4    5090       0    45.2
Permanent Ineff=
       F       F
Bank Sta=4951.13,5048.93
XS Rating Curve= 0
Exp/Cntr=.5,.3

Type RM Length L Ch R = 3 ,27306.0 ,,,
BEGIN DESCRIPTION:
24" PIPELINE
END DESCRIPTION:
Bridge Culvert--1,0,-1,-1, 0
Deck Dist Width WeirC Skew NumUp NumDn MinLoCord MaxHiCord MaxSubmerge Is_Ogee
10,2,2.6,0, 55, 55, , , .95, 0, 1,1,,
  3495.3  3535.3  3595.3  3757.1  4130.7  4300.7  4530.7 4651.73 4743.83 4816.03
 4885.33 4893.53 4893.64 4893.73 4897.73 4899.73 4900.33 4904.23 4909.43 4931.83
 4951.13 4969.43 4980.73 4988.43 4998.23 5009.03 5013.43 5019.33 5033.73 5048.93
 5061.83 5076.03 5078.03 5079.42 5079.53 5079.63 5092.13 5159.83 5228.63 5307.03
 5326.93  5382.6  5462.6  5554.3  5723.9  5763.9  5833.9    5840  5843.9  5913.9
  6103.9  6286.5  6306.5  6356.5  6364.9
      51    50.8    49.7   49.13    47.8    47.3    47.7   47.22   46.62   46.66
   46.61   46.93   46.93   46.94   47.09   47.16   46.36   46.36   46.37   46.38
   46.39    46.4   46.41   46.41   46.42   46.42   46.42   46.43   46.44   46.44
   46.45   46.46   45.33   44.55   44.49    43.1   47.08   47.02   46.71   46.13
   46.24    46.9    46.7    44.9      47    49.4    49.9   49.72    49.6      48
    48.2      50    50.7    50.9    51.1
      51    50.8    49.7   49.13    47.8    47.3    47.7   47.22   46.62   46.66
   46.61   46.92   46.92   46.93   47.08   47.15   44.36   44.36   44.37   44.38
   44.39    44.4   44.41   44.41   44.42   44.42   44.42   44.43   44.44   44.44
   44.45   44.46   43.33   43.03   43.07    43.1   47.08   47.02   46.71   46.13
   46.24    46.9    46.7    44.9      47    49.4    49.9   49.72    49.6      48
    48.2      50    50.7    50.9    51.1
  3495.3  3535.3  3595.3  3757.1  4130.7  4300.7  4530.7 4651.73 4743.83 4816.03
 4885.33 4893.53 4893.64 4893.73 4897.73 4899.73 4900.33 4904.23 4909.43 4931.83
 4951.13 4969.43 4980.73 4988.43 4998.23 5009.03 5013.43 5019.33 5033.73 5048.93
 5061.83 5076.03 5078.03 5079.42 5079.53 5079.63 5092.13 5159.83 5228.63 5307.03
 5326.93  5382.6  5462.6  5554.3  5723.9  5763.9  5833.9    5840  5843.9  5913.9
  6103.9  6286.5  6306.5  6356.5  6364.9
      51    50.8    49.7   49.13    47.8    47.3    47.7   47.22   46.62   46.66
   46.61   46.93   46.93   46.94   47.09   47.16   46.36   46.36   46.37   46.38
   46.39    46.4   46.41   46.41   46.42   46.42   46.42   46.43   46.44   46.44
   46.45   46.46   45.33   44.55   44.49    43.1   47.08   47.02   46.71   46.13
   46.24    46.9    46.7    44.9      47    49.4    49.9   49.72    49.6      48
    48.2      50    50.7    50.9    51.1
      51    50.8    49.7   49.13    47.8    47.3    47.7   47.22   46.62   46.66
   46.61   46.92   46.92   46.93   47.08   47.15   44.36   44.36   44.37   44.38
   44.39    44.4   44.41   44.41   44.42   44.42   44.42   44.43   44.44   44.44
   44.45   44.46   43.33   43.03   43.07    43.1   47.08   47.02   46.71   46.13
   46.24    46.9    46.7    44.9      47    49.4    49.9   49.72    49.6      48
    48.2      50    50.7    50.9    51.1
Pier Skew, UpSta & Num, DnSta & Num=  ,4931.8, 2 ,4931.8, 2 , 0 , 0 , 0 ,,
     1.5     1.5
   38.25   45.38
     1.5     1.5
   38.25   45.38
Pier Skew, UpSta & Num, DnSta & Num=  ,4969.4, 2 ,4969.4, 2 , 0 , 0 , 0 ,,
     1.5     1.5
   29.41    45.4
     1.5     1.5
   29.41    45.4
Pier Skew, UpSta & Num, DnSta & Num=  ,5009, 2 ,5009, 2 , 0 , 0 , 0 ,,
     1.5     1.5
   26.75   45.42
     1.5     1.5
   26.75   45.42
Pier Skew, UpSta & Num, DnSta & Num=  ,5048.9, 2 ,5048.9, 2 , 0 , 0 , 0 ,,
     1.5     1.5
   35.75   45.44
     1.5     1.5
   35.75   45.44
BR Coef= 1 , 1 , 0 ,1.25, 0 ,,,.8,0,2,0,
WSPro=,,,, 1 ,,,, 0 ,,,, 0 ,,,,-1 ,-1 ,-1 , 0 , 0 , 0 , 0 , 0
BR U #Sta/Elev= 55
  3495.3      51  3535.3    50.8  3595.3    49.7  3757.1   49.13  4130.7    47.8
  4300.7    47.3  4530.7    47.7 4651.73   47.22 4743.83   46.62 4816.03   46.66
 4885.33   46.61 4893.53   46.92 4893.64   46.92 4893.73   46.93 4897.73   47.08
 4899.73   47.15 4900.33   43.03 4904.23   42.28 4909.43   41.55 4931.83   39.31
 4951.13   37.65 4969.43   30.64 4980.73   27.16 4988.43   25.95 4998.23   25.93
 5009.03   28.06 5013.43   26.24 5019.33   27.26 5033.73   31.36 5048.93   37.03
 5061.83   38.93 5076.03   42.14 5078.03   42.59 5079.42   43.03 5079.53   43.07
 5079.63    43.1 5092.13   47.08 5159.83   47.02 5228.63   46.71 5307.03   46.13
 5326.93   46.24  5382.6    46.9  5462.6    46.7  5554.3    44.9  5723.9      47
  5763.9    49.4  5833.9    49.9    5840   49.72  5843.9    49.6  5913.9      48
  6103.9    48.2  6286.5      50  6306.5    50.7  6356.5    50.9  6364.9    51.1
BR U #Mann= 5
  3495.3      .2  3757.1      .1 4951.13    .045 5048.93      .1    5840     .99
BR U Banks=4951.13,5048.93
BR D #Sta/Elev= 55
  3495.3      51  3535.3    50.8  3595.3    49.7  3757.1   49.13  4130.7    47.8
  4300.7    47.3  4530.7    47.7 4651.73   47.22 4743.83   46.62 4816.03   46.66
 4885.33   46.61 4893.53   46.92 4893.64   46.92 4893.73   46.93 4897.73   47.08
 4899.73   47.15 4900.33   43.03 4904.23   42.28 4909.43   41.55 4931.83   39.31
 4951.13   37.65 4969.43   30.64 4980.73   27.16 4988.43   25.95 4998.23   25.93
 5009.03   28.06 5013.43   26.24 5019.33   27.26 5033.73   31.36 5048.93   37.03
 5061.83   38.93 5076.03   42.14 5078.03   42.59 5079.42   43.03 5079.53   43.07
 5079.63    43.1 5092.13   47.08 5159.83   47.02 5228.63   46.71 5307.03   46.13
 5326.93   46.24  5382.6    46.9  5462.6    46.7  5554.3    44.9  5723.9      47
  5763.9    49.4  5833.9    49.9    5840   49.72  5843.9    49.6  5913.9      48
  6103.9    48.2  6286.5      50  6306.5    50.7  6356.5    50.9  6364.9    51.1
BR D #Mann= 5
  3495.3      .2  3757.1      .1 4951.13    .045 5048.93      .1    5840     .99
BR D Banks=4951.13,5048.93
BC Design=,, 0 ,, 0 ,,,,,,

Type RM Length L Ch R = 1 ,27304.8 ,124,124,124
BEGIN DESCRIPTION:
Upstream Section of Bridge/Culvert/Weir
END DESCRIPTION:
XS GIS Cut Line= 4
      3140923.91     13877792.93      3140933.77     13876286.76
      3140953.63     13875460.15      3140834.07     13874937.09
#Sta/Elev= 30
  3495.3      51  3595.3    49.7  3757.1   49.13  4300.7    47.3  4530.7    47.7
  4743.8   46.62  4899.6   47.15  4900.3   43.03  4904.2   42.28  4951.1   37.65
  4969.4   30.64  4980.7   27.16  4988.4   25.95    4996   25.93  5013.4   26.24
  5019.3   27.26  5033.7   31.36  5048.9   37.03  5061.8   38.93    5078   42.59
  5092.1   47.08    5307   46.13  5462.6    46.7  5554.3    44.9  5723.9      47
  5763.9    49.4    5840   49.72  5913.9      48  6106.5    47.9  6364.9    51.1
#Mann= 5 , 1 , 0
  3495.3      .2       0  3757.1      .1       0  4951.1    .045       0
  5048.9      .1       0    5840     .99       0
#XS Ineff= 2 , 0
       0    4890    46.5    5090       0    45.2
Permanent Ineff=
       F       F
Bank Sta=4951.1,5048.9
XS Rating Curve= 0
Exp/Cntr=.5,.3