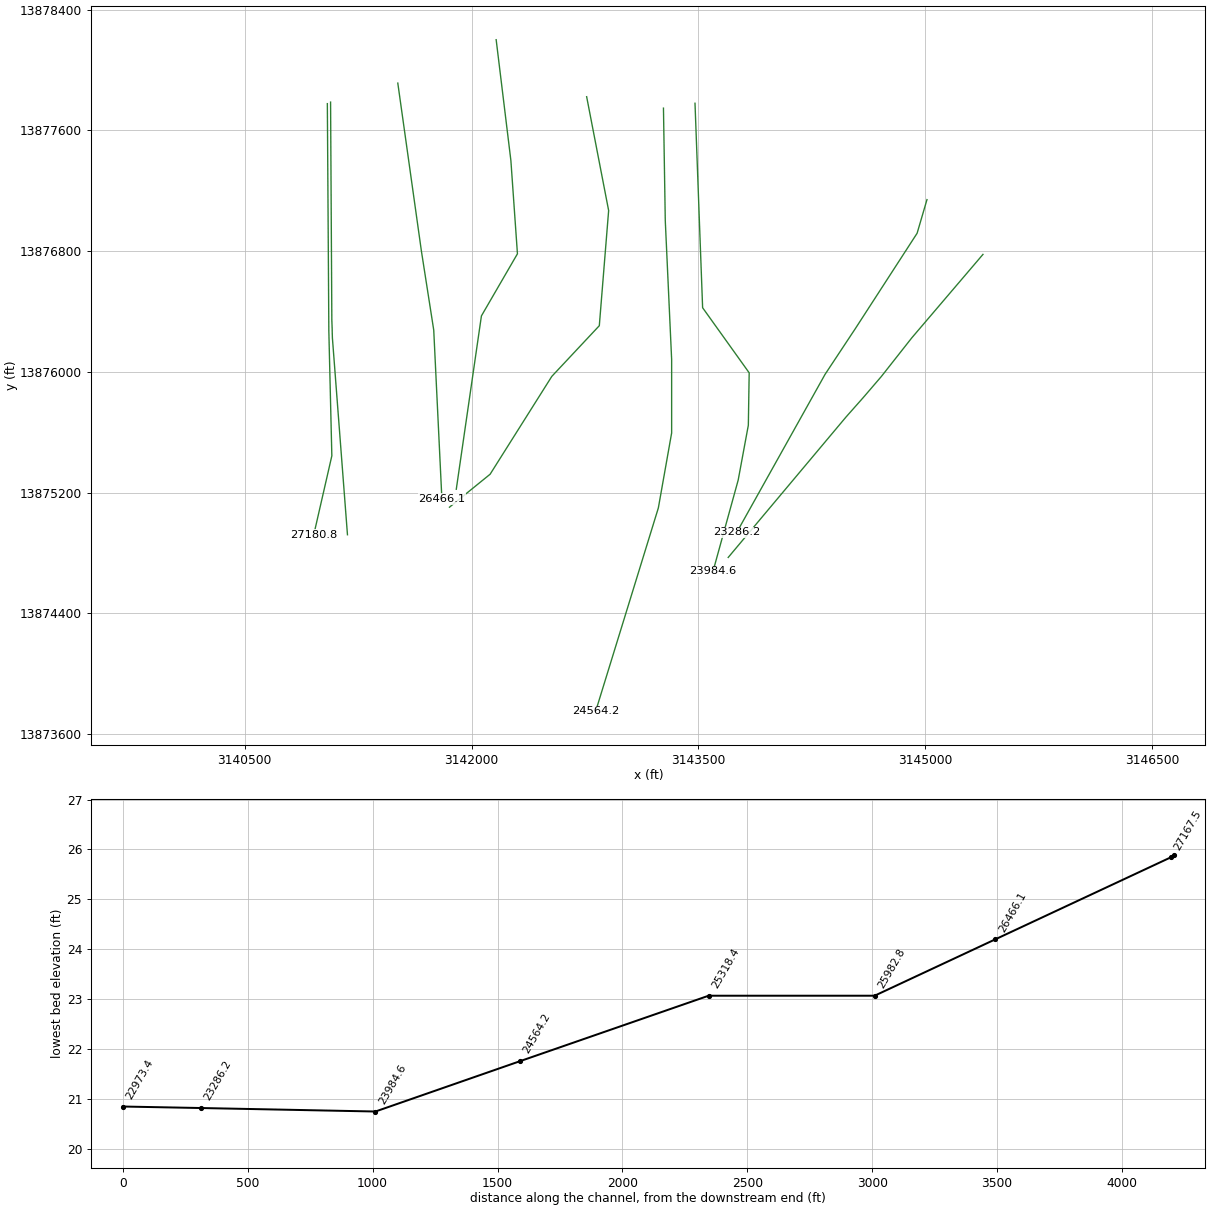
HEC-RAS study P118-00-00.PRJ: P118-00-00

--- P118-00-00.g01 (geometry) --- (continued)

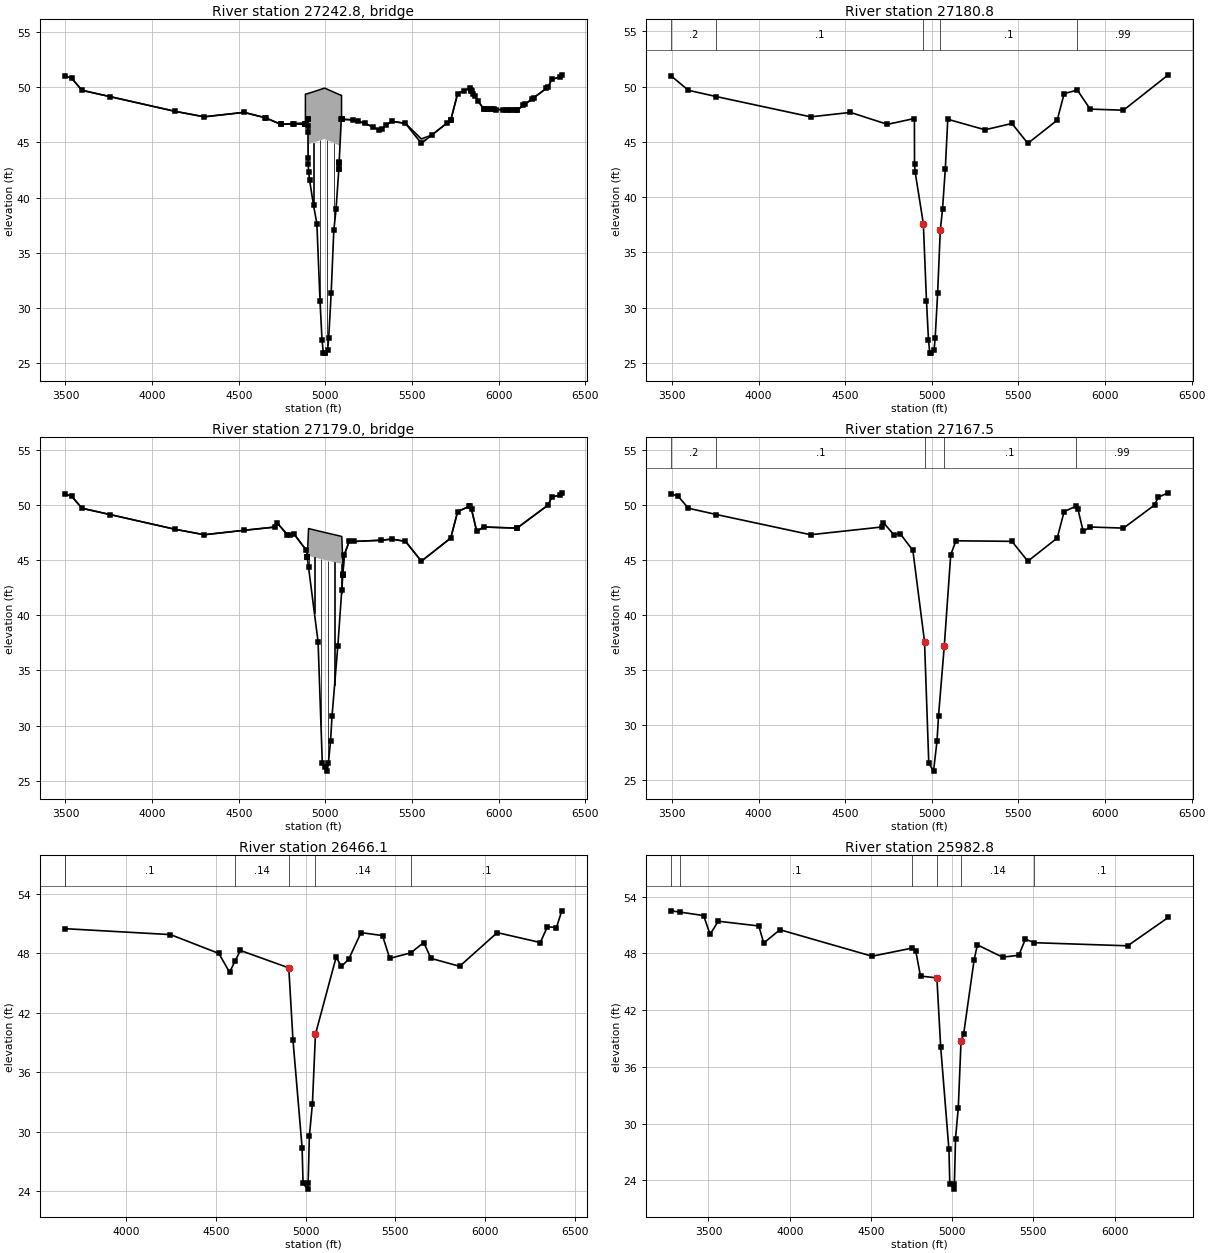
Type RM Length L Ch R = 3 ,27242.8 ,,,
BEGIN DESCRIPTION:
HOMESTEAD ROAD
Structure ID: P18-07
END DESCRIPTION:
Bridge Culvert--1,0,-1,-1, 0
Deck Dist Width WeirC Skew NumUp NumDn MinLoCord MaxHiCord MaxSubmerge Is_Ogee
10,104,2.6,0, 37, 36, , , .95, 0, 1,1,,
  3495.3  3535.3  3595.3  4130.7  4300.7  4530.7  4651.7  4743.8 4884.89    4885
  4899.6  4899.8  4900.2    4996 5079.69  5079.8  5092.1  5093.6 5093.71  5159.8
  5228.6    5307  5326.9  5382.6  5462.6  5554.3  5614.7  5723.9  5763.9  5833.9
  5843.9  5913.9  6106.5  6286.5  6306.5  6356.5  6364.9
      51    50.8    49.7   47.81   47.31   47.71   47.23   46.63   46.76   49.36
    49.4    49.4   49.41    49.9   49.32   49.32   49.25   49.24   47.09   47.03
   46.72   46.14   46.25   46.91   46.71   45.31   45.66   47.01   49.41   49.91
   49.61   48.01   47.91      50    50.7    50.9    51.1
      51    50.8    49.7    47.8    47.3    47.7   47.22   46.62   46.61   46.61
   47.15   45.97   44.81    45.3   44.72   43.16   47.08   47.08   47.08   47.02
   46.71   46.13   46.24    46.9    46.7    44.9   45.65      47    49.4    49.9
    49.6      48    47.9      50    50.7    50.9    51.1
  3495.3  3535.3  3595.3  4130.7  4300.7  4530.7  4651.7  4743.8 4884.89    4885
  4899.6  4899.8  4900.2    4996 5079.69  5079.8  5092.1  5093.6 5093.71  5159.8
  5228.6    5307  5326.9  5382.6  5462.6  5554.3  5723.9  5763.9  5833.9  5843.9
  5913.9  6106.5  6286.5  6306.5  6356.5  6364.9
   51.38   51.18   50.08   48.18   47.68   48.08    47.6      47   46.99   49.36
    49.4    49.4   49.41    49.9   49.32   49.32   49.25   49.24   47.46    47.4
   47.09   46.51   46.62   47.28   47.08   45.31   47.38   49.78   50.28   49.98
   48.38   48.28   50.38   51.08   51.28   51.48
   51.38   51.18   50.08   48.18   47.68   48.08    47.6      47   46.99   46.99
   47.53   46.35   45.19   45.68    45.1   43.54   47.46   47.46   47.46    47.4
   47.09   46.51   46.62   47.28   47.08   45.28   47.38   49.78   50.28   49.98
   48.38   48.28   50.38   51.08   51.28   51.48
Pier Skew, UpSta & Num, DnSta & Num=  ,4901.7, 2 ,4901.7, 2 , 0 , 0 , 0 ,,
     1.5     1.5
   41.62   45.82
     1.5     1.5
      42    46.2
Pier Skew, UpSta & Num, DnSta & Num=  ,4931.8, 2 ,4931.8, 2 , 0 , 0 , 0 ,,
     1.5     1.5
   38.25   45.97
     1.5     1.5
   38.63   46.35
Pier Skew, UpSta & Num, DnSta & Num=  ,4969.4, 2 ,4969.4, 2 , 0 , 0 , 0 ,,
     1.5     1.5
   29.41   46.16
     1.5     1.5
   29.79   46.54
Pier Skew, UpSta & Num, DnSta & Num=  ,5009, 2 ,5009, 2 , 0 , 0 , 0 ,,
     1.5     1.5
   25.13   46.21
     1.5     1.5
   25.51   46.59
Pier Skew, UpSta & Num, DnSta & Num=  ,5048.9, 2 ,5048.9, 2 , 0 , 0 , 0 ,,
     1.5     1.5
   35.75   45.94
     1.5     1.5
   36.13   46.32
Abutment Skew #Up #Dn= , 2 , 2
    5078 5079.89
   42.59   44.72
    5078 5079.89
   42.97    45.1
BR Coef= 1 , 1 , 0 ,1.25, 0 ,,,.8,0,2,0,
WSPro=,,,, 1 ,,,, 0 ,,,, 0 ,,,,-1 ,-1 ,-1 , 0 , 0 , 0 , 0 , 0
BR U #Sta/Elev= 92
  3495.3      51  3535.3    50.8  3595.3    49.7  3757.1   49.13  4130.7    47.8
  4300.7    47.3  4530.7    47.7  4651.7   47.22  4657.9   47.18  4741.7   46.63
  4743.8   46.62    4816   46.66  4818.9   46.66 4884.89   46.61    4885   46.61
 4885.11   46.61  4885.3   46.61  4899.2   47.13  4899.6   47.15 4899.71    46.5
  4899.8   45.97  4900.2   43.62  4900.3   43.03  4904.2   42.28  4909.4   41.55
  4931.8   39.31  4951.1   37.65  4969.4   30.64  4980.7   27.16  4988.4   25.95
    4996   25.93  4998.2   25.93  5013.4   26.24  5019.3   27.26  5033.7   31.36
  5048.9   37.03  5061.8   38.93  5077.9   42.57    5078   42.59 5079.69   43.13
  5079.8   43.16  5079.9    43.2  5092.1   47.08 5093.49   47.08  5093.6   47.08
 5093.71   47.08  5159.8   47.02  5190.7   46.88  5228.6   46.71    5275   46.37
    5307   46.13  5326.9   46.24  5352.4   46.54  5382.6    46.9  5462.6    46.7
  5554.3    44.9  5614.7   45.65  5704.7   46.76  5723.9      47  5724.7   47.05
  5763.9    49.4    5803   49.68  5833.9    49.9    5840   49.72    5843   49.63
  5843.9    49.6    5853   49.39    5863   49.16    5883   48.71    5913   48.02
  5913.9      48    5933   47.99    5943   47.98    5963   47.97    5973   47.97
    5983   47.96    6023   47.94    6043   47.93    6063   47.92    6073   47.92
    6093   47.91  6103.9    47.9  6106.5    47.9    6143   48.33    6153   48.44
    6193   48.91    6203   49.03  6275.4   49.87  6286.5      50  6306.5    50.7
  6356.5    50.9  6364.9    51.1
BR U #Mann= 5
  3495.3      .2  3757.1      .1  4951.1    .045  5048.9      .1    5840     .99
BR U Banks=4951.1,5048.9
BR D #Sta/Elev= 92
  3495.3   51.38  3535.3   51.18  3595.3   50.08  3757.1   49.51  4130.7   48.18
  4300.7   47.68  4530.7   48.08  4651.7    47.6  4657.9   47.56  4741.7   47.01
  4743.8      47    4816   47.04  4818.9   47.04 4884.89   46.99    4885   46.99
 4885.11   46.99  4885.3   46.99  4899.2   47.51  4899.6   47.53 4899.71   46.88
  4899.8   46.35  4900.2      44  4900.3   43.41  4904.2   42.66  4909.4   41.93
  4931.8   39.69  4951.1   38.03  4969.4   31.02  4980.7   27.54  4988.4   26.33
    4996   26.31  4998.2   26.31  5013.4   26.62  5019.3   27.64  5033.7   31.74
  5048.9   37.41  5061.8   39.31  5077.9   42.95    5078   42.97 5079.69   43.51
  5079.8   43.54  5079.9   43.58  5092.1   47.46 5093.49   47.46  5093.6   47.46
 5093.71   47.46  5159.8    47.4  5190.7   47.26  5228.6   47.09    5275   46.75
    5307   46.51  5326.9   46.62  5352.4   46.92  5382.6   47.28  5462.6   47.08
  5554.3   45.28  5614.7   46.03  5704.7   47.14  5723.9   47.38  5724.7   47.43
  5763.9   49.78    5803   50.06  5833.9   50.28    5840    50.1    5843   50.01
  5843.9   49.98    5853   49.77    5863   49.54    5883   49.09    5913    48.4
  5913.9   48.38    5933   48.37    5943   48.36    5963   48.35    5973   48.35
    5983   48.34    6023   48.32    6043   48.31    6063    48.3    6073    48.3
    6093   48.29  6103.9   48.28  6106.5   48.28    6143   48.71    6153   48.82
    6193   49.29    6203   49.41  6275.4   50.25  6286.5   50.38  6306.5   51.08
  6356.5   51.28  6364.9   51.48
BR D #Mann= 5
  3495.3      .2  3757.1      .1  4951.1    .045  5048.9      .1    5840     .99
BR D Banks=4951.1,5048.9
BC Design=,, 0 ,, 0 ,,,,,,

Type RM Length L Ch R = 1 ,27180.8 ,13.3,13.3,13.3
BEGIN DESCRIPTION:
Downstream Section of Bridge/Culvert/Weir
END DESCRIPTION:
XS GIS Cut Line= 4
      3141046.89     13877777.06      3141056.75     13876270.88
      3141076.61     13875444.27      3140957.05     13874921.22
#Sta/Elev= 30
  3495.3   50.96  3595.3   49.66  3757.1   49.09  4300.7   47.26  4530.7   47.66
  4743.8   46.58  4899.6   47.11  4900.3   42.99  4904.2   42.24  4951.1   37.61
  4969.4    30.6  4980.7   27.12  4988.4   25.91    4996   25.89  5013.4    26.2
  5019.3   27.22  5033.7   31.32  5048.9   36.99  5061.8   38.89    5078   42.55
  5092.1   47.04    5307   46.09  5462.6   46.66  5554.3   44.86  5723.9   46.96
  5763.9   49.36    5840   49.68  5913.9   47.96  6106.5   47.86  6364.9   51.06
#Mann= 5 , 1 , 0
  3495.3      .2       0  3757.1      .1       0  4951.1    .045       0
  5048.9      .1       0    5840     .99       0
#XS Ineff= 2 , 0
       0    4890    46.5    5090       0    45.2
Permanent Ineff=
       F       F
Bank Sta=4951.1,5048.9
XS Rating Curve= 0
Exp/Cntr=.5,.3

Type RM Length L Ch R = 3 ,27179.0 ,,,
BEGIN DESCRIPTION:
30" PIPELINE
END DESCRIPTION:
Bridge Culvert--1,0,-1,-1, 0
Deck Dist Width WeirC Skew NumUp NumDn MinLoCord MaxHiCord MaxSubmerge Is_Ogee
10,3,2.6,0, 49, 49, , , .95, 0, 1,1,,
  3495.3  3535.3  3595.3  3757.1  4130.7  4300.7  4530.7  4710.7  4720.7  4780.7
  4794.4 4818.46 4890.66 4895.36 4895.47 4895.56 4903.26 4958.06 4982.56 4995.36
 5010.06 5017.46 5030.26 5038.86 5072.26 5095.06 5101.05 5101.16 5101.26 5109.16
 5139.06 5166.76  5322.1  5382.6  5462.6  5554.3  5723.9  5763.9    5830  5833.9
  5843.9  5873.9  5913.9  6103.9  6106.5  6286.5  6306.5  6356.5  6364.9
   51.01   50.81   49.71   49.14   47.81   47.31   47.71   48.01   48.41   47.31
   47.31   47.39   45.89   45.31    45.3   45.29   47.87   47.66   47.57   47.52
   47.47   47.44   47.39   47.36   47.24   47.15   44.85   44.81   43.72   45.48
   46.76    46.7   46.81   46.91   46.71   44.91   47.01   49.41   49.88   49.91
   49.61   47.61   48.01   47.91   47.91   50.01   50.71   50.91   51.11
   51.01   50.81   49.71   49.14   47.81   47.31   47.71   48.01   48.41   47.31
   47.31   47.39   45.89   45.31    45.3   45.29   45.38   45.17   45.08   45.03
   44.98   44.95    44.9   44.87   44.75   44.66   43.67    43.7   43.72   45.48
   46.76    46.7   46.81   46.91   46.71   44.91   47.01   49.41   49.88   49.91
   49.61   47.61   48.01   47.91   47.91   50.01   50.71   50.91   51.11
  3495.3  3535.3  3595.3  3757.1  4130.7  4300.7  4530.7  4710.7  4720.7  4780.7
  4794.4 4818.46 4890.66 4895.36 4895.47 4895.56 4903.26 4958.06 4982.56 4995.36
 5010.06 5017.46 5030.26 5038.86 5072.26 5095.06 5101.05 5101.16 5101.26 5109.16
 5139.06 5166.76  5322.1  5382.6  5462.6  5554.3  5723.9  5763.9    5830  5833.9
  5843.9  5873.9  5913.9  6103.9  6106.5  6286.5  6306.5  6356.5  6364.9
      51    50.8    49.7   49.13    47.8    47.3    47.7      48    48.4    47.3
    47.3   47.38   45.88   45.31    45.3   45.29   47.87   47.66   47.57   47.52
   47.47   47.44   47.39   47.36   47.24   47.15   44.85   44.81   43.71   45.47
   46.75   46.69    46.8    46.9    46.7    44.9      47    49.4   49.87    49.9
    49.6    47.6      48    47.9    47.9      50    50.7    50.9    51.1
      51    50.8    49.7   49.13    47.8    47.3    47.7      48    48.4    47.3
    47.3   47.38   45.88    45.3   45.29   45.28   45.37   45.16   45.07   45.02
   44.97   44.94   44.89   44.86   44.74   44.65   43.66   43.69   43.71   45.47
   46.75   46.69    46.8    46.9    46.7    44.9      47    49.4   49.87    49.9
    49.6    47.6      48    47.9    47.9      50    50.7    50.9    51.1
Pier Skew, UpSta & Num, DnSta & Num=  ,4903.6, 2 ,4903.6, 2 , 0 , 0 , 0 ,,
     1.5     1.5
   43.21   46.38
     1.5     1.5
    43.2   46.37
Pier Skew, UpSta & Num, DnSta & Num=  ,4937.2, 2 ,4937.2, 2 , 0 , 0 , 0 ,,
     1.5     1.5
   39.08   46.25
     1.5     1.5
   39.07   46.24
Pier Skew, UpSta & Num, DnSta & Num=  ,4975, 2 ,4975, 2 , 0 , 0 , 0 ,,
     1.5     1.5
   28.68   46.11
     1.5     1.5
   28.67    46.1
Pier Skew, UpSta & Num, DnSta & Num=  ,5015.1, 2 ,5015.1, 2 , 0 , 0 , 0 ,,
     1.5     1.5
   25.27   45.96
     1.5     1.5
   25.26   45.95
Pier Skew, UpSta & Num, DnSta & Num=  ,5053.3, 2 ,5053.3, 2 , 0 , 0 , 0 ,,
     1.5     1.5
    32.5   45.82
     1.5     1.5
   32.49   45.81
Pier Skew, UpSta & Num, DnSta & Num=  ,5093.6, 2 ,5093.6, 2 , 0 , 0 , 0 ,,
     1.5     1.5
   40.84   45.67
     1.5     1.5
   40.83   45.66
BR Coef= 1 , 1 , 0 ,1.25, 0 ,,,.8,0,2,0,
WSPro=,,,, 1 ,,,, 0 ,,,, 0 ,,,,-1 ,-1 ,-1 , 0 , 0 , 0 , 0 , 0
BR U #Sta/Elev= 49
  3495.3   51.01  3535.3   50.81  3595.3   49.71  3757.1   49.14  4130.7   47.81
  4300.7   47.31  4530.7   47.71  4710.7   48.01  4720.7   48.41  4780.7   47.31
  4794.4   47.31 4818.46   47.39 4890.66   45.89 4895.36   45.31 4895.47    45.3
 4895.56   45.29 4903.26   44.34 4958.06   37.61 4982.56    26.6 4995.36   26.21
 5010.06   25.87 5017.46   26.57 5030.26   28.64 5038.86    30.9 5072.26   37.25
 5095.06   42.34 5101.05   43.67 5101.16    43.7 5101.26   43.72 5109.16   45.48
 5139.06   46.76 5166.76    46.7  5322.1   46.81  5382.6   46.91  5462.6   46.71
  5554.3   44.91  5723.9   47.01  5763.9   49.41    5830   49.88  5833.9   49.91
  5843.9   49.61  5873.9   47.61  5913.9   48.01  6103.9   47.91  6106.5   47.91
  6286.5   50.01  6306.5   50.71  6356.5   50.91  6364.9   51.11
BR U #Mann= 5
  3495.3      .2  3757.1      .1 4958.06    .045 5072.26      .1    5830     .99
BR U Banks=4958.06,5072.26
BR D #Sta/Elev= 49
  3495.3      51  3535.3    50.8  3595.3    49.7  3757.1   49.13  4130.7    47.8
  4300.7    47.3  4530.7    47.7  4710.7      48  4720.7    48.4  4780.7    47.3
  4794.4    47.3 4818.46   47.38 4890.66   45.88 4895.36    45.3 4895.47   45.29
 4895.56   45.28 4903.26   44.33 4958.06    37.6 4982.56   26.59 4995.36    26.2
 5010.06   25.86 5017.46   26.56 5030.26   28.63 5038.86   30.89 5072.26   37.24
 5095.06   42.33 5101.05   43.66 5101.16   43.69 5101.26   43.71 5109.16   45.47
 5139.06   46.75 5166.76   46.69  5322.1    46.8  5382.6    46.9  5462.6    46.7
  5554.3    44.9  5723.9      47  5763.9    49.4    5830   49.87  5833.9    49.9
  5843.9    49.6  5873.9    47.6  5913.9      48  6103.9    47.9  6106.5    47.9
  6286.5      50  6306.5    50.7  6356.5    50.9  6364.9    51.1
BR D #Mann= 5
  3495.3      .2  3757.1      .1 4958.06    .045 5072.26      .1    5830     .99
BR D Banks=4958.06,5072.26
BC Design=,, 0 ,, 0 ,,,,,,

Type RM Length L Ch R = 1 ,27167.5 ,701.4,701.4,701.4
BEGIN DESCRIPTION:
Downstream Section of Bridge/Culvert/Weir
END DESCRIPTION:
XS GIS Cut Line= 6
      3141068.26     13877787.28      3141076.59     13876342.34
      3141078.61     13876289.85       3141079.2     13876260.54
      3141080.19     13876226.75      3141179.91     13874921.57
#Sta/Elev= 30
  3495.3   50.98  3535.3   50.78  3595.3   49.68  3757.1   49.11  4300.7   47.28
  4710.7   47.98  4720.7   48.38  4780.7   47.28 4818.46   47.36 4890.66   45.86
 4958.06   37.58 4982.56   26.57 5010.06   25.84 5030.26   28.61 5038.86   30.87
 5072.26   37.22 5109.16   45.45 5139.06   46.73  5462.6   46.68  5554.3   44.88
  5723.9   46.98  5763.9   49.38    5830   49.85  5843.9   49.58  5873.9   47.58
  5913.9   47.98  6106.5   47.88  6286.5   49.98  6306.5   50.68  6364.9   51.08
#Mann= 5 , 1 , 0
  3495.3      .2       0  3757.1      .1       0 4958.06    .045       0
 5072.26      .1       0    5830     .99       0
#XS Ineff= 2 , 0
       0    4885   45.29    5111       0    44.8
Permanent Ineff=
       F       F
Bank Sta=4958.06,5072.26
XS Rating Curve= 0
Exp/Cntr=.5,.3

Type RM Length L Ch R = 1 ,26466.1 ,550.3,483.3,387.8
BEGIN DESCRIPTION:
Cross Section 26466.1-Interpolated
END DESCRIPTION:
XS GIS Cut Line= 4
      3141512.68     13877913.13      3141668.81     13876799.86
      3141750.27     13876277.17      3141804.19     13875158.46
#Sta/Elev= 30
  3655.9    50.5  4245.9    49.9  4515.9      48  4575.9    46.1    4607   47.24
  4635.9    48.3  4906.2   46.54  4929.7   39.22  4980.4    28.4  4985.8   24.77
  5011.5    24.2  5014.1   24.79    5021   29.55  5038.1   32.83  5054.9   39.84
  5170.1    47.6  5200.1    46.7  5240.1    47.4  5309.1    50.1  5429.1    49.8
  5469.1    47.5  5586.3   48.05  5659.1    49.1  5699.1    47.5  5859.1    46.7
  6069.1    50.1  6309.1    49.1  6349.1    50.7  6399.1    50.6  6429.1    52.3
#Mann= 6 , 1 , 0
  3655.9      .2       0  3655.9      .1       0    4607     .14       0
  4906.2    .045       0  5054.9     .14       0  5586.3      .1       0
#XS Ineff= 2 , 0
       0  4635.9    48.3  5309.1       0    50.1
Permanent Ineff=
       F       F
Bank Sta=4906.2,5054.9
XS Rating Curve= 0
Exp/Cntr=.3,.1

Type RM Length L Ch R = 1 ,25982.8 ,683.5,664.4,639.7
BEGIN DESCRIPTION:
Cross Section 25982.8
END DESCRIPTION:
XS GIS Cut Line= 5
      3142162.99     13878200.59      3142260.42     13877399.53
      3142303.72     13876782.49      3142065.56     13876371.13
      3141899.33     13875223.01
#Sta/Elev= 30
  3269.9    52.5  3326.8   52.36  3469.9      52  3509.9      50  3559.9    51.4
  3809.9    50.9  3839.9    49.1  3939.9    50.5  4506.9    47.7    4754   48.56
  4775.4    48.3  4805.4    45.6  4906.2   45.41  4929.7   38.09  4980.4   27.27
  4985.8   23.64  5011.5   23.07  5014.1   23.66    5021   28.42  5038.1    31.7
  5054.9   38.71  5070.6   39.43  5135.4    47.3  5155.4    48.9  5310.8    47.6
  5410.8    47.8  5450.8    49.5  5506.7   49.13  6080.8    48.8  6330.8    51.8
#Mann= 6 , 1 , 0
  3269.9      .2       0  3326.8      .1       0    4754     .14       0
  4906.2    .045       0  5054.9     .14       0  5506.7      .1       0
#XS Ineff= 2 , 0
       0                  5450.8       0    49.5
Permanent Ineff=
       F       F
Bank Sta=4906.2,5054.9
XS Rating Curve= 0
Exp/Cntr=.3,.1

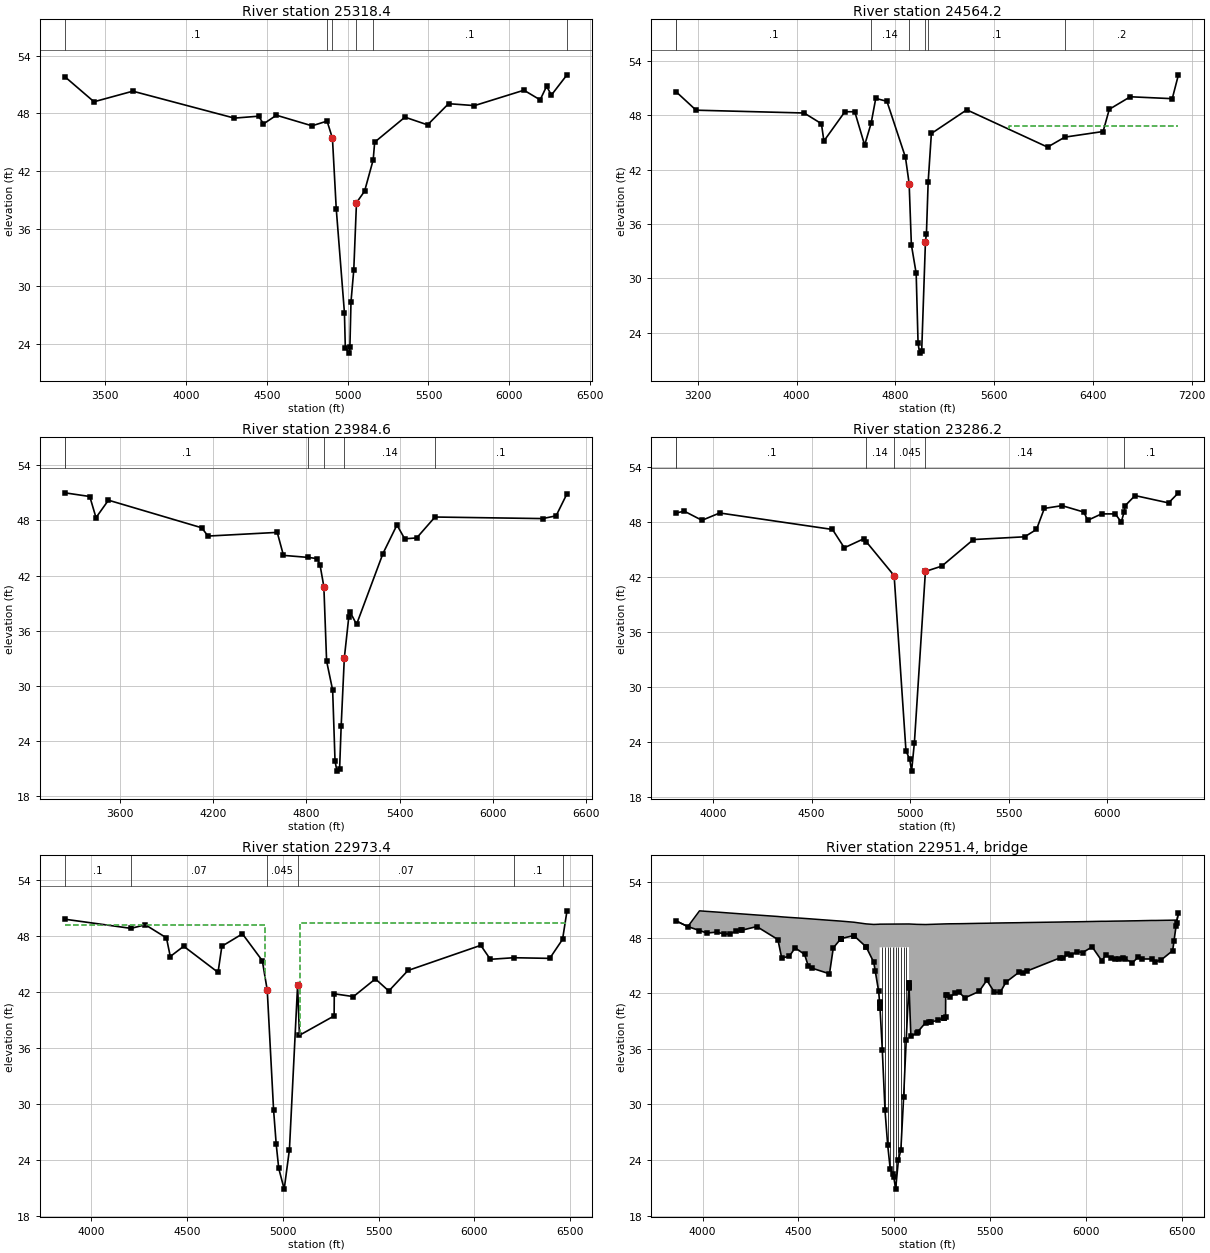
Type RM Length L Ch R = 1 ,25318.4 ,649,754.2,905.4
BEGIN DESCRIPTION:
Cross Section 25318.4
END DESCRIPTION:
XS GIS Cut Line= 6
      3142761.23     13877823.04      3142906.68     13877068.82
      3142844.98     13876306.18      3142531.05     13875970.59
      3142123.03     13875322.39      3141854.35     13875104.09
#Sta/Elev= 30
  3251.7    51.8  3431.7    49.2  3671.7    50.3  4299.8    47.5  4449.8    47.7
  4479.8    46.9  4559.8    47.8  4779.8    46.7    4873   47.19  4906.2   45.41
  4929.7   38.09  4980.4   27.27  4985.8   23.64  5011.5   23.07  5014.1   23.66
    5021   28.42  5038.1    31.7  5054.9   38.71  5104.9    39.9  5158.2   43.16
  5167.4      45  5354.5    47.6  5494.5    46.8  5624.5      49  5784.5    48.8
  6090.5    50.4  6190.5    49.4  6230.5    50.8  6260.5    49.9  6356.7      52
#Mann= 6 , 1 , 0
  3251.7      .1       0    4873     .14       0  4906.2    .045       0
  5054.9     .14       0  5158.2      .1       0  6356.7      .2       0
Bank Sta=4906.2,5054.9
XS Rating Curve= 0
Exp/Cntr=.3,.1

Type RM Length L Ch R = 1 ,24564.2 ,481.9,579.6,607.1
BEGIN DESCRIPTION:
Cross Section 24564.2-Interpolated
END DESCRIPTION:
XS GIS Cut Line= 6
      3143269.11      13877747.2      3143281.13     13877001.97
       3143323.2     13876082.45       3143323.2     13875595.64
      3143235.31     13875099.07      3142820.64     13873751.41
#Sta/Elev= 30
  3025.6   50.56  3185.6   48.55  4060.9   48.24  4200.9   47.06  4220.9   45.15
  4390.9   48.38  4470.9   48.38  4550.9    44.7  4603.4   47.11  4640.9   49.85
  4731.4   49.53  4881.4   43.36  4911.4   40.46  4929.4   33.72  4968.3   30.56
  4983.6   22.85  4996.1   21.76    5013      22  5043.4   34.06  5051.4   34.94
  5065.5   40.65  5091.4   45.98  5378.2   48.59  6032.5   44.48  6172.4   45.58
  6482.5    46.2  6532.5   48.65  6702.5   50.03  7042.5   49.82  7092.5   52.45
#Mann= 7 , 1 , 0
  3025.6      .2       0  3025.6      .1       0  4603.4     .14       0
  4911.4    .045       0  5043.4     .14       0  5065.5      .1       0
  6172.4      .2       0
#XS Ineff= 2 , 0
       0  4603.8    47.1  5720.4       0    46.8
Permanent Ineff=
       F       F
Bank Sta=4911.4,5043.4
XS Rating Curve= 0
Exp/Cntr=.3,.1

Type RM Length L Ch R = 1 ,23984.6 ,884.1,698.4,577
BEGIN DESCRIPTION:
Cross Section 23984.6
END DESCRIPTION:
XS GIS Cut Line= 6
      3143477.63     13877779.71      3143528.01      13876425.1
      3143835.87     13875994.09      3143830.28     13875647.05
      3143763.11     13875283.21      3143596.75     13874679.33
#Sta/Elev= 30
  3246.5      51  3406.5    50.6  3446.5    48.3  3526.5    50.2  4126.5    47.2
  4166.5    46.3    4612    46.7    4652    44.2  4811.5   43.98  4869.3   43.85
  4887.6   43.12  4911.8   40.79  4929.4   32.71  4968.3   29.55  4983.6   21.84
  4996.1   20.75    5013   20.99    5023   25.63  5043.4   33.05    5072    37.5
    5082      38    5122    36.7  5291.7    44.4  5381.7    47.5  5431.7      46
  5508.8    46.1  5626.4   48.37  6318.8    48.2  6405.2    48.5  6475.2    50.9
#Mann= 6 , 1 , 0
  3246.5      .2       0  3246.5      .1       0  4811.5     .14       0
  4911.8    .045       0  5043.4     .14       0  5626.4      .1       0
Bank Sta=4911.8,5043.4
XS Rating Curve= 0
Exp/Cntr=.3,.1

Type RM Length L Ch R = 1 ,23286.2 ,316.8,312.8,287.5
BEGIN DESCRIPTION:
Cross Section 23286.2-Interpolated
END DESCRIPTION:
XS GIS Cut Line= 5
      3145011.33     13877141.31      3144946.17     13876918.66
      3144538.87     13876288.71      3144337.94      13875984.6
      3143753.34     13874936.71
#Sta/Elev= 30
  3813.9      49  3853.9    49.2  3943.9    48.2  4033.9      49  4605.9    47.2
  4665.9    45.2  4765.9    46.2  4777.7   45.85  4918.6   42.16  4978.6   23.04
  4997.5   22.11  5007.1   20.82  5021.4   23.94  5077.2   42.62  5160.5    43.2
  5320.5    46.1  5580.5    46.4  5640.5    47.2  5680.5    49.5  5770.5    49.8
  5880.5    49.1  5900.5    48.2  5970.5    48.9  6040.5    48.9  6070.5      48
  6084.3   49.06  6090.5    49.8  6140.5    50.9  6310.5    50.1  6360.5    51.2
#Mann= 6 , 1 , 0
  3813.9      .2       0  3813.9      .1       0  4777.7     .14       0
  4918.6    .045       0  5077.2     .14       0  6084.3      .1       0
Bank Sta=4918.6,5077.2
XS Rating Curve= 0
Exp/Cntr=.5,.3

Type RM Length L Ch R = 1 ,22973.4 ,44,44,44
BEGIN DESCRIPTION:
Upstream Section of Bridge/Culvert/Weir
END DESCRIPTION:
XS GIS Cut Line= 6
      3145381.41     13876778.37      3144911.06     13876225.86
      3144709.41     13875969.45      3144589.92     13875830.04
       3144475.4     13875700.58      3143697.28      13874771.3
#Sta/Elev= 30
  3862.6    49.8  4207.2   48.82  4282.6    49.2  4392.6    47.8  4412.6    45.8
  4482.6    46.9  4661.8    44.1  4681.8    46.9  4789.1   48.23  4892.9   45.35
  4918.6   42.19  4951.7   29.34  4965.5   25.64  4978.6   23.07  5007.1   20.85
  5034.4    25.1    5077   42.71  5086.6   37.35  5267.7   39.43  5268.4    41.8
  5368.4    41.5  5482.9    43.4  5552.9    42.1  5652.9    44.3  6032.9      47
  6082.9    45.5  6205.5   45.67  6392.9    45.6  6459.8   47.64  6482.9    50.7
#Mann= 6 , 1 , 0
  3862.6      .1       0  4207.2     .07       0  4918.6    .045       0
    5077     .07       0  6205.5      .1       0  6459.8      .2       0
#XS Ineff= 2 , 0
       0  4908.6    49.2    5087       0   49.42
Permanent Ineff=
       F       F
Bank Sta=4918.6,5077
XS Rating Curve= 0
Exp/Cntr=.5,.3

Type RM Length L Ch R = 3 ,22951.4 ,,,
BEGIN DESCRIPTION:
UNION PACIFIC RAILROAD
Structure ID: P18-6
END DESCRIPTION:
Bridge Culvert--1,0,-1,-1, 0
Deck Dist Width WeirC Skew NumUp NumDn MinLoCord MaxHiCord MaxSubmerge Is_Ogee
10,24,2.6,0, 60, 60, , , .95, 0, 1,1,,
  3862.6  3922.6  3983.5  4022.6  4072.6  4142.6  4282.6  4392.6  4412.6  4452.6
  4482.6  4531.8  4551.8  4661.8  4681.8  4721.8  4789.1    4853  4892.9  4918.6
 4923.41  4923.5 5076.89    5077  5086.6  5116.1  5163.3  5267.7  5268.4  5288.4
  5338.4  5368.4  5442.9  5482.9  5522.9  5552.9  5582.9  5652.9  5672.9  5862.9
  5882.9  5902.9  5922.9  5952.9  5982.9  6032.9  6082.9  6102.9  6152.9  6192.9
  6242.9  6272.9  6292.9  6342.9  6362.9  6392.9  6452.9  6470.8  6472.9  6482.9
    49.8    49.2    50.9   50.84   50.77   50.66   50.45   50.29   50.25   50.19
   50.15   50.08   50.05   49.88   49.85   49.79   49.67   49.49   49.43   49.45
   49.46   49.46   49.48   49.48   49.47   49.44   49.42   49.49   49.49    49.5
   49.51   49.52   49.55   49.56   49.58   49.59    49.6   49.62   49.63   49.69
    49.7   49.71   49.71   49.72   49.73   49.75   49.77   49.77   49.79    49.8
   49.82   49.83   49.84   49.86   49.86   49.87   49.89    49.9    49.6    50.7
    49.8    49.2   48.77    48.5    48.6    48.4    49.2    47.8    45.8      46
    46.9    46.2    44.9    44.1    46.9    47.9   48.23   47.01   45.35   42.19
   40.98   46.96   46.98   42.71   37.35   37.68   38.82   39.43    41.8    41.6
    42.1    41.5    42.2    43.4    42.1    42.1    43.2    44.3    44.2    45.8
    45.8    46.2    46.1    46.5    46.4      47    45.5    46.1    45.7    45.8
    45.3    45.9    45.7    45.7    45.4    45.6    46.6   49.29    49.6    50.7
  3862.6  3922.6  3983.5  4022.6  4072.6  4142.6  4282.6  4392.6  4412.6  4452.6
  4482.6  4531.8  4551.8  4661.8  4681.8  4721.8  4789.1    4853  4892.9  4918.6
 4923.41  4923.5 5076.89    5077  5086.6  5116.1  5163.3  5267.7  5268.4  5288.4
  5338.4  5368.4  5442.9  5482.9  5522.9  5552.9  5582.9  5652.9  5672.9  5862.9
  5882.9  5902.9  5922.9  5952.9  5982.9  6032.9  6082.9  6102.9  6152.9  6192.9
  6242.9  6272.9  6292.9  6342.9  6362.9  6392.9  6452.9  6470.8  6472.9  6482.9
    49.8    49.2    50.9   50.84   50.77   50.66   50.45   50.29   50.25   50.19
   50.15   50.08   50.05   49.88   49.85   49.79   49.67   49.49   49.43   49.45
   49.46   49.46   49.48   49.48   49.47   49.44   49.42   49.49   49.49    49.5
   49.51   49.52   49.55   49.56   49.58   49.59    49.6   49.62   49.63   49.69
    49.7   49.71   49.71   49.72   49.73   49.75   49.77   49.77   49.79    49.8
   49.82   49.83   49.84   49.86   49.86   49.87   49.89    49.9    49.6    50.7
   49.49   48.89   48.46   48.19   48.29   48.09   48.89   47.49   45.49   45.69
   46.59   45.89   44.59   43.79   46.59   47.59   47.92    46.7   45.04   41.88
   40.67   46.65   46.67    42.4   37.04   37.37   38.51   39.12   41.49   41.29
   41.79   41.19   41.89   43.09   41.79   41.79   42.89   43.99   43.89   45.49
   45.49   45.89   45.79   46.19   46.09   46.69   45.19   45.79   45.39   45.49
   44.99   45.59   45.39   45.39   45.09   45.29   46.29   48.98   49.29   50.39
Pier Skew, UpSta & Num, DnSta & Num=  ,4937.4, 2 ,4937.4, 2 , 0 , 0 , 0 ,,
       1       1
   34.68   47.96
       1       1
   34.37   47.65
Pier Skew, UpSta & Num, DnSta & Num=  ,4951.7, 2 ,4951.7, 2 , 0 , 0 , 0 ,,
       1       1
   28.21   47.96
       1       1
    27.9   47.65
Pier Skew, UpSta & Num, DnSta & Num=  ,4965.5, 2 ,4965.5, 2 , 0 , 0 , 0 ,,
       1       1
   24.54   47.97
       1       1
   24.23   47.66
Pier Skew, UpSta & Num, DnSta & Num=  ,4978.6, 2 ,4978.6, 2 , 0 , 0 , 0 ,,
       1       1
   22.05   47.97
       1       1
   21.74   47.66
Pier Skew, UpSta & Num, DnSta & Num=  ,4993.4, 2 ,4993.4, 2 , 0 , 0 , 0 ,,
       1       1
   21.39   47.97
       1       1
   21.08   47.66
Pier Skew, UpSta & Num, DnSta & Num=  ,5007.1, 2 ,5007.1, 2 , 0 , 0 , 0 ,,
       1       1
   19.92   47.97
       1       1
   19.61   47.66
Pier Skew, UpSta & Num, DnSta & Num=  ,5021.4, 2 ,5021.4, 2 , 0 , 0 , 0 ,,
       1       1
   22.86   47.97
       1       1
   22.55   47.66
Pier Skew, UpSta & Num, DnSta & Num=  ,5034.4, 2 ,5034.4, 2 , 0 , 0 , 0 ,,
       1       1
   24.06   47.97
       1       1
   23.75   47.66
Pier Skew, UpSta & Num, DnSta & Num=  ,5048.7, 2 ,5048.7, 2 , 0 , 0 , 0 ,,
       1       1
   29.56   47.98
       1       1
   29.25   47.67
Pier Skew, UpSta & Num, DnSta & Num=  ,5062.3, 2 ,5062.3, 2 , 0 , 0 , 0 ,,
       1       1
   35.71   47.98
       1       1
    35.4   47.67
Abutment Skew #Up #Dn= , 2 , 2
  4923.3  4925.7
   46.96   40.41
  4923.3  4925.7
   46.65    40.1
BR Coef= 1 , 1 , 0 ,1.25, 0 ,,,.8,0,2,0,
WSPro=,,,, 1 ,,,, 0 ,,,, 0 ,,,,-1 ,-1 ,-1 , 0 , 0 , 0 , 0 , 0
BR U #Sta/Elev= 104
  3862.6    49.8  3922.6    49.2  3983.5   48.77  4022.6    48.5  4072.6    48.6
  4112.6    48.4  4142.6    48.4  4172.6    48.7  4202.6    48.8  4207.2   48.82
  4282.6    49.2  4392.6    47.8  4412.6    45.8  4452.6      46  4482.6    46.9
  4531.8    46.2  4551.8    44.9  4571.8    44.7  4661.8    44.1  4681.8    46.9
  4721.8    47.9 4721.89    47.9    4722    47.9 4722.11    47.9  4722.2    47.9
  4789.1   48.23  4789.4   48.22  4851.4   47.04    4853   47.01  4892.9   45.35
  4900.7   44.39  4918.6   42.19  4923.3   41.01 4923.41   40.98  4923.5   40.96
  4925.6   40.44  4925.7   40.41  4937.4   35.91  4951.7   29.34  4965.5   25.64
  4978.6   23.07  4993.4   22.43  4997.5   22.14  5007.1   20.85  5021.4   23.97
  5034.4    25.1  5048.7   30.76  5062.3   36.94  5076.3   43.06  5076.4    43.1
 5076.89   42.79    5077   42.71  5077.1   42.65  5077.2   42.59  5086.6   37.35
  5116.1   37.68  5122.8   37.84  5163.3   38.82  5182.8   38.89  5192.9   38.93
  5226.6   39.06 5261.29   39.37  5261.4   39.37 5261.51   39.37  5267.7   39.43
  5268.4    41.8  5272.9   41.76  5288.4    41.6  5318.4      42  5338.4    42.1
  5368.4    41.5  5442.9    42.2  5482.9    43.4  5522.9    42.1  5552.9    42.1
  5582.9    43.2  5652.9    44.3  5672.9    44.2  5692.9    44.4  5862.9    45.8
  5882.9    45.8  5902.9    46.2  5922.9    46.1  5952.9    46.5  5982.9    46.4
  6032.9      47  6082.9    45.5  6102.9    46.1  6132.9    45.8  6152.9    45.7
  6172.9    45.7  6192.9    45.8  6205.5   45.67  6242.9    45.3  6272.9    45.9
  6292.9    45.7  6342.9    45.7  6362.9    45.4  6392.9    45.6  6452.9    46.6
  6459.8   47.64  6470.8   49.29  6472.9    49.6  6482.9    50.7
BR U #Mann= 6
  3862.6      .1  4207.2     .07  4918.6    .045    5077     .07  6205.5      .1
  6459.8      .2
BR U Banks=4918.6,5077
BR D #Sta/Elev= 104
  3862.6   49.49  3922.6   48.89  3983.5   48.46  4022.6   48.19  4072.6   48.29
  4112.6   48.09  4142.6   48.09  4172.6   48.39  4202.6   48.49  4207.2   48.51
  4282.6   48.89  4392.6   47.49  4412.6   45.49  4452.6   45.69  4482.6   46.59
  4531.8   45.89  4551.8   44.59  4571.8   44.39  4661.8   43.79  4681.8   46.59
  4721.8   47.59 4721.89   47.59    4722   47.59 4722.11   47.59  4722.2   47.59
  4789.1   47.92  4789.4   47.91  4851.4   46.73    4853    46.7  4892.9   45.04
  4900.7   44.08  4918.6   41.88  4923.3    40.7 4923.41   40.67  4923.5   40.65
  4925.6   40.13  4925.7    40.1  4937.4    35.6  4951.7   29.03  4965.5   25.33
  4978.6   22.76  4993.4   22.12  4997.5   21.83  5007.1   20.54  5021.4   23.66
  5034.4   24.79  5048.7   30.45  5062.3   36.63  5076.3   42.75  5076.4   42.79
 5076.89   42.48    5077    42.4  5077.1   42.34  5077.2   42.28  5086.6   37.04
  5116.1   37.37  5122.8   37.53  5163.3   38.51  5182.8   38.58  5192.9   38.62
  5226.6   38.75 5261.29   39.06  5261.4   39.06 5261.51   39.06  5267.7   39.12
  5268.4   41.49  5272.9   41.45  5288.4   41.29  5318.4   41.69  5338.4   41.79
  5368.4   41.19  5442.9   41.89  5482.9   43.09  5522.9   41.79  5552.9   41.79
  5582.9   42.89  5652.9   43.99  5672.9   43.89  5692.9   44.09  5862.9   45.49
  5882.9   45.49  5902.9   45.89  5922.9   45.79  5952.9   46.19  5982.9   46.09
  6032.9   46.69  6082.9   45.19  6102.9   45.79  6132.9   45.49  6152.9   45.39
  6172.9   45.39  6192.9   45.49  6205.5   45.36  6242.9   44.99  6272.9   45.59
  6292.9   45.39  6342.9   45.39  6362.9   45.09  6392.9   45.29  6452.9   46.29
  6459.8   47.33  6470.8   48.98  6472.9   49.29  6482.9   50.39
BR D #Mann= 6
  3862.6      .1  4207.2     .07  4918.6    .045    5077     .07  6205.5      .1
  6459.8      .2
BR D Banks=4918.6,5077
BC Design=,, 0 ,, 0 ,,,,,,