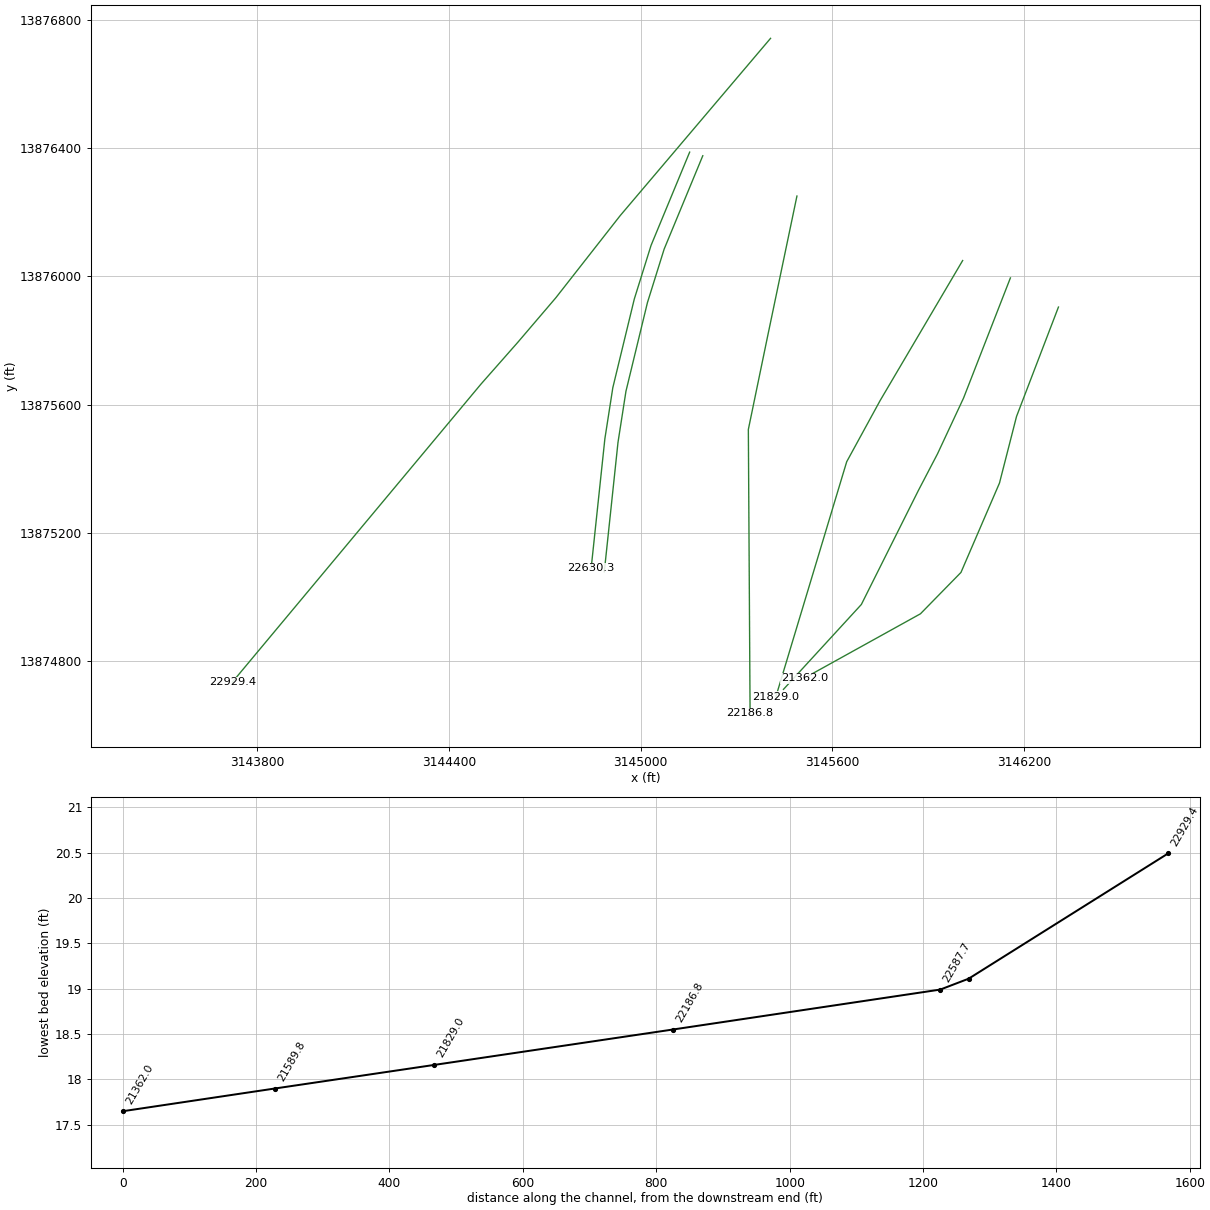
HEC-RAS study P118-00-00.PRJ: P118-00-00

--- P118-00-00.g01 (geometry) --- (continued)

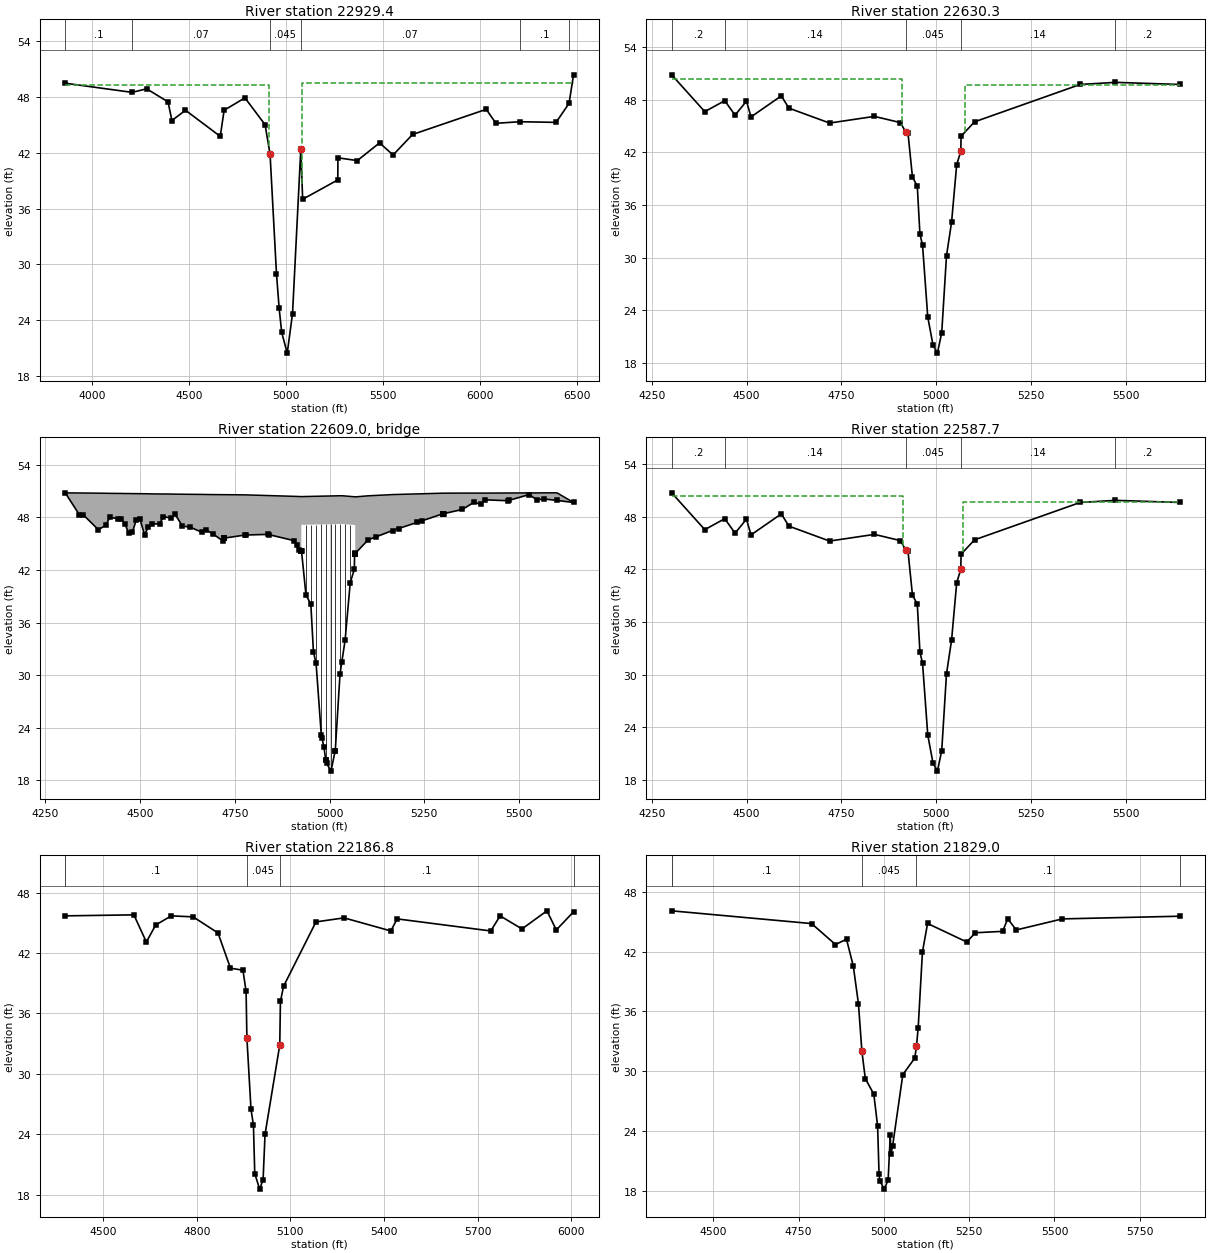
Type RM Length L Ch R = 1 ,22929.4 ,299.1,299.1,299.1
BEGIN DESCRIPTION:
Downstream Section of Bridge/Culvert/Weir
END DESCRIPTION:
XS GIS Cut Line= 6
      3145406.65     13876742.33       3144936.3     13876189.82
      3144734.65     13875933.41      3144615.16       13875794.
      3144500.64     13875664.54      3143722.51     13874735.26
#Sta/Elev= 30
  3862.6   49.44  4207.2   48.46  4282.6   48.84  4392.6   47.44  4412.6   45.44
  4482.6   46.54  4661.8   43.74  4681.8   46.54  4789.1   47.87  4892.9   44.99
  4918.6   41.83  4951.7   28.98  4965.5   25.28  4978.6   22.71  5007.1   20.49
  5034.4   24.74    5077   42.35  5086.6   36.99  5267.7   39.07  5268.4   41.44
  5368.4   41.14  5482.9   43.04  5552.9   41.74  5652.9   43.94  6032.9   46.64
  6082.9   45.14  6205.5   45.31  6392.9   45.24  6459.8   47.28  6482.9   50.34
#Mann= 6 , 1 , 0
  3862.6      .1       0  4207.2     .07       0  4918.6    .045       0
    5077     .07       0  6205.5      .1       0  6459.8      .2       0
#XS Ineff= 2 , 0
       0 4911.93    49.2 5083.67       0   49.42
Permanent Ineff=
       F       F
Bank Sta=4918.6,5077
XS Rating Curve= 0
Exp/Cntr=.5,.3

Type RM Length L Ch R = 1 ,22630.3 ,42.6,42.6,42.6
BEGIN DESCRIPTION:
Upstream Section of Bridge/Culvert/Weir
END DESCRIPTION:
XS GIS Cut Line= 6
      3145153.53      13876387.6       3145032.6      13876096.5
      3144980.32      13875929.7      3144913.11     13875653.37
      3144888.21     13875494.05      3144845.28     13875090.48
#Sta/Elev= 30
  4302.1   50.85  4389.5   46.65  4442.1    47.9  4469.5   46.25  4499.5   47.85
  4511.5   46.05  4591.5   48.45  4611.5   47.05  4718.9   45.35  4837.3   46.11
  4905.9    45.4  4920.3   44.29  4925.8   44.22  4937.6    39.2  4950.4   38.15
  4957.3   32.71  4964.3    31.4    4978   23.24  4991.9   20.02  5003.5   19.11
  5014.9   21.45  5027.5   30.22  5040.9   34.05  5054.4    40.6  5065.3   42.14
  5065.9   43.85  5101.6   45.49  5380.2   49.75  5473.3   49.99  5643.8   49.75
#Mann= 5 , 1 , 0
  4302.1      .2       0  4442.1     .14       0  4920.3    .045       0
  5065.3     .14       0  5473.3      .2       0
#XS Ineff= 2 , 0
       0  4910.3   50.38  5075.3       0    49.7
Permanent Ineff=
       F       F
Bank Sta=4920.3,5065.3
XS Rating Curve= 0
Exp/Cntr=.5,.3

Type RM Length L Ch R = 3 ,22609.0 ,,,
BEGIN DESCRIPTION:
UNION PACIFIC RAILROAD
Structure ID: P18-5
END DESCRIPTION:
Bridge Culvert--1,0,-1,-1, 0
Deck Dist Width WeirC Skew NumUp NumDn MinLoCord MaxHiCord MaxSubmerge Is_Ogee
10,22.6,2.6,0, 50, 50, , , .95, 0, 1,1,,
  4302.1  4339.5  4349.5  4389.5  4409.5  4419.5  4449.5  4459.5  4469.5  4479.5
  4489.5  4499.5  4511.5  4521.5  4531.5  4551.5  4561.5  4581.5  4591.5  4611.5
  4631.5  4662.5  4672.5  4692.5  4718.9  4720.6  4721.4  4775.6  4837.3  4905.9
  4920.3 4925.31  4925.4  5032.3    5066 5067.59  5067.7  5101.6  5166.1  5299.2
  5350.2  5380.2  5400.2  5410.2  5470.2  5526.8  5546.8  5566.8  5600.1  5643.8
    50.8   50.78   50.78   50.76   50.75   50.74   50.73   50.72   50.72   50.71
   50.71    50.7    50.7   50.69   50.68   50.67   50.67   50.66   50.65   50.64
   50.63   50.62   50.61    50.6   50.59   50.59   50.59   50.57   50.49    50.4
   50.38   50.37   50.37   50.47   50.35   50.34   50.34   50.46    50.6   50.76
   50.77   50.77   50.77   50.77   50.78   50.79   50.79    50.8    50.8    49.7
    50.8    48.3    48.3    46.6    47.1      48    47.8    47.3    46.2    46.3
    47.7    47.8      46    46.9    47.2    47.3    48.1    47.9    48.4      47
    46.9    46.3    46.6    46.1    45.3   45.62   45.63   45.98   46.06   45.35
   44.24   44.18   47.15   47.25   47.13   47.12   43.88   45.44    46.5   48.41
    48.9    49.7    49.5      50    49.9    50.6      50    50.1   49.93    49.7
  4302.1  4339.5  4349.5  4389.5  4409.5  4419.5  4449.5  4459.5  4469.5  4479.5
  4489.5  4499.5  4511.5  4521.5  4531.5  4551.5  4561.5  4581.5  4591.5  4611.5
  4631.5  4662.5  4672.5  4692.5  4718.9  4720.6  4721.4  4775.6  4837.3  4905.9
  4920.3 4925.31  4925.4  5032.3    5066 5067.59  5067.7  5101.6  5166.1  5299.2
  5350.2  5380.2  5400.2  5410.2  5470.2  5526.8  5546.8  5566.8  5600.1  5643.8
    50.8   50.78   50.78   50.76   50.75   50.74   50.73   50.72   50.72   50.71
   50.71    50.7    50.7   50.69   50.68   50.67   50.67   50.66   50.65   50.64
   50.63   50.62   50.61    50.6   50.59   50.59   50.59   50.57   50.49    50.4
   50.38   50.37   50.37   50.47   50.35   50.34   50.34   50.46    50.6   50.76
   50.77   50.77   50.77   50.77   50.78   50.79   50.79    50.8    50.8    49.7
   50.74   48.24   48.24   46.54   47.04   47.94   47.74   47.24   46.14   46.24
   47.64   47.74   45.94   46.84   47.14   47.24   48.04   47.84   48.34   46.94
   46.84   46.24   46.54   46.04   45.24   45.56   45.57   45.92      46   45.29
   44.18   44.12   47.09   47.19   47.07   47.06   43.82   45.38   46.44   48.35
   48.84   49.64   49.44   49.94   49.84   50.54   49.94   50.04   49.87   49.64
Pier Skew, UpSta & Num, DnSta & Num=  ,4937.6, 2 ,4937.6, 2 , 0 , 0 , 0 ,,
       1       1
   38.11   48.16
       1       1
   38.05    48.1
Pier Skew, UpSta & Num, DnSta & Num=  ,4950.4, 2 ,4950.4, 2 , 0 , 0 , 0 ,,
       1       1
   36.71   48.17
       1       1
   36.65   48.11
Pier Skew, UpSta & Num, DnSta & Num=  ,4964.3, 2 ,4964.3, 2 , 0 , 0 , 0 ,,
       1       1
   30.05   48.18
       1       1
   29.99   48.12
Pier Skew, UpSta & Num, DnSta & Num=  ,4978, 2 ,4978, 2 , 0 , 0 , 0 ,,
       1       1
   22.09   48.19
       1       1
   22.03   48.13
Pier Skew, UpSta & Num, DnSta & Num=  ,4989.7, 2 ,4989.7, 2 , 0 , 0 , 0 ,,
       1       1
   19.29    48.2
       1       1
   19.23   48.14
Pier Skew, UpSta & Num, DnSta & Num=  ,5003.5, 2 ,5003.5, 2 , 0 , 0 , 0 ,,
       1       1
    18.1   48.22
       1       1
   18.04   48.16
Pier Skew, UpSta & Num, DnSta & Num=  ,5014.9, 2 ,5014.9, 2 , 0 , 0 , 0 ,,
       1       1
   20.32   48.23
       1       1
   20.26   48.17
Pier Skew, UpSta & Num, DnSta & Num=  ,5027.5, 2 ,5027.5, 2 , 0 , 0 , 0 ,,
       1       1
   28.82   48.24
       1       1
   28.76   48.18
Pier Skew, UpSta & Num, DnSta & Num=  ,5040.9, 2 ,5040.9, 2 , 0 , 0 , 0 ,,
       1       1
   32.86   48.22
       1       1
    32.8   48.16
Pier Skew, UpSta & Num, DnSta & Num=  ,5054.4, 2 ,5054.4, 2 , 0 , 0 , 0 ,,
       1       1
   39.31   48.17
       1       1
   39.25   48.11
Abutment Skew #Up #Dn= , 2 , 2
    5066 5067.79
    43.8   47.12
    5066 5067.79
   43.74   47.06
BR Coef= 1 , 1 , 0 ,1.25, 0 ,,,.8,0,2,0,
WSPro=,,,, 1 ,,,, 0 ,,,, 0 ,,,,-1 ,-1 ,-1 , 0 , 0 , 0 , 0 , 0
BR U #Sta/Elev= 88
  4302.1    50.8  4339.5    48.3  4349.5    48.3  4389.5    46.6  4409.5    47.1
  4419.5      48  4442.1   47.85  4449.5    47.8  4459.5    47.3  4469.5    46.2
  4479.5    46.3  4489.5    47.7  4499.5    47.8  4511.5      46  4521.5    46.9
  4531.5    47.2  4551.5    47.3  4561.5    48.1  4581.5    47.9  4591.5    48.4
  4611.5      47  4631.5    46.9  4662.5    46.3  4672.5    46.6  4692.5    46.1
  4718.9    45.3  4720.6   45.62 4720.99   45.62  4721.1   45.62 4721.21   45.62
  4721.4   45.63  4775.6   45.98  4780.2   45.99  4837.3   46.06  4838.9   46.04
  4905.9   45.35  4912.6   44.83  4920.3   44.24  4925.2   44.18 4925.31   44.18
  4925.4   44.18  4925.7   44.17  4925.8   44.17  4937.6   39.15  4950.4    38.1
  4957.3   32.66  4964.3   31.35    4978   23.19  4979.7   22.85  4985.1   21.76
  4989.7   20.35  4989.8   20.36  4991.9   19.97  5003.5   19.06  5014.8    21.4
  5014.9    21.4  5027.5   30.17  5032.3   31.54  5040.9      34  5054.4   40.55
  5065.3   42.09  5065.9    43.8    5066    43.8 5067.59   43.88  5067.7   43.88
  5067.8   43.89  5101.6   45.44  5123.7    45.8  5166.1    46.5  5182.3   46.73
  5230.6   47.42  5242.6   47.59  5299.2   48.41  5300.1   48.42 5300.39   48.42
  5300.5   48.42 5300.61   48.42  5350.2    48.9  5380.2    49.7  5400.2    49.5
  5410.2      50  5470.2    49.9  5473.3   49.94  5526.8    50.6  5546.8      50
  5566.8    50.1  5600.1   49.93  5643.8    49.7
BR U #Mann= 5
  4302.1      .2  4442.1     .14  4920.3    .045  5065.3     .14  5473.3      .2
BR U Banks=4920.3,5065.3
BR D #Sta/Elev= 88
  4302.1   50.74  4339.5   48.24  4349.5   48.24  4389.5   46.54  4409.5   47.04
  4419.5   47.94  4442.1   47.79  4449.5   47.74  4459.5   47.24  4469.5   46.14
  4479.5   46.24  4489.5   47.64  4499.5   47.74  4511.5   45.94  4521.5   46.84
  4531.5   47.14  4551.5   47.24  4561.5   48.04  4581.5   47.84  4591.5   48.34
  4611.5   46.94  4631.5   46.84  4662.5   46.24  4672.5   46.54  4692.5   46.04
  4718.9   45.24  4720.6   45.56 4720.99   45.56  4721.1   45.56 4721.21   45.56
  4721.4   45.57  4775.6   45.92  4780.2   45.93  4837.3      46  4838.9   45.98
  4905.9   45.29  4912.6   44.77  4920.3   44.18  4925.2   44.12 4925.31   44.12
  4925.4   44.12  4925.7   44.11  4925.8   44.11  4937.6   39.09  4950.4   38.04
  4957.3    32.6  4964.3   31.29    4978   23.13  4979.7   22.79  4985.1    21.7
  4989.7   20.29  4989.8    20.3  4991.9   19.91  5003.5      19  5014.8   21.34
  5014.9   21.34  5027.5   30.11  5032.3   31.48  5040.9   33.94  5054.4   40.49
  5065.3   42.03  5065.9   43.74    5066   43.74 5067.59   43.82  5067.7   43.82
  5067.8   43.83  5101.6   45.38  5123.7   45.74  5166.1   46.44  5182.3   46.67
  5230.6   47.36  5242.6   47.53  5299.2   48.35  5300.1   48.36 5300.39   48.36
  5300.5   48.36 5300.61   48.36  5350.2   48.84  5380.2   49.64  5400.2   49.44
  5410.2   49.94  5470.2   49.84  5473.3   49.88  5526.8   50.54  5546.8   49.94
  5566.8   50.04  5600.1   49.87  5643.8   49.64
BR D #Mann= 5
  4302.1      .2  4442.1     .14  4920.3    .045  5065.3     .14  5473.3      .2
BR D Banks=4920.3,5065.3
BC Design=,, 0 ,, 0 ,,,,,,

Type RM Length L Ch R = 1 ,22587.7 ,400.9,400.9,400.9
BEGIN DESCRIPTION:
Downstream Section of Bridge/Culvert/Weir
END DESCRIPTION:
XS GIS Cut Line= 6
      3145194.59     13876376.28      3145073.66     13876085.18
      3145021.38     13875918.38      3144954.17     13875642.05
      3144929.27     13875482.73      3144886.35     13875079.15
#Sta/Elev= 30
  4302.1   50.73  4389.5   46.53  4442.1   47.78  4469.5   46.13  4499.5   47.73
  4511.5   45.93  4591.5   48.33  4611.5   46.93  4718.9   45.23  4837.3   45.99
  4905.9   45.28  4920.3   44.17  4925.8    44.1  4937.6   39.08  4950.4   38.03
  4957.3   32.59  4964.3   31.28    4978   23.12  4991.9    19.9  5003.5   18.99
  5014.9   21.33  5027.5    30.1  5040.9   33.93  5054.4   40.48  5065.3   42.02
  5065.9   43.73  5101.6   45.37  5380.2   49.63  5473.3   49.87  5643.8   49.63
#Mann= 5 , 1 , 0
  4302.1      .2       0  4442.1     .14       0  4920.3    .045       0
  5065.3     .14       0  5473.3      .2       0
#XS Ineff= 2 , 0
       0 4913.63   50.38 5071.97       0    49.7
Permanent Ineff=
       F       F
Bank Sta=4920.3,5065.3
XS Rating Curve= 0
Exp/Cntr=.5,.3

Type RM Length L Ch R = 1 ,22186.8 ,387.6,357.8,318.6
BEGIN DESCRIPTION:
Cross Section 22186.8-Interpolated
END DESCRIPTION:
XS GIS Cut Line= 4
      3145489.22     13876250.69      3145396.91     13875810.82
      3145337.17       13875523.       3145342.6     13874637.81
#Sta/Elev= 30
  4378.6    45.7  4598.6    45.8  4638.6    43.1  4668.6    44.8  4718.6    45.7
  4788.6    45.6  4868.1      44  4908.1    40.5  4948.1    40.3  4958.1    38.2
  4960.7   33.57  4973.8   26.51  4981.7   24.89  4985.9   20.09  5001.6   18.55
  5012.6   19.49  5018.8   23.99    5066   32.87  5068.1    37.2  5078.1    38.7
    5182    45.1    5272    45.5    5422    44.2    5442    45.4    5742    44.2
    5772    45.7    5842    44.4    5922    46.2    5952    44.3  6007.2    46.1
#Mann= 5 , 1 , 0
  4378.6      .2       0  4378.6      .1       0  4960.7    .045       0
    5066      .1       0  6007.2      .2       0
#XS Ineff= 2 , 0
       0  4718.6    45.7    5772       0    45.7
Permanent Ineff=
       F       F
Bank Sta=4960.7,5066
XS Rating Curve= 0
Exp/Cntr=.3,.1

Type RM Length L Ch R = 1 ,21829.0 ,238.7,239.2,244.2
BEGIN DESCRIPTION:
Cross Section 21829.0-Interpolated
END DESCRIPTION:
XS GIS Cut Line= 4
      3146007.83     13876049.67      3145749.47     13875612.92
      3145644.89     13875422.23      3145423.44     13874690.21
#Sta/Elev= 30
  4378.2   46.09  4788.2   44.81  4858.2   42.71  4890.6   43.24  4910.6   40.52
  4925.6   36.75  4935.6   32.01  4945.6   29.26  4970.6   27.69  4981.7    24.5
  4985.9    19.7  4988.1   18.99  5001.6   18.16  5012.6    19.1  5018.8    23.6
  5020.6   21.68  5025.6   22.48  5055.6   29.65  5090.6   31.31  5095.6    32.5
  5100.6   34.35  5113.1   41.96  5128.1   44.82  5243.1   42.96  5268.1   43.89
  5348.1   44.03  5363.1   45.29  5388.1   44.17  5523.1   45.28  5867.9   45.55
#Mann= 5 , 1 , 0
  4378.2      .2       0  4378.2      .1       0  4935.6    .045       0
  5095.6      .1       0  5867.9      .2       0
Bank Sta=4935.6,5095.6
XS Rating Curve= 0
Exp/Cntr=.3,.1

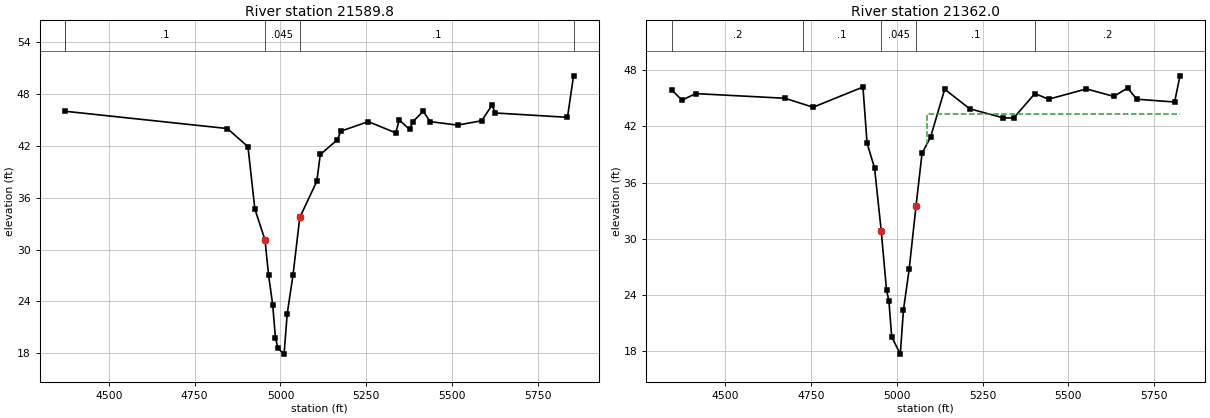
Type RM Length L Ch R = 1 ,21589.8 ,214.8,227.8,233.1
BEGIN DESCRIPTION:
Cross Section 21589.8-Interpolated
END DESCRIPTION:
XS GIS Cut Line= 6
      3146157.19     13875995.46      3146010.56     13875620.75
       3145929.1     13875446.97      3145869.37     13875332.93
      3145690.78     13874977.26      3145447.03     13874712.66
#Sta/Elev= 30
    4373      46  4845.4      44  4905.4    41.9  4925.4    34.7    4955   31.11
  4965.5   27.02  4977.4   23.62  4985.5   19.75    4993   18.57  5010.6    17.9
  5019.7   22.58  5036.6   27.04  5056.3   33.71    5106    37.9    5116      41
    5166    42.7    5176    43.7    5256    44.8    5336    43.5    5346      45
    5376    43.9    5386    44.8    5416      46    5436    44.8  5516.2    44.4
  5586.2    44.9  5616.2    46.7  5626.2    45.8  5836.2    45.3  5853.8    50.1
#Mann= 5 , 1 , 0
    4373      .2       0    4373      .1       0    4955    .045       0
  5056.3      .1       0  5853.8      .2       0
Bank Sta=4955,5056.3
XS Rating Curve= 0
Exp/Cntr=.5,.3

Type RM Length L Ch R = 1 ,21362.0 ,58,58,58
BEGIN DESCRIPTION:
Upstream Section of Bridge/Culvert/Weir
END DESCRIPTION:
XS GIS Cut Line= 6
      3146307.57     13875904.57      3146176.38     13875563.49
      3146123.05     13875355.91      3146002.51     13875077.24
      3145875.63     13874948.18      3145512.11     13874747.56
#Sta/Elev= 30
  4345.1   45.91  4375.1   44.81  4415.1   45.51  4675.1   45.01  4756.6   44.05
  4901.9   46.21  4913.9    40.2  4935.6   37.57    4955   30.86  4970.5    24.5
  4977.4   23.37  4985.5    19.5  5010.6   17.65  5019.7   22.33  5036.6   26.79
  5056.3   33.46  5073.9   39.13  5098.7   40.85  5139.8   45.98  5212.4   43.89
  5310.8   42.91  5340.8   42.91  5402.4   45.51  5442.3   44.91  5552.3   46.01
  5632.3   45.21  5672.3   46.11  5699.1   44.91  5809.1   44.61  5824.8   47.41
#Mann= 5 , 1 , 0
  4345.1      .2       0  4726.8      .1       0    4955    .045       0
  5056.3      .1       0  5402.4      .2       0
#XS Ineff= 2 , 0
       0  4901.5    44.5  5087.1       0    43.3
Permanent Ineff=
       F       F
Bank Sta=4955,5056.3
XS Rating Curve= 0
Exp/Cntr=.5,.3