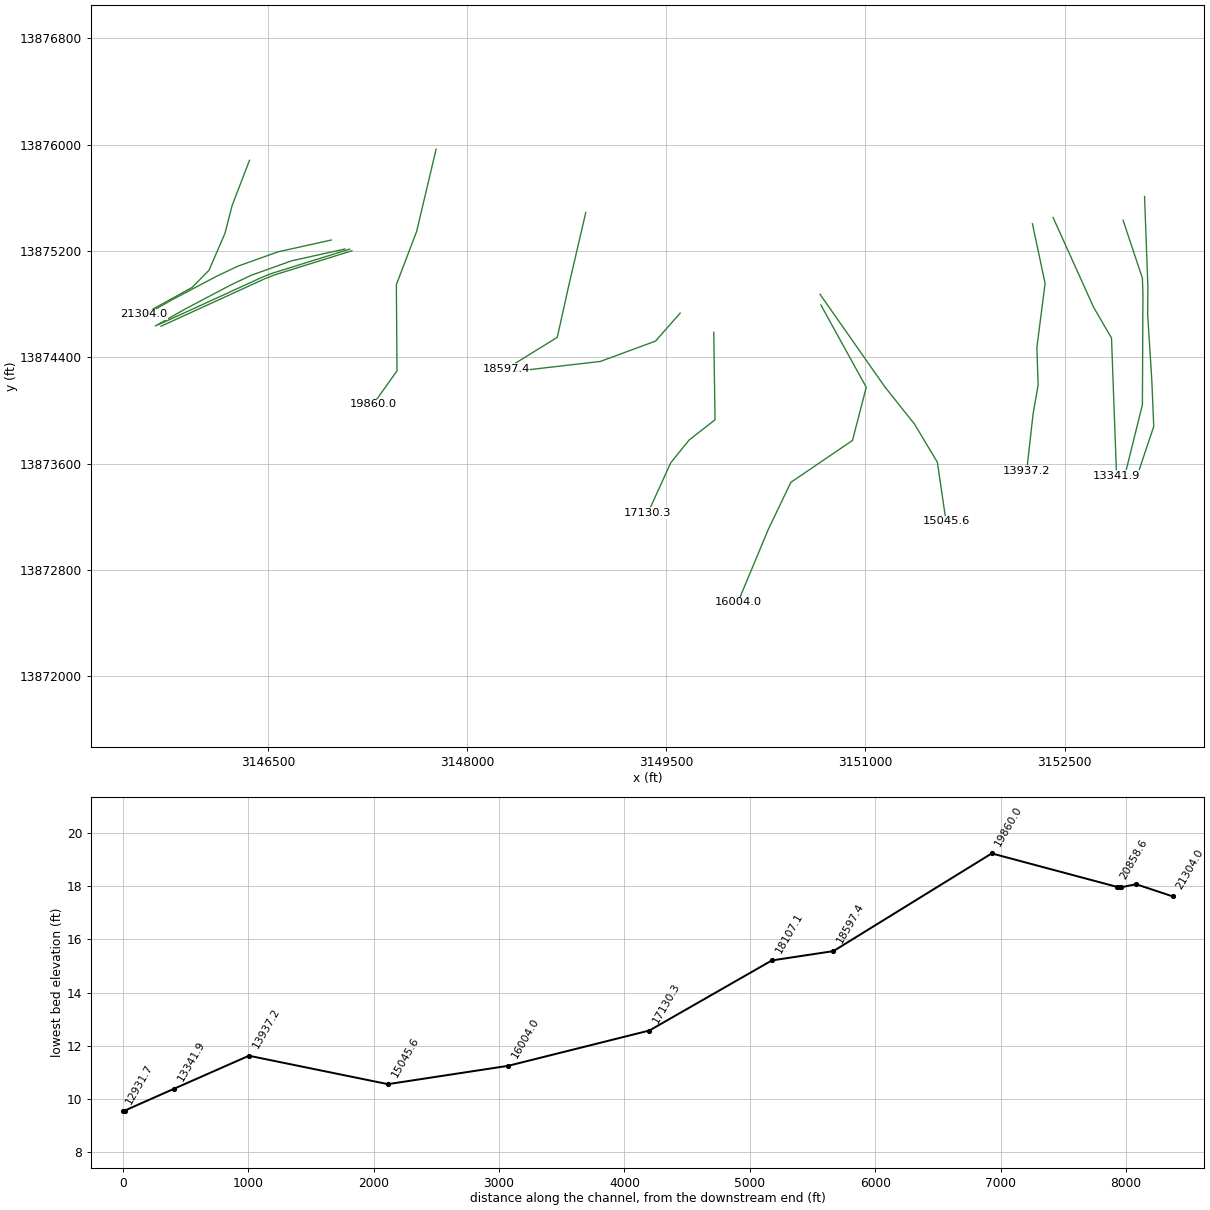
HEC-RAS study P118-00-00.PRJ: P118-00-00

--- P118-00-00.g01 (geometry) --- (continued)

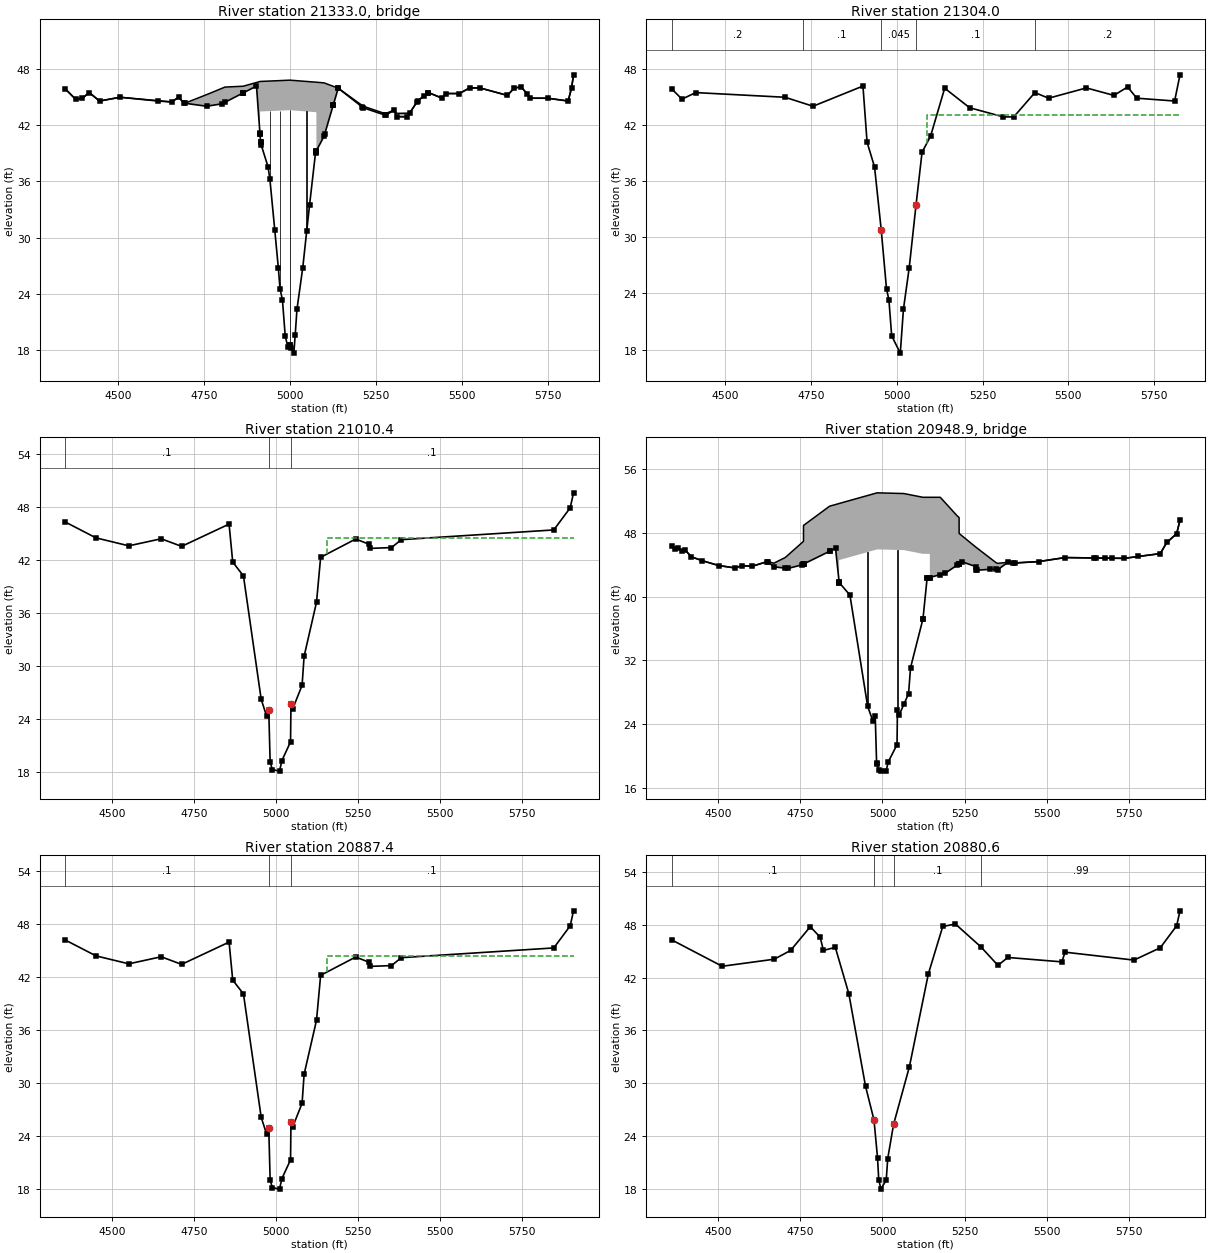
Type RM Length L Ch R = 3 ,21333.0 ,,,
BEGIN DESCRIPTION:
WAYSIDE DRIVE
Structure ID: P18-4
END DESCRIPTION:
Bridge Culvert--1,0,-1,-1, 0
Deck Dist Width WeirC Skew NumUp NumDn MinLoCord MaxHiCord MaxSubmerge Is_Ogee
10,38,2.6,0, 45, 45, , , .95, 0, 1,1,,
  4345.1  4375.1  4395.1  4415.1  4445.1  4505.1  4655.1  4675.1  4691.4  4693.6
  4756.6  4801.6  4810.1 4863.01  4901.9 4912.11  4912.2  4999.2 5076.29  5076.4
  5098.7  5139.8  5212.4  5275.7    5278  5300.8  5310.8  5340.8  5348.6  5370.8
  5402.3  5442.3  5452.3  5492.3  5522.3  5552.3  5632.3  5652.3  5672.3  5689.1
  5699.1  5749.1  5809.1  5819.1  5824.8
    45.9    44.8    44.9    45.5    44.6      45    44.5      45   44.37   44.37
   45.28   45.96   46.09   46.18   46.58   46.69   46.69   46.83   46.61   46.61
   46.54   45.97   44.05   43.26   43.26   43.61   43.28    43.3   43.35   44.61
   45.51    44.9    45.4    45.4      46      46    45.2      46    46.1    45.4
    44.9    44.9    44.6      46    47.4
    45.9    44.8    44.9    45.5    44.6      45    44.5      45   44.37   44.36
   44.04    44.3   44.46   45.46    46.2   41.09   43.48   43.62    43.4   39.29
   40.84   45.97   43.88    43.1   43.07    43.6    42.9    42.9   43.34    44.6
    45.5    44.9    45.4    45.4      46      46    45.2      46    46.1    45.4
    44.9    44.9    44.6      46    47.4
  4345.1  4375.1  4395.1  4415.1  4445.1  4505.1  4655.1  4675.1  4691.4  4693.6
  4756.6  4801.6  4810.1 4863.01  4901.9 4912.11  4912.2  4999.2 5076.29  5076.4
  5098.7  5139.8  5212.4  5275.7    5278  5300.8  5310.8  5340.8  5348.6  5370.8
  5402.3  5442.3  5452.3  5492.3  5522.3  5552.3  5632.3  5652.3  5672.3  5689.1
  5699.1  5749.1  5809.1  5819.1  5824.8
    45.9    44.8    44.9    45.5    44.6      45    44.5      45   44.37   44.37
   45.28   45.96   46.09   46.18   46.58   46.69   46.69   46.83   46.61   46.61
   46.54   45.97   44.05   43.26   43.26   43.61   43.28    43.3   43.35   44.61
   45.51    44.9    45.4    45.4      46      46    45.2      46    46.1    45.4
    44.9    44.9    44.6      46    47.4
   45.86   44.76   44.86   45.46   44.56   44.96   44.46   44.96   44.33   44.32
      44   44.26   44.42   45.42   46.16   41.05   43.44   43.58   43.36   39.25
    40.8   45.93   43.84   43.06   43.03   43.56   42.86   42.86    43.3   44.56
   45.46   44.86   45.36   45.36   45.96   45.96   45.16   45.96   46.06   45.36
   44.86   44.86   44.56   45.96   47.36
Pier Skew, UpSta & Num, DnSta & Num=  ,4941, 2 ,4941, 2 , 0 , 0 , 0 ,,
     1.5     1.5
   34.92   44.53
     1.5     1.5
   34.88   44.49
Pier Skew, UpSta & Num, DnSta & Num=  ,4970.5, 2 ,4970.5, 2 , 0 , 0 , 0 ,,
     1.5     1.5
   23.37   44.57
     1.5     1.5
   23.33   44.53
Pier Skew, UpSta & Num, DnSta & Num=  ,4999.2, 2 ,4999.2, 2 , 0 , 0 , 0 ,,
     1.5     1.5
   17.44   44.62
     1.5     1.5
    17.4   44.58
Pier Skew, UpSta & Num, DnSta & Num=  ,5048.2, 2 ,5048.2, 2 , 0 , 0 , 0 ,,
     1.5     1.5
   29.47   44.48
     1.5     1.5
   29.43   44.44
Abutment Skew #Up #Dn= , 2 , 2
    4912  4913.9
   43.48   40.19
    4912  4913.9
   43.44   40.15
Abutment Skew #Up #Dn= , 2 , 2
  5073.9 5076.49
   39.12    43.4
  5073.9 5076.49
   39.08   43.36
BR Coef= 1 , 1 , 0 ,1.25, 0 ,,,.8,0,2,0,
WSPro=,,,, 1 ,,,, 0 ,,,, 0 ,,,,-1 ,-1 ,-1 , 0 , 0 , 0 , 0 , 0
BR U #Sta/Elev= 79
  4345.1    45.9  4375.1    44.8  4395.1    44.9  4415.1    45.5  4445.1    44.6
  4505.1      45  4615.1    44.6  4655.1    44.5  4675.1      45  4691.4   44.37
  4693.6   44.36  4756.6   44.04  4801.6    44.3  4810.1   44.46 4862.79   45.46
  4862.9   45.46 4863.01   45.46  4901.9    46.2    4912   41.14 4912.11   41.09
  4912.2   41.04  4913.8   40.24  4913.9   40.19  4915.7   39.89  4935.6   37.56
    4941   36.21    4955   30.85  4965.5   26.76  4970.5   24.49  4977.4   23.36
  4985.5   19.49    4993   18.31  4998.4   18.49  4999.2   18.52  5002.5   18.17
  5010.6   17.64  5014.5   19.53  5019.7   22.32  5036.6   26.78  5048.2   30.73
  5056.3   33.45  5073.8   39.09  5073.9   39.12 5076.29   39.29  5076.4   39.29
  5098.7   40.84  5100.3   41.04 5125.19   44.15  5125.3   44.16 5125.41   44.17
  5139.8   45.97  5139.9   45.97  5209.4   43.97  5212.4   43.88  5275.7    43.1
    5278   43.07  5300.8    43.6  5310.8    42.9  5340.8    42.9  5348.6   43.34
  5368.6   44.48  5370.8    44.6  5388.6   45.11  5402.3    45.5  5402.4    45.5
  5442.3    44.9  5452.3    45.4  5492.3    45.4  5522.3      46  5552.3      46
  5632.3    45.2  5652.3      46  5672.3    46.1  5689.1    45.4  5699.1    44.9
  5749.1    44.9  5809.1    44.6  5819.1      46  5824.8    47.4
BR U #Mann= 5
  4345.1      .2  4726.8      .1    4955    .045  5056.3      .1  5402.4      .2
BR U Banks=4955,5056.3
BR D #Sta/Elev= 79
  4345.1   45.86  4375.1   44.76  4395.1   44.86  4415.1   45.46  4445.1   44.56
  4505.1   44.96  4615.1   44.56  4655.1   44.46  4675.1   44.96  4691.4   44.33
  4693.6   44.32  4756.6      44  4801.6   44.26  4810.1   44.42 4862.79   45.42
  4862.9   45.42 4863.01   45.42  4901.9   46.16    4912    41.1 4912.11   41.05
  4912.2      41  4913.8    40.2  4913.9   40.15  4915.7   39.85  4935.6   37.52
    4941   36.17    4955   30.81  4965.5   26.72  4970.5   24.45  4977.4   23.32
  4985.5   19.45    4993   18.27  4998.4   18.45  4999.2   18.48  5002.5   18.13
  5010.6    17.6  5014.5   19.49  5019.7   22.28  5036.6   26.74  5048.2   30.69
  5056.3   33.41  5073.8   39.05  5073.9   39.08 5076.29   39.25  5076.4   39.25
  5098.7    40.8  5100.3      41 5125.19   44.11  5125.3   44.12 5125.41   44.13
  5139.8   45.93  5139.9   45.93  5209.4   43.93  5212.4   43.84  5275.7   43.06
    5278   43.03  5300.8   43.56  5310.8   42.86  5340.8   42.86  5348.6    43.3
  5368.6   44.44  5370.8   44.56  5388.6   45.07  5402.3   45.46  5402.4   45.46
  5442.3   44.86  5452.3   45.36  5492.3   45.36  5522.3   45.96  5552.3   45.96
  5632.3   45.16  5652.3   45.96  5672.3   46.06  5689.1   45.36  5699.1   44.86
  5749.1   44.86  5809.1   44.56  5819.1   45.96  5824.8   47.36
BR D #Mann= 5
  4345.1      .2  4726.8      .1    4955    .045  5056.3      .1  5402.4      .2
BR D Banks=4955,5056.3
BC Design=,, 0 ,, 0 ,,,,,,

Type RM Length L Ch R = 1 ,21304.0 ,293.6,293.6,293.6
BEGIN DESCRIPTION:
Downstream Section of Bridge/Culvert/Weir
END DESCRIPTION:
XS GIS Cut Line= 6
      3146361.35     13875882.83      3146230.16     13875541.75
      3146176.83     13875334.17      3146056.29      13875055.5
      3145929.41     13874926.44      3145565.88     13874725.82
#Sta/Elev= 30
  4345.1   45.88  4375.1   44.78  4415.1   45.48  4675.1   44.98  4756.6   44.02
  4901.9   46.18  4913.9   40.17  4935.6   37.54    4955   30.83  4970.5   24.47
  4977.4   23.34  4985.5   19.47  5010.6   17.62  5019.7    22.3  5036.6   26.76
  5056.3   33.43  5073.9    39.1  5098.7   40.82  5139.8   45.95  5212.4   43.86
  5310.8   42.88  5340.8   42.88  5402.4   45.48  5442.3   44.88  5552.3   45.98
  5632.3   45.18  5672.3   46.08  5699.1   44.88  5809.1   44.58  5824.8   47.38
#Mann= 5 , 1 , 0
  4345.1      .2       0  4726.8      .1       0    4955    .045       0
  5056.3      .1       0  5402.4      .2       0
#XS Ineff= 2 , 0
       0  4901.5    44.3  5087.1       0    43.1
Permanent Ineff=
       F       F
Bank Sta=4955,5056.3
XS Rating Curve= 0
Exp/Cntr=.5,.3

Type RM Length L Ch R = 1 ,21010.4 ,123,123,123
BEGIN DESCRIPTION:
Upstream Section of Bridge/Culvert/Weir
END DESCRIPTION:
XS GIS Cut Line= 6
      3146976.78     13875282.86      3146576.72     13875194.34
      3146272.31     13875085.81      3146116.14     13875011.69
      3145774.67      13874831.7      3145550.88     13874704.55
#Sta/Elev= 30
  4357.5   46.28  4451.4   44.48  4551.4   43.58    4650   44.38 4712.34   43.52
 4856.91   46.04 4868.04   41.74  4900.7   40.18 4954.82    26.2  4971.3   24.31
 4977.86   24.99 4982.04   19.15  4988.6   18.25 5010.66   18.08 5017.88   19.27
 5044.28    21.4 5045.51   25.71 5050.76   25.12 5079.46    27.8 5085.53   31.07
 5123.41    37.2 5135.94   42.28 5242.72   44.35 5284.38   43.75 5285.03   43.29
  5351.9   43.38  5381.9   44.28  5846.5   45.38  5896.5   47.88  5906.7   49.58
#Mann= 3 , 1 , 0
  4357.5      .1       0 4977.86    .045       0 5045.51      .1       0
#XS Ineff= 2 , 0
       0  4857.6    43.6    5155       0    44.5
Permanent Ineff=
       F       F
Bank Sta=4977.86,5045.51
XS Rating Curve= 0
Exp/Cntr=.5,.3

Type RM Length L Ch R = 3 ,20948.9 ,,,
BEGIN DESCRIPTION:
TIDWELL ROAD, SKEW ANGLE OF 35 DEGREES
Structure ID: P18-3
END DESCRIPTION:
Bridge Culvert--1,0,-1,-1, 0
Deck Dist Width WeirC Skew NumUp NumDn MinLoCord MaxHiCord MaxSubmerge Is_Ogee
10,103,2.6,0, 45, 45, , , .95, 0, 1,1,,
  4357.5  4367.5  4377.5  4387.5  4397.5  4417.5  4451.4  4501.4  4551.4  4571.4
  4601.4    4650 4668.97  4703.6 4712.34 4759.19  4759.3  4838.7 4856.91 4867.73
 4867.82  4983.7  5065.3  5123.1 5144.29  5144.4  5176.1  5191.8  5227.8  5233.5
 5233.61 5242.72 5284.38 5285.03  5346.5  5351.9  5381.9  5396.5  5476.5  5556.5
  5736.5  5846.5  5866.5  5896.5  5906.7
    46.3      46    46.1    45.7    45.9      45    44.5    43.9    43.6    43.9
    43.8   44.41    44.2   44.91   45.23   46.94   48.94   51.35   51.56   51.69
   51.69   53.03   52.94   52.47   52.47   52.47   52.47   51.76   50.13   49.93
   47.93   47.62   46.22    46.2   44.25   44.18   44.31   44.21   44.41   44.91
   44.81    45.4    46.8    47.9    49.6
    46.3      46    46.1    45.7    45.9      45    44.5    43.9    43.6    43.9
    43.8    44.4   43.74   43.58   43.54   44.08   44.08   45.69   46.06   41.88
   44.59   45.93   45.84   45.37   45.37    42.4   42.77   42.96   43.96   44.11
   44.12   44.37   43.77   43.31   43.41    43.4    44.3    44.2    44.4    44.9
    44.8    45.4    46.8    47.9    49.6
  4357.5  4367.5  4377.5  4387.5  4397.5  4417.5  4451.4  4501.4  4551.4  4571.4
  4601.4    4650 4668.97  4703.6 4712.34 4759.19  4759.3  4838.7 4856.91 4867.73
 4867.82  4983.7  5065.3  5123.1 5144.29  5144.4  5176.1  5191.8  5227.8  5233.5
 5233.61 5242.72 5284.38 5285.03  5346.5  5351.9  5381.9  5396.5  5476.5  5556.5
  5736.5  5846.5  5866.5  5896.5  5906.7
    46.3      46    46.1    45.7    45.9      45    44.5    43.9    43.6    43.9
    43.8   44.41    44.2   44.91   45.23   46.94   48.94   51.35   51.56   51.69
   51.69   53.03   52.94   52.47   52.47   52.47   52.47   51.76   50.13   49.93
   47.93   47.62   46.22    46.2   44.25   44.18   44.31   44.21   44.41   44.91
   44.81    45.4    46.8    47.9    49.6
   46.15   45.85   45.95   45.55   45.75   44.85   44.35   43.75   43.45   43.75
   43.65   44.25   43.59   43.43   43.39   43.93   43.93   45.54   45.91   41.73
   44.44   45.78   45.69   45.22   45.22   42.25   42.62   42.81   43.81   43.96
   43.97   44.22   43.62   43.16   43.26   43.25   44.15   44.05   44.25   44.75
   44.65   45.25   46.65   47.75   49.45
Pier Skew, UpSta & Num, DnSta & Num=  ,4954.8, 2 ,4954.8, 2 , 0 , 0 , 0 ,,
       3       3
   25.05   46.62
       3       3
    24.9   46.47
Pier Skew, UpSta & Num, DnSta & Num=  ,5045.5, 2 ,5045.5, 2 , 0 , 0 , 0 ,,
       3       3
    20.4   46.86
       3       3
   20.25   46.71
Abutment Skew #Up #Dn= , 2 , 2
 5136.04 5144.49
    42.3   45.37
 5136.04 5144.49
   42.15   45.22
BR Coef= 1 , 1 , 0 ,1.25, 0 ,,,.8,0,2,0,
WSPro=,,,, 1 ,,,, 0 ,,,, 0 ,,,,-1 ,-1 ,-1 , 0 , 0 , 0 , 0 , 0
BR U #Sta/Elev= 78
  4357.5    46.3  4367.5      46  4377.5    46.1  4387.5    45.7  4397.5    45.9
  4417.5      45  4451.4    44.5  4501.4    43.9  4551.4    43.6  4571.4    43.9
  4601.4    43.8  4648.8   44.39    4650    44.4 4668.97   43.74  4703.6   43.58
 4712.34   43.54 4755.31      44 4759.19   44.08  4759.3   44.08 4759.41   44.08
  4761.1   44.12  4838.7   45.69  4838.8   45.69 4856.91   46.06 4867.73   41.88
 4867.82   41.84 4868.04   41.76 4868.14   41.76  4900.7    40.2 4954.82   26.22
  4971.3   24.33 4977.86   25.01 4982.04   19.17  4983.7   18.94  4988.6   18.27
 4996.31   18.13 5010.66    18.1 5017.88   19.29 5044.28   21.42 5045.51   25.73
 5050.76   25.14  5065.3    26.5 5079.46   27.82 5085.53   31.09  5123.1   37.17
 5123.41   37.22 5135.94    42.3 5136.04    42.3 5144.29    42.4  5144.4    42.4
  5176.1   42.77  5191.8   42.96  5227.8   43.96 5233.39   44.11  5233.5   44.11
 5233.61   44.12 5242.72   44.37 5284.38   43.77 5285.03   43.31  5289.2   43.32
 5328.25   43.43  5346.5   43.41  5351.9    43.4  5381.9    44.3  5396.5    44.2
  5403.2   44.22  5476.5    44.4  5556.5    44.9  5646.1   44.85  5649.3   44.85
  5679.3   44.83  5699.3   44.82  5736.5    44.8  5779.7   45.04  5846.5    45.4
  5866.5    46.8  5896.5    47.9  5906.7    49.6
BR U #Mann= 3
  4357.5      .1 4977.86    .045 5045.51      .1
BR U Banks=4977.86,5045.51
BR D #Sta/Elev= 78
  4357.5   46.15  4367.5   45.85  4377.5   45.95  4387.5   45.55  4397.5   45.75
  4417.5   44.85  4451.4   44.35  4501.4   43.75  4551.4   43.45  4571.4   43.75
  4601.4   43.65  4648.8   44.24    4650   44.25 4668.97   43.59  4703.6   43.43
 4712.34   43.39 4755.31   43.85 4759.19   43.93  4759.3   43.93 4759.41   43.93
  4761.1   43.97  4838.7   45.54  4838.8   45.54 4856.91   45.91 4867.73   41.73
 4867.82   41.69 4868.04   41.61 4868.14   41.61  4900.7   40.05 4954.82   26.07
  4971.3   24.18 4977.86   24.86 4982.04   19.02  4983.7   18.79  4988.6   18.12
 4996.31   17.98 5010.66   17.95 5017.88   19.14 5044.28   21.27 5045.51   25.58
 5050.76   24.99  5065.3   26.35 5079.46   27.67 5085.53   30.94  5123.1   37.02
 5123.41   37.07 5135.94   42.15 5136.04   42.15 5144.29   42.25  5144.4   42.25
  5176.1   42.62  5191.8   42.81  5227.8   43.81 5233.39   43.96  5233.5   43.96
 5233.61   43.97 5242.72   44.22 5284.38   43.62 5285.03   43.16  5289.2   43.17
 5328.25   43.28  5346.5   43.26  5351.9   43.25  5381.9   44.15  5396.5   44.05
  5403.2   44.07  5476.5   44.25  5556.5   44.75  5646.1    44.7  5649.3    44.7
  5679.3   44.68  5699.3   44.67  5736.5   44.65  5779.7   44.89  5846.5   45.25
  5866.5   46.65  5896.5   47.75  5906.7   49.45
BR D #Mann= 3
  4357.5      .1 4977.86    .045 5045.51      .1
BR D Banks=4977.86,5045.51
BC Design=,, 0 ,, 0 ,,,,,,

Type RM Length L Ch R = 1 ,20887.4 ,6.8,6.8,6.8
BEGIN DESCRIPTION:
Downstream Section of Bridge/Culvert/Weir
END DESCRIPTION:
XS GIS Cut Line= 6
      3147079.63     13875215.39      3146679.56     13875126.88
      3146375.15     13875018.35      3146218.98     13874944.23
      3145877.51     13874764.24      3145653.73     13874637.09
#Sta/Elev= 30
  4357.5   46.16  4451.4   44.36  4551.4   43.46    4650   44.26 4712.34    43.4
 4856.91   45.92 4868.04   41.62  4900.7   40.06 4954.82   26.08  4971.3   24.19
 4977.86   24.87 4982.04   19.03  4988.6   18.13 5010.66   17.96 5017.88   19.15
 5044.28   21.28 5045.51   25.59 5050.76      25 5079.46   27.68 5085.53   30.95
 5123.41   37.08 5135.94   42.16 5242.72   44.23 5284.38   43.63 5285.03   43.17
  5351.9   43.26  5381.9   44.16  5846.5   45.26  5896.5   47.76  5906.7   49.46
#Mann= 3 , 1 , 0
  4357.5      .1       0 4977.86    .045       0 5045.51      .1       0
#XS Ineff= 2 , 0
       0  4857.6    43.4    5155       0    44.3
Permanent Ineff=
       F       F
Bank Sta=4977.86,5045.51
XS Rating Curve= 0
Exp/Cntr=.5,.3

Type RM Length L Ch R = 1 ,20880.6 ,22,22,22
BEGIN DESCRIPTION:
Upstream Section of Bridge/Culvert/Weir
END DESCRIPTION:
XS GIS Cut Line= 4
      3147114.41     13875214.41      3146525.14     13875030.63
       3146459.4     13875004.34      3145676.18      13874646.4
#Sta/Elev= 30
  4357.5   46.29  4511.4   43.29    4670   44.09    4720   45.09    4780   47.79
    4810   46.59    4820   45.09  4856.2   45.44 4897.28   40.19 4948.28   29.66
 4974.03   25.83 4984.85   21.54 4988.54   19.03 4995.27   17.96 5011.42      19
 5015.93   21.43 5033.81   25.32 5082.11   31.89 5139.75   42.42 5183.62   47.81
 5222.24   48.09    5300   45.49  5351.9   43.39  5381.9   44.29  5546.5   43.79
  5556.5   44.89  5766.5   43.99  5846.5   45.39  5896.5   47.89  5906.7   49.59
#Mann= 4 , 1 , 0
  4357.5      .1       0 4974.03    .045       0 5033.81      .1       0
    5300     .99       0
#XS Ineff= 2 , 0
       0  4844.3    43.4    5170       0    44.1
Permanent Ineff=
       F       F
Bank Sta=4974.03,5033.81
XS Rating Curve= 0
Exp/Cntr=.5,.3

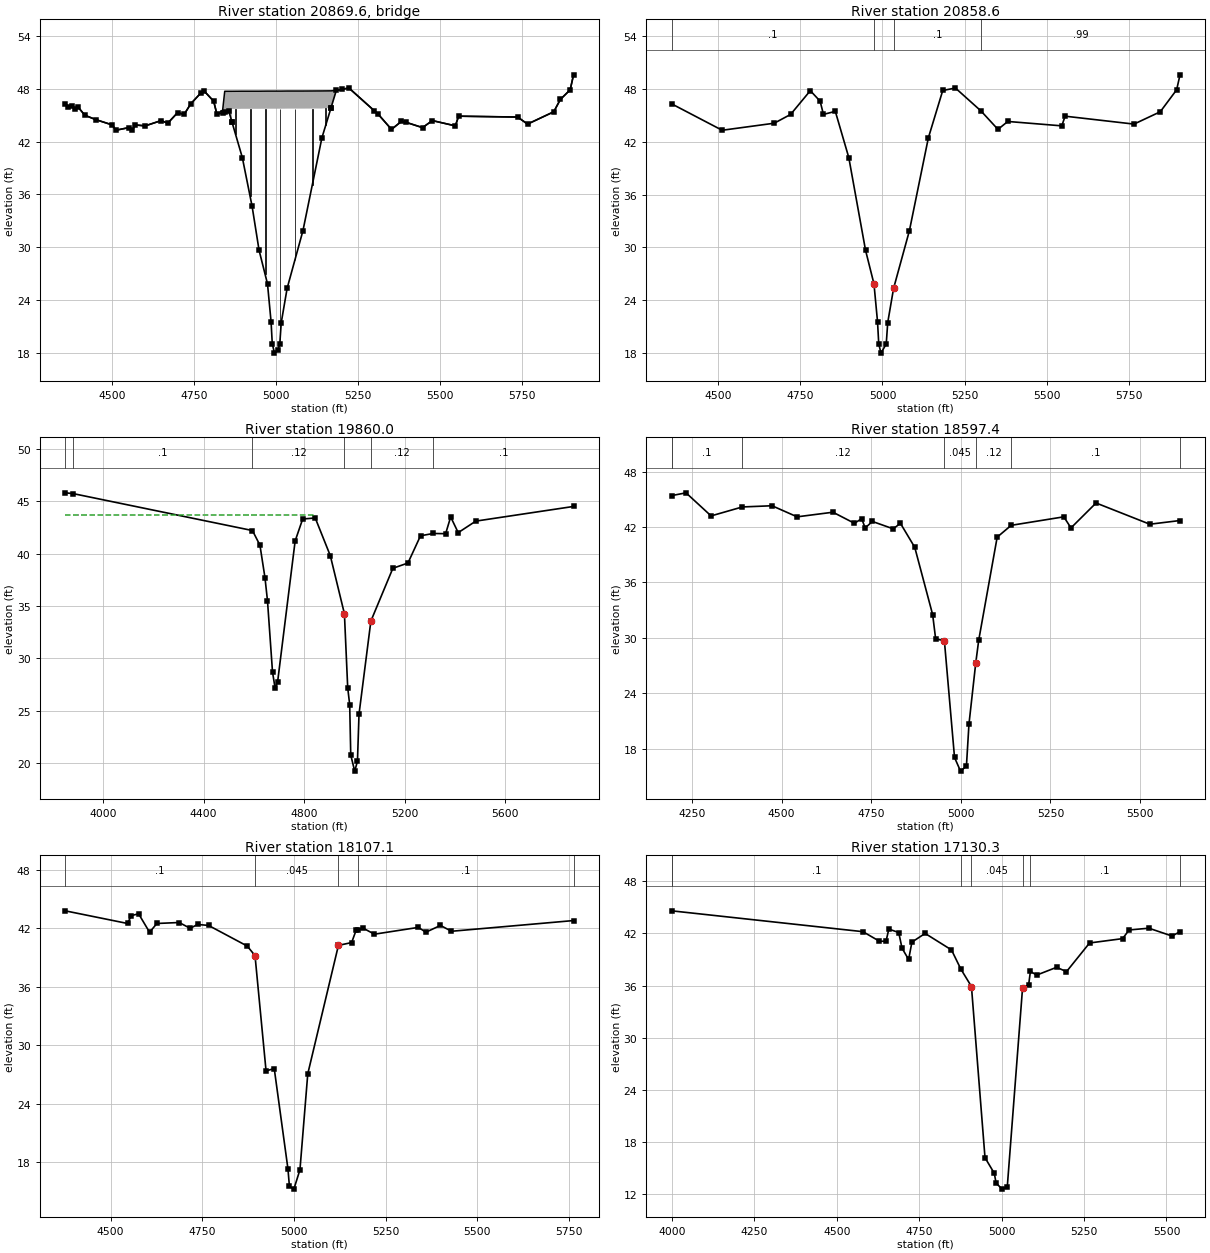
Type RM Length L Ch R = 3 ,20869.6 ,,,
BEGIN DESCRIPTION:
24" PIPELINE, SKEW ANGLE OF 35 DEGREES
END DESCRIPTION:
Bridge Culvert--1,0,-1,-1, 0
Deck Dist Width WeirC Skew NumUp NumDn MinLoCord MaxHiCord MaxSubmerge Is_Ogee
10,2,2.6,0, 60, 60, , , .95, 0, 1,1,,
  4357.5  4367.5  4377.5  4387.5  4397.5  4417.5  4451.4  4501.4  4511.4  4551.4
  4561.4  4571.4  4601.4    4650    4670    4700    4720    4740    4770    4780
    4810    4820 4837.33 4843.63  4856.2 4865.45 4865.54 4897.28 4927.13 4948.28
 4974.03 4984.85 4988.54 4995.27 5005.35 5011.42 5015.93 5033.81 5082.11 5139.75
 5167.69  5167.8 5183.62 5201.23 5222.24    5300  5311.9  5351.9  5381.9  5396.5
  5446.5  5476.5  5546.5  5556.5  5736.5  5766.5  5846.5  5866.5  5896.5  5906.7
    46.3      46    46.1    45.7    45.9      45    44.5    43.9    43.3    43.6
    43.3    43.9    43.8    44.4    44.1    45.3    45.1    46.3    47.5    47.8
    46.6    45.1    45.6   47.73   47.73   47.73   47.73   47.74   47.74   47.74
   47.75   47.75   47.75   47.75   47.75   47.75   47.75   47.76   47.76   47.77
   47.78   47.78   47.83   47.96    48.1    45.5    45.1    43.4    44.3    44.2
    43.6    44.4    43.8    44.9    44.8      44    45.4    46.8    47.9    49.6
    46.3      46    46.1    45.7    45.9      45    44.5    43.9    43.3    43.6
    43.3    43.9    43.8    44.4    44.1    45.3    45.1    46.3    47.5    47.8
    46.6    45.1   45.27   45.33   45.45   44.27   45.73   45.74   45.74   45.74
   45.75   45.75   45.75   45.75   45.75   45.75   45.75   45.76   45.76   45.77
   45.86   45.88   47.82   47.95    48.1    45.5    45.1    43.4    44.3    44.2
    43.6    44.4    43.8    44.9    44.8      44    45.4    46.8    47.9    49.6
  4357.5  4367.5  4377.5  4387.5  4397.5  4417.5  4451.4  4501.4  4511.4  4551.4
  4561.4  4571.4  4601.4    4650    4670    4700    4720    4740    4770    4780
    4810    4820 4837.33 4843.63  4856.2 4865.45 4865.54 4897.28 4927.13 4948.28
 4974.03 4984.85 4988.54 4995.27 5005.35 5011.42 5015.93 5033.81 5082.11 5139.75
 5167.69  5167.8 5183.62 5201.23 5222.24    5300  5311.9  5351.9  5381.9  5396.5
  5446.5  5476.5  5546.5  5556.5  5736.5  5766.5  5846.5  5866.5  5896.5  5906.7
    46.3      46    46.1    45.7    45.9      45    44.5    43.9    43.3    43.6
    43.3    43.9    43.8    44.4    44.1    45.3    45.1    46.3    47.5    47.8
    46.6    45.1    45.6   47.73   47.73   47.73   47.73   47.74   47.74   47.74
   47.75   47.75   47.75   47.75   47.75   47.75   47.75   47.76   47.76   47.77
   47.78   47.78   47.83   47.96    48.1    45.5    45.1    43.4    44.3    44.2
    43.6    44.4    43.8    44.9    44.8      44    45.4    46.8    47.9    49.6
    46.3      46    46.1    45.7    45.9      45    44.5    43.9    43.3    43.6
    43.3    43.9    43.8    44.4    44.1    45.3    45.1    46.3    47.5    47.8
    46.6    45.1   45.27   45.33   45.45   44.27   45.73   45.74   45.74   45.74
   45.75   45.75   45.75   45.75   45.75   45.75   45.75   45.76   45.76   45.77
   45.86   45.88   47.82   47.95    48.1    45.5    45.1    43.4    44.3    44.2
    43.6    44.4    43.8    44.9    44.8      44    45.4    46.8    47.9    49.6
Pier Skew, UpSta & Num, DnSta & Num=  ,4876, 2 ,4876, 2 , 0 , 0 , 0 ,,
     2.5     2.5
   41.77   46.73
     2.5     2.5
   41.77   46.73
Pier Skew, UpSta & Num, DnSta & Num=  ,4921, 2 ,4921, 2 , 0 , 0 , 0 ,,
     2.5     2.5
   34.56   46.74
     2.5     2.5
   34.56   46.74
Pier Skew, UpSta & Num, DnSta & Num=  ,4966.8, 2 ,4966.8, 2 , 0 , 0 , 0 ,,
     2.5     2.5
   25.73   46.75
     2.5     2.5
   25.73   46.75
Pier Skew, UpSta & Num, DnSta & Num=  ,5012.2, 2 ,5012.2, 2 , 0 , 0 , 0 ,,
     2.5     2.5
   17.95   46.75
     2.5     2.5
   17.95   46.75
Pier Skew, UpSta & Num, DnSta & Num=  ,5057.8, 2 ,5057.8, 2 , 0 , 0 , 0 ,,
     2.5     2.5
   27.43   46.76
     2.5     2.5
   27.43   46.76
Pier Skew, UpSta & Num, DnSta & Num=  ,5110.6, 2 ,5110.6, 2 , 0 , 0 , 0 ,,
     2.5     2.5
   35.87   46.77
     2.5     2.5
   35.87   46.77
Pier Skew, UpSta & Num, DnSta & Num=  ,5151.8, 2 ,5151.8, 2 , 0 , 0 , 0 ,,
     2.5     2.5
   42.76   46.81
     2.5     2.5
   42.76   46.81
BR Coef= 1 , 1 , 0 ,1.25, 0 ,,,.8,0,2,0,
WSPro=,,,, 1 ,,,, 0 ,,,, 0 ,,,,-1 ,-1 ,-1 , 0 , 0 , 0 , 0 , 0
BR U #Sta/Elev= 60
  4357.5    46.3  4367.5      46  4377.5    46.1  4387.5    45.7  4397.5    45.9
  4417.5      45  4451.4    44.5  4501.4    43.9  4511.4    43.3  4551.4    43.6
  4561.4    43.3  4571.4    43.9  4601.4    43.8    4650    44.4    4670    44.1
    4700    45.3    4720    45.1    4740    46.3    4770    47.5    4780    47.8
    4810    46.6    4820    45.1 4837.33   45.27 4843.63   45.33  4856.2   45.45
 4865.45   44.27 4865.54   44.26 4897.28    40.2 4927.13   34.65 4948.28   29.67
 4974.03   25.84 4984.85   21.55 4988.54   19.04 4995.27   17.97 5005.35   18.27
 5011.42   19.01 5015.93   21.44 5033.81   25.33 5082.11    31.9 5139.75   42.43
 5167.69   45.86  5167.8   45.88 5183.62   47.82 5201.23   47.95 5222.24    48.1
    5300    45.5  5311.9    45.1  5351.9    43.4  5381.9    44.3  5396.5    44.2
  5446.5    43.6  5476.5    44.4  5546.5    43.8  5556.5    44.9  5736.5    44.8
  5766.5      44  5846.5    45.4  5866.5    46.8  5896.5    47.9  5906.7    49.6
BR U #Mann= 4
  4357.5      .1 4974.03     .04 5033.81      .1    5300     .99
BR U Banks=4974.03,5033.81
BR D #Sta/Elev= 60
  4357.5    46.3  4367.5      46  4377.5    46.1  4387.5    45.7  4397.5    45.9
  4417.5      45  4451.4    44.5  4501.4    43.9  4511.4    43.3  4551.4    43.6
  4561.4    43.3  4571.4    43.9  4601.4    43.8    4650    44.4    4670    44.1
    4700    45.3    4720    45.1    4740    46.3    4770    47.5    4780    47.8
    4810    46.6    4820    45.1 4837.33   45.27 4843.63   45.33  4856.2   45.45
 4865.45   44.27 4865.54   44.26 4897.28    40.2 4927.13   34.65 4948.28   29.67
 4974.03   25.84 4984.85   21.55 4988.54   19.04 4995.27   17.97 5005.35   18.27
 5011.42   19.01 5015.93   21.44 5033.81   25.33 5082.11    31.9 5139.75   42.43
 5167.69   45.86  5167.8   45.88 5183.62   47.82 5201.23   47.95 5222.24    48.1
    5300    45.5  5311.9    45.1  5351.9    43.4  5381.9    44.3  5396.5    44.2
  5446.5    43.6  5476.5    44.4  5546.5    43.8  5556.5    44.9  5736.5    44.8
  5766.5      44  5846.5    45.4  5866.5    46.8  5896.5    47.9  5906.7    49.6
BR D #Mann= 4
  4357.5      .1 4974.03     .04 5033.81      .1    5300     .99
BR D Banks=4974.03,5033.81
BC Design=,, 0 ,, 0 ,,,,,,

Type RM Length L Ch R = 1 ,20858.6 ,998.6,998.6,998.6
BEGIN DESCRIPTION:
Downstream Section of Bridge/Culvert/Weir
END DESCRIPTION:
XS GIS Cut Line= 4
       3147132.8     13875202.35      3146543.54     13875018.57
       3146477.8     13874992.28      3145694.57     13874634.34
#Sta/Elev= 30
  4357.5   46.31  4511.4   43.31    4670   44.11    4720   45.11    4780   47.81
    4810   46.61    4820   45.11  4856.2   45.46 4897.28   40.21 4948.28   29.68
 4974.03   25.85 4984.85   21.56 4988.54   19.05 4995.27   17.98 5011.42   19.02
 5015.93   21.45 5033.81   25.34 5082.11   31.91 5139.75   42.44 5183.62   47.83
 5222.24   48.11    5300   45.51  5351.9   43.41  5381.9   44.31  5546.5   43.81
  5556.5   44.91  5766.5   44.01  5846.5   45.41  5896.5   47.91  5906.7   49.61
#Mann= 4 , 1 , 0
  4357.5      .1       0 4974.03    .045       0 5033.81      .1       0
    5300     .99       0
#XS Ineff= 2 , 0
       0  4844.3    43.4    5175       0    44.1
Permanent Ineff=
       F       F
Bank Sta=4974.03,5033.81
XS Rating Curve= 0
Exp/Cntr=.5,.3

Type RM Length L Ch R = 1 ,19860.0 ,1289.7,1262.6,1239.7
BEGIN DESCRIPTION:
Cross Section 19860.0
END DESCRIPTION:
XS GIS Cut Line= 5
      3147766.57     13875965.71      3147620.03     13875347.87
      3147467.36     13874947.09      3147472.13     13874298.22
      3147291.75     13874046.15
#Sta/Elev= 30
  3849.7    45.8  3880.3   45.73  4594.8    42.2  4624.6    40.8  4644.6    37.7
  4654.6    35.5  4674.6    28.7  4684.6    27.2  4694.6    27.7  4764.6    41.2
  4794.6    43.3  4844.6    43.4  4904.6    39.8  4960.7   34.26  4973.8    27.2
  4981.7   25.58  4985.9   20.78  5001.6   19.24  5012.6   20.18  5018.8   24.68
    5066   33.56  5153.5    38.6  5213.5    39.1  5263.5    41.7  5313.9   41.92
  5363.5    41.9  5383.5    43.5  5413.5      42  5483.5    43.1  5872.4    44.5
#Mann= 6 , 1 , 0
  3849.7      .2       0  3880.3      .1       0  4594.8     .12       0
  4960.7    .045       0    5066     .12       0  5313.9      .1       0
#XS Ineff= 2 , 0
       0  4834.6    43.7               0
Permanent Ineff=
       F       F
Bank Sta=4960.7,5066
XS Rating Curve= 0
Exp/Cntr=.3,.1

Type RM Length L Ch R = 1 ,18597.4 ,571.8,490.3,322.7
BEGIN DESCRIPTION:
Cross Section 18597.4
END DESCRIPTION:
XS GIS Cut Line= 4
      3148893.92       13875491.       3148765.1     13874937.55
      3148679.22     13874551.09      3148292.76     13874312.54
#Sta/Elev= 30
  4193.2    45.4  4233.2    45.7  4303.2    43.2  4390.3   44.17  4473.2    44.3
  4543.2    43.1  4643.2    43.6  4703.2    42.4  4723.2    42.9  4733.2    41.9
  4753.2    42.6  4811.4    41.8  4831.4    42.4  4871.4    39.8  4921.4    32.5
  4929.7   29.88  4954.1   29.68  4982.4   17.04  4999.1   15.56  5015.6    16.1
  5022.7   20.66  5041.6   27.27  5049.9   29.74  5101.4    40.9  5140.5   42.18
  5287.3    43.1  5307.3    41.9  5377.3    44.6  5527.3    42.3  5611.5    42.7
#Mann= 7 , 1 , 0
  4193.2      .2       0  4193.2      .1       0  4390.3     .12       0
  4954.1    .045       0  5041.6     .12       0  5140.5      .1       0
  5611.5      .2       0
Bank Sta=4954.1,5041.6
XS Rating Curve= 0
Exp/Cntr=.3,.1

Type RM Length L Ch R = 1 ,18107.1 ,877.6,976.8,1087.3
BEGIN DESCRIPTION:
Cross Section 18107.1
END DESCRIPTION:
XS GIS Cut Line= 4
      3149604.56     13874733.06      3149418.74     13874522.47
      3149003.65     13874369.79      3148345.24     13874293.45
#Sta/Elev= 30
  4376.3    43.8  4546.3    42.5  4556.3    43.3  4576.3    43.5  4606.3    41.6
  4626.3    42.5  4687.1    42.6  4717.1      42  4737.1    42.4  4767.1    42.3
  4872.6   40.18  4893.8    39.2  4923.9   27.35  4946.2    27.6  4983.6   17.28
  4987.6   15.49  4999.7   15.21  5016.3    17.2  5037.6   27.05  5121.2   40.25
  5157.2   40.54  5169.4    41.8  5175.1   41.86  5189.4      42  5219.4    41.4
  5339.4    42.1  5359.4    41.6  5399.4    42.3  5429.4    41.7  5762.2    42.8
#Mann= 5 , 1 , 0
  4376.3      .1       0  4893.8    .045       0  5121.2     .12       0
  5175.1      .1       0  5762.2      .2       0
Bank Sta=4893.8,5121.2
XS Rating Curve= 0
Exp/Cntr=.3,.1

Type RM Length L Ch R = 1 ,17130.3 ,1132.9,1126.3,1043.2
BEGIN DESCRIPTION:
Cross Section 17130.3
END DESCRIPTION:
XS GIS Cut Line= 5
      3149857.68     13874589.26      3149867.22     13873930.85
      3149671.61     13873778.17      3149533.25     13873606.41
      3149361.49      13873229.5
#Sta/Elev= 30
  3999.6    44.6  4579.6    42.2  4629.6    41.1  4649.6    41.1  4658.1    42.5
  4688.1    42.1  4698.1    40.3  4718.1      39  4728.1      41  4768.1      42
  4848.1    40.1  4876.4    37.9  4908.6   35.89  4949.7   16.19  4977.9   14.39
  4983.3   13.27  5001.6   12.57  5017.2   12.81  5063.6   35.74    5082   36.07
  5087.4   37.64  5106.2    37.2  5166.8    38.1  5196.8    37.6  5266.8    40.9
  5366.8    41.4  5386.8    42.4  5446.8    42.6  5516.8    41.7    5541    42.2
#Mann= 7 , 1 , 0
  3999.6      .2       0  3999.6      .1       0  4876.4     .07       0
  4908.6    .045       0  5063.6     .07       0  5087.4      .1       0
    5541      .2       0
Bank Sta=4908.6,5063.6
XS Rating Curve= 0
Exp/Cntr=.3,.1

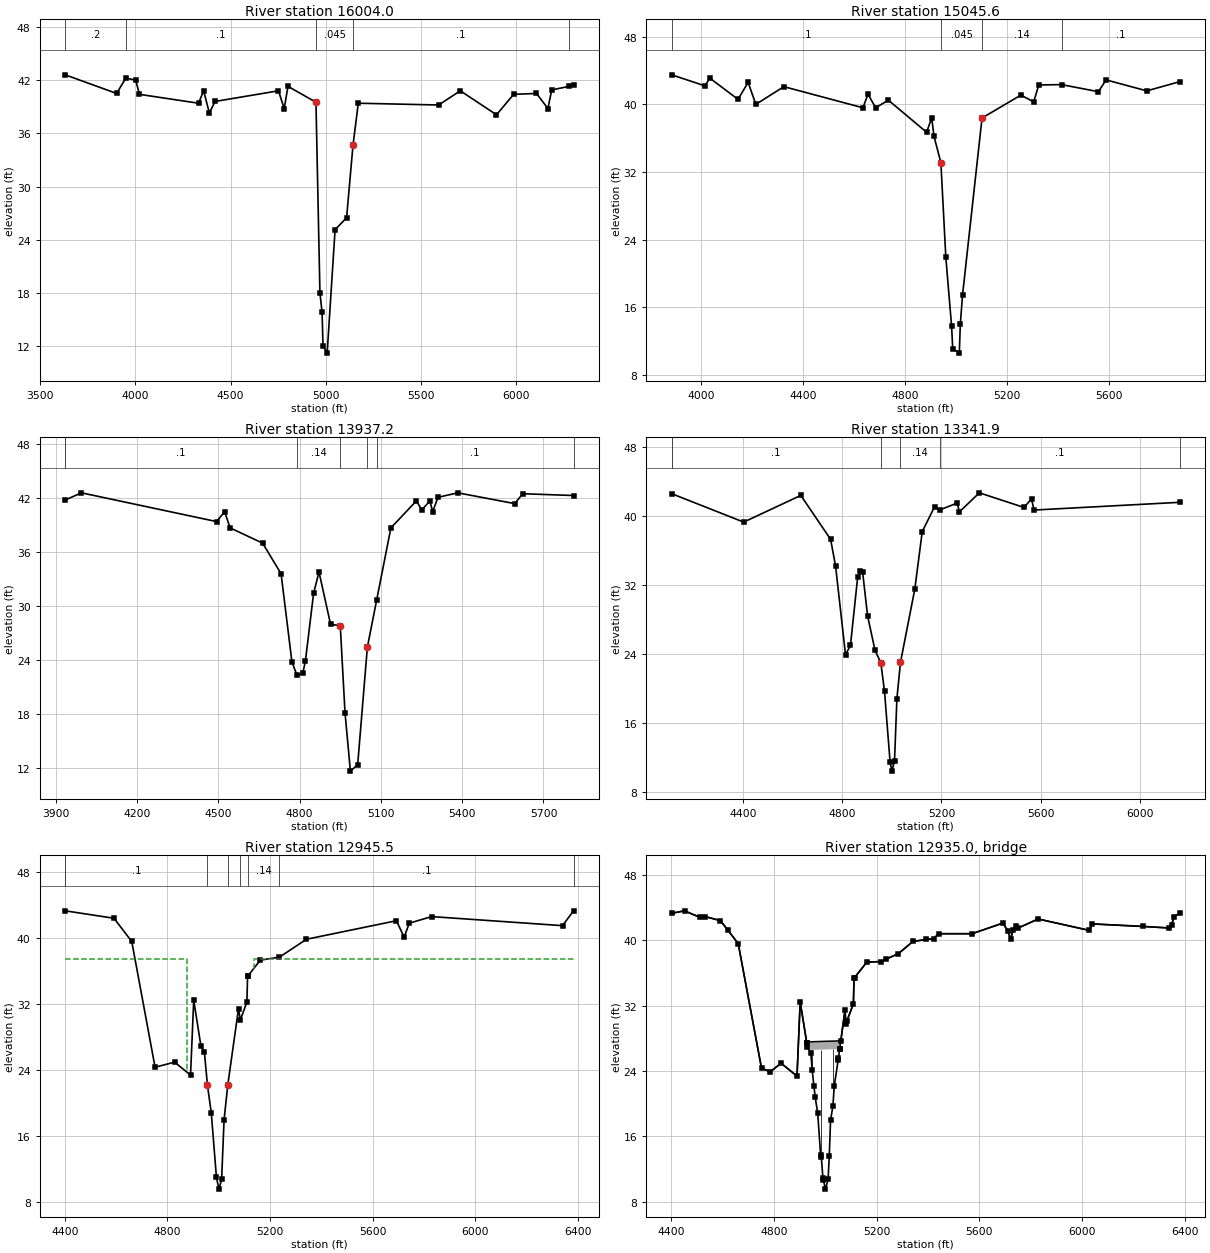
Type RM Length L Ch R = 1 ,16004.0 ,856.4,958.4,1214.4
BEGIN DESCRIPTION:
Cross Section 16004.0
END DESCRIPTION:
XS GIS Cut Line= 6
      3150664.67     13874794.21      3151006.01     13874175.29
      3150902.44     13873775.44      3150438.39     13873460.24
        3150268.     13873105.45      3150038.98     13872556.77
#Sta/Elev= 30
  3631.7    42.6  3901.7    40.5  3949.6   42.23  4001.7      42  4021.7    40.4
  4331.7    39.4  4358.5    40.8  4388.5    38.3  4418.5    39.6  4751.5    40.8
  4781.5    38.8  4801.5    41.3  4948.3   39.51  4969.2   18.01  4980.5   15.82
  4985.3   12.05  5007.1   11.24  5048.7   25.15  5109.1    26.5  5142.8   34.68
  5170.6    39.4  5592.6    39.2  5706.2    40.8  5896.2    38.1  5986.2    40.4
  6106.2    40.5  6166.2    38.8  6186.2    40.9  6277.2    41.3  6300.7    41.4
#Mann= 5 , 1 , 0
  3631.7      .2       0  3949.6      .1       0  4948.3    .045       0
  5142.8      .1       0  6277.2      .2       0
#XS Ineff= 2 , 0
       0  4358.5    40.8  5706.2       0    40.8
Permanent Ineff=
       F       F
Bank Sta=4948.3,5142.8
XS Rating Curve= 0
Exp/Cntr=.3,.1

Type RM Length L Ch R = 1 ,15045.6 ,1149.2,1108.4,1021.1
BEGIN DESCRIPTION:
Cross Section 15045.6
END DESCRIPTION:
XS GIS Cut Line= 5
      3150657.96     13874874.74      3151145.88     13874178.95
      3151370.12     13873897.45      3151541.88     13873611.19
      3151606.82     13873165.86
#Sta/Elev= 30
  3885.1    43.5  4015.1    42.2  4035.1    43.1  4145.1    40.6  4185.1    42.6
  4215.1      40  4325.1    42.1  4635.1    39.6  4655.1    41.2  4685.1    39.6
  4734.9    40.5  4884.9    36.7  4904.9    38.4  4913.8   36.23  4940.9    33.1
  4960.2   21.94  4982.9   13.75  4987.3   11.09  5013.2   10.55  5017.1   13.95
  5025.8   17.43  5102.3   38.39  5254.8    41.1  5304.8    40.3  5324.8    42.3
  5414.5   42.34  5558.7    41.5  5588.7    42.9  5748.7    41.6  5878.7    42.7
#Mann= 4 , 1 , 0
  3885.1      .1       0  4940.9    .045       0  5102.3     .14       0
  5414.5      .1       0
Bank Sta=4940.9,5102.3
XS Rating Curve= 0
Exp/Cntr=.3,.1

Type RM Length L Ch R = 1 ,13937.2 ,540.2,595.3,633.4
BEGIN DESCRIPTION:
Cross Section 13937.2
END DESCRIPTION:
XS GIS Cut Line= 6
      3152257.55     13875405.12      3152352.97     13874956.64
      3152290.94     13874474.76      3152300.49     13874193.26
      3152262.32     13873973.79      3152214.61     13873549.16
#Sta/Elev= 30
  3934.8    41.8  3994.8    42.6  4493.3    39.4  4523.3    40.5  4543.3    38.7
  4663.3      37  4731.5    33.6  4771.5    23.8  4790.4   22.27  4811.5    22.5
  4821.5    23.9  4851.5    31.4  4871.5    33.8  4914.1   27.97    4950    27.8
  4967.6    18.1  4987.4   11.62  5014.3   12.34    5050   25.41  5084.5   30.69
  5136.9    38.7  5230.9    41.7  5250.9    40.7  5280.9    41.7  5290.9    40.5
  5310.9    42.1  5383.7    42.6  5593.7    41.4  5623.7    42.5    5811    42.3
#Mann= 7 , 1 , 0
  3934.8      .2       0  3934.8      .1       0  4790.4     .14       0
    4950    .045       0    5050     .14       0  5084.5      .1       0
    5811      .2       0
Bank Sta=4950,5050
XS Rating Curve= 0
Exp/Cntr=.3,.1

Type RM Length L Ch R = 1 ,13341.9 ,432.1,396.4,372.8
BEGIN DESCRIPTION:
Cross Section 13341.9-Interpolated
END DESCRIPTION:
XS GIS Cut Line= 4
      3152413.22      13875452.4      3152717.33     13874779.01
      3152853.09     13874545.49      3152891.11     13873508.25
#Sta/Elev= 30
  4113.6    42.6  4403.6    39.3  4633.6    42.4  4753.6    37.3  4773.6    34.2
  4813.6    23.9  4833.6      25  4862.5    32.9  4872.5    33.6  4882.5    33.5
  4902.5    28.4  4932.5    24.4 4955.72   22.98 4970.62   19.65 4993.02   11.45
 5000.52   10.38 5010.92   11.56 5020.52   18.79 5034.92   23.01  5092.5    31.5
  5122.6    38.2  5172.6    41.1  5192.1   40.71  5262.6    41.5  5272.6    40.5
  5352.6    42.7  5532.6      41  5562.6      42  5572.6    40.7  6160.5    41.6
#Mann= 6 , 1 , 0
  4113.6      .2       0  4113.6      .1       0 4955.72    .045       0
 5034.92     .14       0  5192.1      .1       0  6160.5      .2       0
Bank Sta=4955.72,5034.92
XS Rating Curve= 0
Exp/Cntr=.5,.3

Type RM Length L Ch R = 1 ,12945.5 ,13.8,13.8,13.8
BEGIN DESCRIPTION:
Upstream Section of Bridge/Culvert/Weir
END DESCRIPTION:
XS GIS Cut Line= 5
      3152940.17     13875432.57      3153085.73     13874995.89
      3153089.72     13874873.76      3153085.73     13874043.96
      3152948.88     13873492.39
#Sta/Elev= 30
  4401.5   43.32  4591.5   42.42 4660.82    39.6 4751.62   24.34 4827.72   24.96
 4889.82   23.39 4902.22   32.47 4930.32   26.91 4943.62   26.24 4955.72   22.15
 4970.62   18.82 4990.72   10.97 5000.52    9.55 5010.92   10.73 5020.52   17.96
 5034.92   22.18 5076.72   31.45  5083.8   30.08 5109.52   32.25 5112.02   35.36
  5114.2   35.45 5161.82   37.34  5235.8   37.69 5341.52   39.87  5692.1   42.12
  5722.1   40.12  5742.1   41.82  5829.3   42.62  6339.3   41.52  6382.1   43.32
#Mann= 8 , 1 , 0
  4401.5      .2       0  4401.5      .1       0 4955.72    .045       0
 5034.92     .14       0  5083.8      .1       0  5114.2     .14       0
  5235.8      .1       0  6382.1      .2       0
#XS Ineff= 2 , 0
       0    4875    37.5  5135.5       0    37.5
Permanent Ineff=
       F       F
Bank Sta=4955.72,5034.92
XS Rating Curve= 0
Exp/Cntr=.5,.3

Type RM Length L Ch R = 3 ,12935.0 ,,,
BEGIN DESCRIPTION:
12" PIPELINE
END DESCRIPTION:
Bridge Culvert--1,0,-1,-1, 0
Deck Dist Width WeirC Skew NumUp NumDn MinLoCord MaxHiCord MaxSubmerge Is_Ogee
10,1,2.6,0, 40, 40, , , .95, 0, 1,1,,
  4401.5  4451.5  4511.5  4531.5  4591.5 4660.82 4751.62 4786.02 4827.72 4889.82
 4902.22 4927.72 4930.32 4943.62 5056.11 5060.42 5076.72 5080.52 5109.52 5112.02
 5161.82 5216.12 5285.22 5341.52  5422.1  5442.1  5572.1  5692.1  5712.1  5722.1
  5732.1  5742.1  5752.1  5829.3  6029.3  6039.3  6339.3  6349.3  6359.3  6382.1
    43.3    43.6    42.8    42.9    42.4   39.58   24.32   23.91   24.94   23.37
   32.45   27.56   27.56   27.57   27.68   27.68   31.43   29.78   32.23   35.34
   37.32   37.39   38.37   39.85    40.2    40.8    40.8    42.1    41.1    40.1
    41.3    41.8    41.5    42.6    41.2      42    41.5    41.9    42.9    43.3
    43.3    43.6    42.8    42.9    42.4   39.58   24.32   23.91   24.94   23.37
   32.45    27.4   26.89   26.57   26.68   27.67   31.43   29.78   32.23   35.34
   37.32   37.39   38.37   39.85    40.2    40.8    40.8    42.1    41.1    40.1
    41.3    41.8    41.5    42.6    41.2      42    41.5    41.9    42.9    43.3
  4401.5  4451.5  4511.5  4531.5  4591.5 4660.82 4751.62 4786.02 4827.72 4889.82
 4902.22 4927.72 4930.32 4943.62 5056.11 5060.42 5076.72 5080.52 5109.52 5112.02
 5161.82 5216.12 5285.22 5341.52  5422.1  5442.1  5572.1  5692.1  5712.1  5722.1
  5732.1  5742.1  5752.1  5829.3  6029.3  6039.3  6339.3  6349.3  6359.3  6382.1
    43.3    43.6    42.8    42.9    42.4   39.58   24.32   23.91   24.94   23.37
   32.45   27.56   27.56   27.57   27.68   27.68   31.43   29.78   32.23   35.34
   37.32   37.39   38.37   39.85    40.2    40.8    40.8    42.1    41.1    40.1
    41.3    41.8    41.5    42.6    41.2      42    41.5    41.9    42.9    43.3
    43.3    43.6    42.8    42.9    42.4   39.58   24.32   23.91   24.94   23.37
   32.45    27.4   26.89   26.57   26.68   27.67   31.43   29.78   32.23   35.34
   37.32   37.39   38.37   39.85    40.2    40.8    40.8    42.1    41.1    40.1
    41.3    41.8    41.5    42.6    41.2      42    41.5    41.9    42.9    43.3
Pier Skew, UpSta & Num, DnSta & Num=  ,4948.7, 2 ,4948.7, 2 , 0 , 0 , 0 ,,
      .8      .8
   23.04   27.58
      .8      .8
   23.04   27.58
Pier Skew, UpSta & Num, DnSta & Num=  ,4981.8, 2 ,4981.8, 2 , 0 , 0 , 0 ,,
      .8      .8
   12.63   27.61
      .8      .8
   12.63   27.61
Pier Skew, UpSta & Num, DnSta & Num=  ,5029.8, 2 ,5029.8, 2 , 0 , 0 , 0 ,,
      .8      .8
   18.66   27.65
      .8      .8
   18.66   27.65
BR Coef= 1 , 1 , 0 ,1.25, 0 ,,,.8,0,2,0,
WSPro=,,,, 1 ,,,, 0 ,,,, 0 ,,,,-1 ,-1 ,-1 , 0 , 0 , 0 , 0 , 0
BR U #Sta/Elev= 65
  4401.5    43.3  4451.5    43.6  4511.5    42.8  4531.5    42.9  4591.5    42.4
  4621.5    41.2 4660.82   39.58 4751.62   24.32 4786.02   23.91 4827.72   24.94
 4889.82   23.37 4902.22   32.45 4927.72    27.4 4927.83   27.38 4927.92   27.36
 4930.32   26.89 4943.62   26.22 4948.72   24.16 4955.72   22.13 4960.82   20.77
 4970.62    18.8 4981.82   13.66 4984.52   13.46 4990.72   10.95 4993.02    10.6
 5000.52    9.53 5010.92   10.71 5015.52   13.56 5020.52   17.94 5029.82   19.74
 5034.92   22.16 5050.52   25.38 5051.32   25.56 5056.11   26.67 5056.22    26.7
 5060.42   27.67 5076.72   31.43 5080.52   29.78  5083.8   30.06 5109.52   32.23
 5112.02   35.34  5114.2   35.43 5161.82   37.32 5216.12   37.39  5235.8   37.67
 5285.22   38.37 5341.52   39.85  5392.1    40.1  5422.1    40.2  5442.1    40.8
  5572.1    40.8  5692.1    42.1  5712.1    41.1  5722.1    40.1  5732.1    41.3
  5742.1    41.8  5752.1    41.5  5829.3    42.6  6029.3    41.2  6039.3      42
  6239.3    41.7  6339.3    41.5  6349.3    41.9  6359.3    42.9  6382.1    43.3
BR U #Mann= 8
  4401.5      .2  4401.5      .1 4955.72     .04 5034.92     .14  5083.8      .1
  5114.2     .14  5235.8      .1  6382.1      .2
BR U Banks=4955.72,5034.92
BR D #Sta/Elev= 65
  4401.5    43.3  4451.5    43.6  4511.5    42.8  4531.5    42.9  4591.5    42.4
  4621.5    41.2 4660.82   39.58 4751.62   24.32 4786.02   23.91 4827.72   24.94
 4889.82   23.37 4902.22   32.45 4927.72    27.4 4927.83   27.38 4927.92   27.36
 4930.32   26.89 4943.62   26.22 4948.72   24.16 4955.72   22.13 4960.82   20.77
 4970.62    18.8 4981.82   13.66 4984.52   13.46 4990.72   10.95 4993.02    10.6
 5000.52    9.53 5010.92   10.71 5015.52   13.56 5020.52   17.94 5029.82   19.74
 5034.92   22.16 5050.52   25.38 5051.32   25.56 5056.11   26.67 5056.22    26.7
 5060.42   27.67 5076.72   31.43 5080.52   29.78  5083.8   30.06 5109.52   32.23
 5112.02   35.34  5114.2   35.43 5161.82   37.32 5216.12   37.39  5235.8   37.67
 5285.22   38.37 5341.52   39.85  5392.1    40.1  5422.1    40.2  5442.1    40.8
  5572.1    40.8  5692.1    42.1  5712.1    41.1  5722.1    40.1  5732.1    41.3
  5742.1    41.8  5752.1    41.5  5829.3    42.6  6029.3    41.2  6039.3      42
  6239.3    41.7  6339.3    41.5  6349.3    41.9  6359.3    42.9  6382.1    43.3
BR D #Mann= 8
  4401.5      .2  4401.5      .1 4955.72     .04 5034.92     .14  5083.8      .1
  5114.2     .14  5235.8      .1  6382.1      .2
BR D Banks=4955.72,5034.92
BC Design=,, 0 ,, 0 ,,,,,,

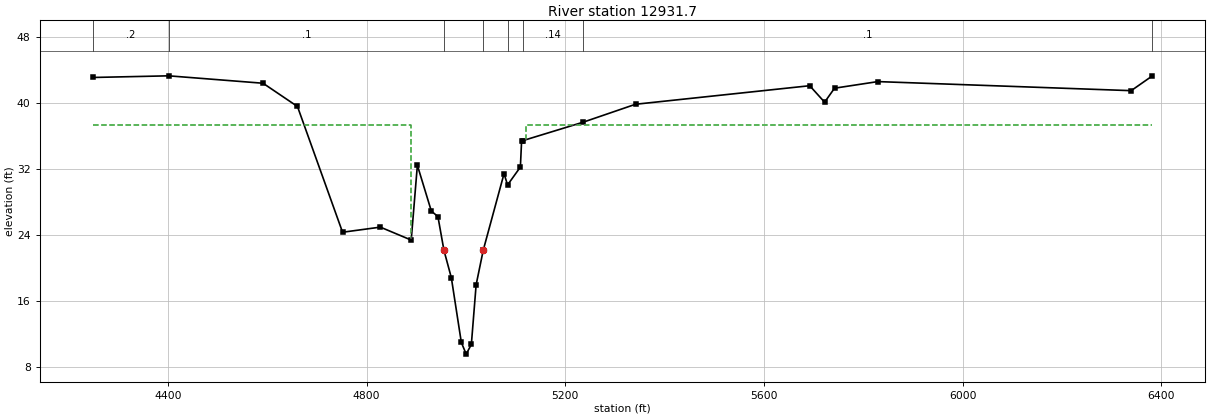
Type RM Length L Ch R = 1 ,12931.7 ,53.8,53.8,53.8
BEGIN DESCRIPTION:
Upstream Section of Bridge/Culvert/Weir
END DESCRIPTION:
XS GIS Cut Line= 6
      3153101.91     13875611.05      3153126.99     13874935.36
      3153125.52     13874719.96       3153156.5     13874228.68
      3153171.19     13873880.57      3153043.46     13873500.27
#Sta/Elev= 30
  4248.7    43.1  4401.5    43.3  4591.5    42.4  4660.8   39.58  4751.6   24.32
  4827.7   24.94  4889.8   23.37  4902.2   32.45  4930.3   26.89  4943.6   26.22
  4955.7   22.13  4970.6    18.8  4990.7   10.95  5000.5    9.53  5010.9   10.71
  5020.5   17.94  5034.9   22.16  5076.7   31.43  5083.8   30.06  5109.6   32.23
    5112   35.34  5114.2   35.43  5235.8   37.67  5341.4   39.85  5692.1    42.1
  5722.1    40.1  5742.1    41.8  5829.3    42.6  6339.3    41.5  6382.1    43.3
#Mann= 8 , 1 , 0
  4248.7      .2       0  4401.5      .1       0  4955.7    .045       0
  5034.9     .14       0  5083.8      .1       0  5114.2     .14       0
  5235.8      .1       0  6382.1      .2       0
#XS Ineff= 2 , 0
       0    4890    37.3  5120.5       0    37.3
Permanent Ineff=
       F       F
Bank Sta=4955.7,5034.9
XS Rating Curve= 0
Exp/Cntr=.5,.3