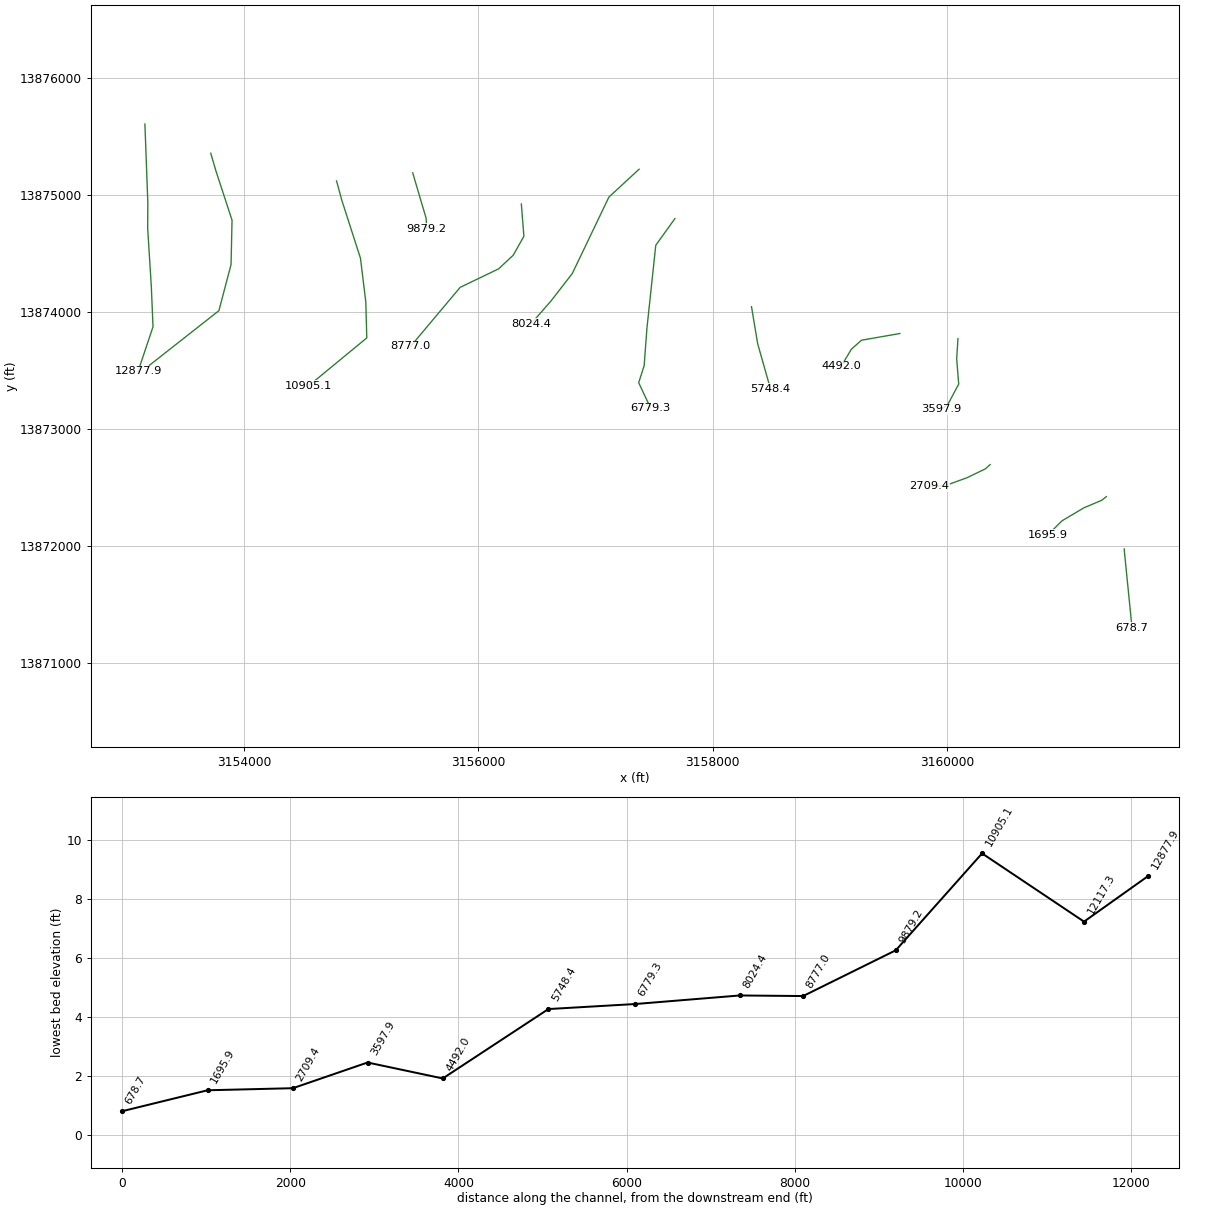
HEC-RAS study P118-00-00.PRJ: P118-00-00

--- P118-00-00.g01 (geometry) --- (continued)

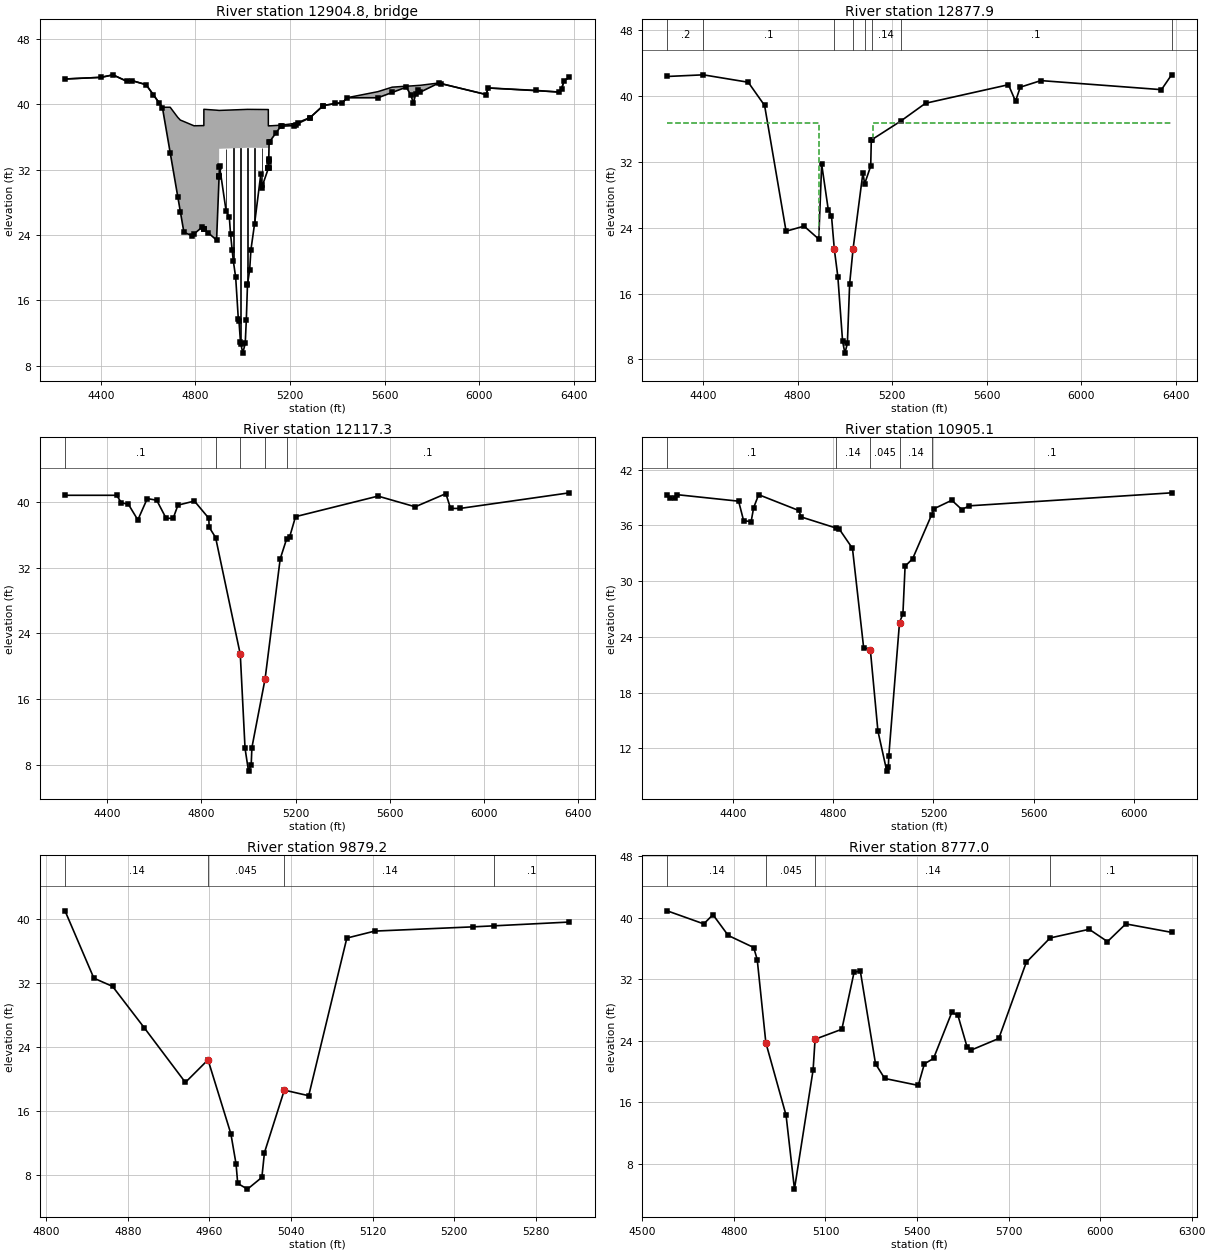
Type RM Length L Ch R = 3 ,12904.8 ,,,
BEGIN DESCRIPTION:
F.M. 527, MESA ROAD
Structure ID: P18-1
END DESCRIPTION:
Bridge Culvert--1,0,-1,-1, 0
Deck Dist Width WeirC Skew NumUp NumDn MinLoCord MaxHiCord MaxSubmerge Is_Ogee
10,33.8,2.6,0, 47, 47, , , .95, 0, 1,1,,
  4248.7  4401.5  4451.5  4511.5  4531.5  4591.5  4660.8  4693.5  4725.6  4736.4
  4751.6    4786  4794.3  4827.7 4835.89    4836  4889.8 4900.51  4900.6  5020.4
  5108.6 5108.71 5110.19  5110.3    5112  5161.8  5216.2  5224.6  5285.2  5341.4
  5422.1  5442.1  5572.1  5632.5  5692.1  5712.1  5722.1  5732.1  5742.1  5752.1
  5829.3  6029.3  6039.3  6339.3  6349.3  6359.3  6382.1
    43.1   43.31   43.61   42.81   42.91   42.41   39.64   39.64    38.4   38.07
   37.89   37.47   37.37   37.39   37.39   39.39   39.28   39.25   39.25   39.38
   39.36   37.36   37.36   37.36   37.36   37.44   37.64   37.67   38.38   39.86
   40.21   40.81   41.55    42.1   42.22   42.25   42.27   42.29   42.31   42.33
   42.61    41.2      42    41.5    41.9    42.9    43.3
    43.1    43.3    43.6    42.8    42.9    42.4   39.58   34.08   28.69   26.87
   24.32   23.91   24.12   24.94   24.73   24.73   23.37   31.21   34.55   34.68
   34.66   34.66   34.66   33.14   35.34   37.32   37.39   37.51   38.37   39.85
    40.2    40.8    40.8   41.45    42.1    41.1    40.1    41.3    41.8    41.5
    42.6    41.2      42    41.5    41.9    42.9    43.3
  4248.7  4401.5  4451.5  4511.5  4531.5  4591.5  4660.8  4693.5  4725.6  4736.4
  4751.6    4786  4794.3  4827.7 4835.89    4836  4889.8 4900.51  4900.6  5020.4
  5108.6 5108.71 5110.19  5110.3    5112  5161.8  5216.2  5224.6  5285.2  5341.4
  5422.1  5442.1  5572.1  5632.5  5692.1  5712.1  5722.1  5732.1  5742.1  5752.1
  5829.3  6029.3  6039.3  6339.3  6349.3  6359.3  6382.1
    43.1   43.31   43.61   42.81   42.91   42.41   39.64   39.64    38.4   38.07
   37.89   37.47   37.37   37.39   37.39   39.39   39.28   39.25   39.25   39.38
   39.36   37.36   37.36   37.36   37.36   37.44   37.64   37.67   38.38   39.86
   40.21   40.81   41.55    42.1   42.22   42.25   42.27   42.29   42.31   42.33
   42.61    41.2      42    41.5    41.9    42.9    43.3
   42.36   42.56   42.86   42.06   42.16   41.66   38.84   33.34   27.95   26.13
   23.58   23.17   23.38    24.2   23.99   23.99   22.63   30.47   33.81   33.94
   33.92   33.92   33.92    32.4    34.6   36.58   36.65   36.77   37.63   39.11
   39.46   40.06   40.06   40.71   41.36   40.36   39.36   40.56   41.06   40.76
   41.86   40.46   41.26   40.76   41.16   42.16   42.56
Pier Skew, UpSta & Num, DnSta & Num=  ,4930.3, 2 ,4930.3, 2 , 0 , 0 , 0 ,,
     1.2     1.2
   25.86   35.58
     1.2     1.2
   25.12   34.84
Pier Skew, UpSta & Num, DnSta & Num=  ,4960.8, 2 ,4960.8, 2 , 0 , 0 , 0 ,,
     1.2     1.2
   19.65   35.62
     1.2     1.2
   18.91   34.88
Pier Skew, UpSta & Num, DnSta & Num=  ,4990.7, 2 ,4990.7, 2 , 0 , 0 , 0 ,,
     1.2     1.2
    9.86   35.65
     1.2     1.2
    9.12   34.91
Pier Skew, UpSta & Num, DnSta & Num=  ,5020.8, 2 ,5020.8, 2 , 0 , 0 , 0 ,,
     1.2     1.2
   16.67   35.68
     1.2     1.2
   15.93   34.94
Pier Skew, UpSta & Num, DnSta & Num=  ,5050.5, 2 ,5050.5, 2 , 0 , 0 , 0 ,,
     1.2     1.2
   24.26   35.67
     1.2     1.2
   23.52   34.93
Pier Skew, UpSta & Num, DnSta & Num=  ,5080.5, 2 ,5080.5, 2 , 0 , 0 , 0 ,,
     1.2     1.2
   28.83   35.67
     1.2     1.2
   28.09   34.93
Abutment Skew #Up #Dn= , 2 , 2
  4900.4  4902.2
   34.55   32.45
  4900.4  4902.2
   33.81   31.71
BR Coef= 1 , 1 , 0 ,1.25, 0 ,,,.8,0,2,0,
WSPro=,,,, 1 ,,,, 0 ,,,, 0 ,,,,-1 ,-1 ,-1 , 0 , 0 , 0 , 0 , 0
BR U #Sta/Elev= 87
  4248.7    43.1  4401.5    43.3  4451.5    43.6  4511.5    42.8  4531.5    42.9
  4591.5    42.4  4621.5    41.2  4646.1   40.19  4660.8   39.58  4693.5   34.08
  4725.6   28.69  4736.4   26.87  4751.6   24.32    4786   23.91  4794.3   24.12
  4827.7   24.94 4835.89   24.73    4836   24.73 4836.11   24.73  4853.7   24.28
  4889.8   23.37  4900.4   31.13 4900.51   31.21  4900.6   31.28  4902.1   32.38
  4902.2   32.45  4930.3   26.89  4943.6   26.22  4948.7   24.16  4955.7   22.13
  4960.8   20.77  4970.6    18.8  4981.8   13.66  4984.5   13.46  4990.7   10.95
    4993    10.6  5000.5    9.53  5010.9   10.71  5015.5   13.56  5020.4   17.85
  5020.5   17.94  5029.8   19.74  5034.9   22.16  5050.5   25.38  5076.7   31.43
  5080.5   29.78  5083.8   30.06 5108.49   32.14  5108.6   32.15 5108.71   32.16
  5109.5   32.22  5109.6   32.23 5110.19   32.99  5110.3   33.14  5110.4   33.27
    5112   35.34  5114.2   35.43    5142   36.53  5161.8   37.32  5164.6   37.32
  5216.2   37.39  5224.6   37.51  5235.8   37.67    5284   38.35  5285.2   38.37
  5341.4   39.85  5341.5   39.85  5392.1    40.1  5422.1    40.2  5442.1    40.8
  5572.1    40.8  5632.5   41.45  5692.1    42.1  5712.1    41.1  5722.1    40.1
  5732.1    41.3  5742.1    41.8  5752.1    41.5  5829.3    42.6  5839.1   42.53
  6029.3    41.2  6039.3      42  6239.3    41.7  6339.3    41.5  6349.3    41.9
  6359.3    42.9  6382.1    43.3
BR U #Mann= 8
  4248.7      .2  4401.5      .1  4955.7    .045  5034.9     .14  5083.8      .1
  5114.2     .14  5235.8      .1  6382.1      .2
BR U Banks=4955.7,5034.9
BR D #Sta/Elev= 87
  4248.7   42.36  4401.5   42.56  4451.5   42.86  4511.5   42.06  4531.5   42.16
  4591.5   41.66  4621.5   40.46  4646.1   39.45  4660.8   38.84  4693.5   33.34
  4725.6   27.95  4736.4   26.13  4751.6   23.58    4786   23.17  4794.3   23.38
  4827.7    24.2 4835.89   23.99    4836   23.99 4836.11   23.99  4853.7   23.54
  4889.8   22.63  4900.4   30.39 4900.51   30.47  4900.6   30.54  4902.1   31.64
  4902.2   31.71  4930.3   26.15  4943.6   25.48  4948.7   23.42  4955.7   21.39
  4960.8   20.03  4970.6   18.06  4981.8   12.92  4984.5   12.72  4990.7   10.21
    4993    9.86  5000.5    8.79  5010.9    9.97  5015.5   12.82  5020.4   17.11
  5020.5    17.2  5029.8      19  5034.9   21.42  5050.5   24.64  5076.7   30.69
  5080.5   29.04  5083.8   29.32 5108.49    31.4  5108.6   31.41 5108.71   31.42
  5109.5   31.48  5109.6   31.49 5110.19   32.25  5110.3    32.4  5110.4   32.53
    5112    34.6  5114.2   34.69    5142   35.79  5161.8   36.58  5164.6   36.58
  5216.2   36.65  5224.6   36.77  5235.8   36.93    5284   37.61  5285.2   37.63
  5341.4   39.11  5341.5   39.11  5392.1   39.36  5422.1   39.46  5442.1   40.06
  5572.1   40.06  5632.5   40.71  5692.1   41.36  5712.1   40.36  5722.1   39.36
  5732.1   40.56  5742.1   41.06  5752.1   40.76  5829.3   41.86  5839.1   41.79
  6029.3   40.46  6039.3   41.26  6239.3   40.96  6339.3   40.76  6349.3   41.16
  6359.3   42.16  6382.1   42.56
BR D #Mann= 8
  4248.7      .2  4401.5      .1  4955.7    .045  5034.9     .14  5083.8      .1
  5114.2     .14  5235.8      .1  6382.1      .2
BR D Banks=4955.7,5034.9
BC Design=,, 0 ,, 0 ,,,,,,

Type RM Length L Ch R = 1 ,12877.9 ,760.6,760.6,760.6
BEGIN DESCRIPTION:
Downstream Section of Bridge/Culvert/Weir
END DESCRIPTION:
XS GIS Cut Line= 6
      3153155.07     13875602.83      3153180.15     13874927.14
      3153178.68     13874711.74      3153209.66     13874220.46
      3153224.35     13873872.35      3153096.63     13873492.05
#Sta/Elev= 30
  4248.7   42.34  4401.5   42.54  4591.5   41.64  4660.8   38.82  4751.6   23.56
  4827.7   24.18  4889.8   22.61  4902.2   31.69  4930.3   26.13  4943.6   25.46
  4955.7   21.37  4970.6   18.04  4990.7   10.19  5000.5    8.77  5010.9    9.95
  5020.5   17.18  5034.9    21.4  5076.7   30.67  5083.8    29.3  5109.6   31.47
    5112   34.58  5114.2   34.67  5235.8   36.91  5341.4   39.09  5692.1   41.34
  5722.1   39.34  5742.1   41.04  5829.3   41.84  6339.3   40.74  6382.1   42.54
#Mann= 8 , 1 , 0
  4248.7      .2       0  4401.5      .1       0  4955.7    .045       0
  5034.9     .14       0  5083.8      .1       0  5114.2     .14       0
  5235.8      .1       0  6382.1      .2       0
#XS Ineff= 2 , 0
       0    4890    36.7  5120.5       0    36.7
Permanent Ineff=
       F       F
Bank Sta=4955.7,5034.9
XS Rating Curve= 0
Exp/Cntr=.5,.3

Type RM Length L Ch R = 1 ,12117.3 ,1163.1,1212.2,1241.1
BEGIN DESCRIPTION:
Cross Section 12117.3
END DESCRIPTION:
XS GIS Cut Line= 6
        3153717.     13875353.88      3153761.74     13875201.36
      3153898.74     13874782.05      3153890.44     13874404.24
      3153786.65     13874009.84      3153193.69     13873543.81
#Sta/Elev= 30
  4221.7    40.8  4440.7    40.8  4460.7    39.9  4490.7    39.7  4530.7    37.8
  4570.7    40.4  4610.7    40.2  4650.7      38  4680.7      38  4700.7    39.6
  4770.7    40.1  4831.8      38  4833.2   36.92  4860.6   35.66  4965.3   21.45
  4985.5      10  5000.2    7.23  5011.6       8  5014.6    10.1  5070.6   18.46
  5134.6   33.05  5161.8   35.48  5175.2   35.78  5199.7    38.2  5549.7    40.7
  5707.5    39.4  5837.5      41  5857.5    39.2  5897.5    39.2  6361.7    41.1
#Mann= 5 , 1 , 0
  4221.7      .1       0  4860.6     .07       0  4965.3    .045       0
  5070.6     .07       0  5161.8      .1       0
Bank Sta=4965.3,5070.6
XS Rating Curve= 0
Exp/Cntr=.3,.1

Type RM Length L Ch R = 1 ,10905.1 ,1014.1,1025.9,1108.9
BEGIN DESCRIPTION:
Cross Section 10905.1
END DESCRIPTION:
XS GIS Cut Line= 6
       3154790.8     13875117.03      3154837.02     13874948.11
      3154994.78     13874458.22      3155040.45     13874084.57
      3155048.75     13873777.34      3154554.53     13873370.67
#Sta/Elev= 30
  4136.9    39.3  4146.9    38.9  4166.9    38.9  4176.9    39.3  4422.1    38.6
  4442.1    36.5  4472.1    36.4  4482.1    37.9  4502.1    39.3  4662.1    37.6
  4672.1    36.9  4809.9   35.72  4824.3   35.58  4876.6   33.52  4921.2   22.84
    4948   22.59  4978.2   13.86  5013.6    9.54  5019.9    9.99  5021.7    11.2
  5064.4   25.53    5078   26.47  5086.7    31.6  5116.7    32.4  5192.7   37.14
  5203.2    37.8  5273.2    38.7  5313.2    37.7  5343.2    38.1  6150.5    39.5
#Mann= 5 , 1 , 0
  4136.9      .1       0  4809.9     .14       0    4948    .045       0
  5064.4     .14       0  5192.7      .1       0
Bank Sta=4948,5064.4
XS Rating Curve= 0
Exp/Cntr=.3,.1

Type RM Length L Ch R = 1 ,9879.2  ,1148.9,1102.2,1095
BEGIN DESCRIPTION:
Cross Section 9879.2
END DESCRIPTION:
XS GIS Cut Line= 3
      3155440.73     13875186.56      3155555.26     13874798.65
      3155560.37     13874708.76
#Sta/Elev= 19
  4818.4      41  4846.7   32.59    4865   31.57  4896.1    26.4  4936.4   19.58
  4958.6    22.4    4981   13.17  4986.1    9.39  4987.7    6.97  4997.3    6.26
  5011.4    7.73  5013.9   10.81  5033.4   18.62  5057.3   17.92  5094.7    37.6
    5122   38.47  5218.4      39  5239.4   39.13  5312.9    39.6
#Mann= 4 , 1 , 0
  4818.4     .14       0  4958.6    .045       0  5033.4     .14       0
  5239.4      .1       0
Bank Sta=4958.6,5033.4
XS Rating Curve= 0
Exp/Cntr=.3,.1

Type RM Length L Ch R = 1 ,8777.0  ,748.3,752.6,876.6
BEGIN DESCRIPTION:
Cross Section 8777.0
END DESCRIPTION:
XS GIS Cut Line= 6
      3156367.98     13874920.71      3156389.74     13874645.04
       3156298.4     13874483.13      3156173.85     13874366.88
      3155845.87     13874209.12      3155424.29     13873707.06
#Sta/Elev= 30
  4581.3    40.9  4701.3    39.2  4731.3    40.4  4781.3    37.7  4864.8   36.13
  4876.4   34.56  4904.7   23.74  4970.9   14.32  4998.4    4.71  5059.5    20.2
    5066    24.2  5153.7    25.5  5193.7    32.9  5214.1    33.1  5264.1      21
  5294.1    19.1  5404.1    18.2  5424.1      21  5454.1    21.7  5514.1    27.7
  5534.1    27.3  5564.1    23.2    5578    22.8    5668    24.3    5758    34.2
  5836.1   37.37  5964.2    38.5  6024.2    36.9  6084.2    39.2  6234.2    38.1
#Mann= 4 , 1 , 0
  4581.3     .14       0  4904.7    .045       0    5066     .14       0
  5836.1      .1       0
Bank Sta=4904.7,5066
XS Rating Curve= 0
Exp/Cntr=.3,.1

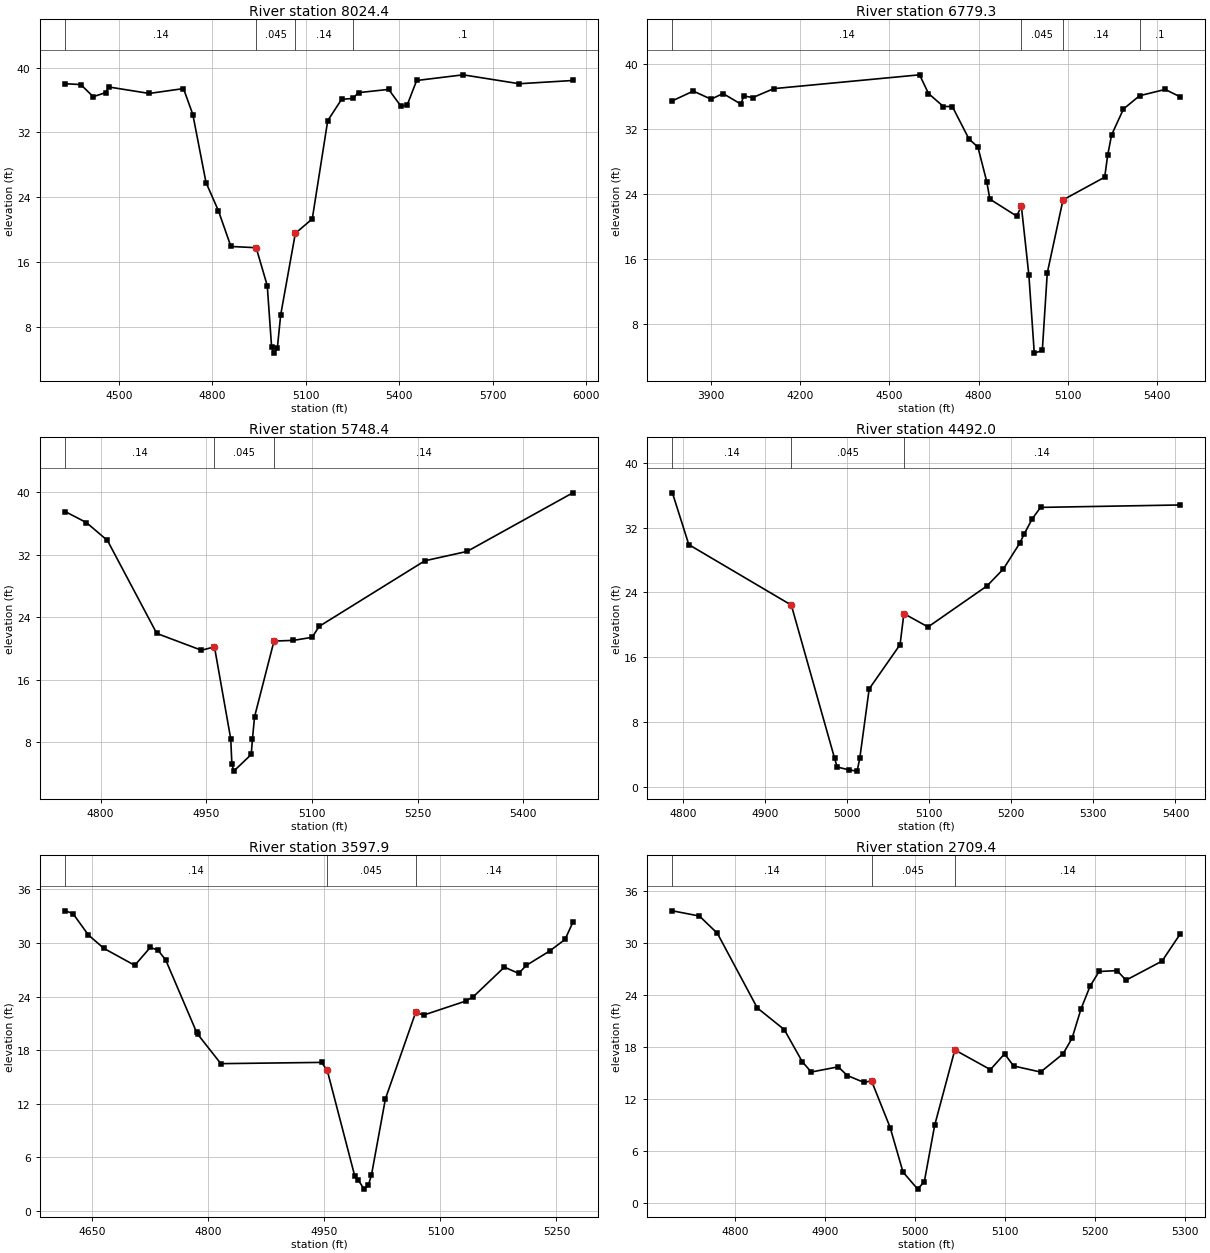
Type RM Length L Ch R = 1 ,8024.4  ,1169.6,1245.1,1353.1
BEGIN DESCRIPTION:
Cross Section 8024.4
END DESCRIPTION:
XS GIS Cut Line= 5
      3157372.79     13875217.27      3157115.29     13874979.58
      3156802.77     13874326.99      3156620.57     13874092.17
      3156450.12     13873897.05
#Sta/Elev= 30
  4327.5      38  4377.5    37.9  4417.5    36.4  4457.5    36.9  4467.5    37.6
  4597.5    36.8  4707.5    37.4  4737.5    34.2  4779.8    25.8  4819.8    22.3
  4859.8    17.9  4940.9   17.75  4976.5   13.07  4990.5    5.47  4998.1    4.73
  5008.8    5.31  5019.6    9.44  5066.7   19.52  5121.1   21.31  5170.7   33.44
  5215.4   36.08  5250.8   36.18  5269.8    36.9  5366.3    37.3  5406.3    35.2
  5426.3    35.4  5456.3    38.4  5605.6    39.1  5785.6      38  5957.8    38.4
#Mann= 4 , 1 , 0
  4327.5     .14       0  4940.9    .045       0  5066.7     .14       0
  5250.8      .1       0
Bank Sta=4940.9,5066.7
XS Rating Curve= 0
Exp/Cntr=.3,.1

Type RM Length L Ch R = 1 ,6779.3  ,987.8,1030.9,1040.3
BEGIN DESCRIPTION:
Cross Section 6779.3
END DESCRIPTION:
XS GIS Cut Line= 6
      3157679.07     13874796.23       3157515.4     13874568.32
      3157439.53     13873856.28      3157416.19     13873541.12
      3157369.49     13873395.21      3157471.45     13873177.93
#Sta/Elev= 30
  3771.3    35.5  3841.3    36.7  3901.3    35.7  3941.3    36.4  4001.3    35.1
  4011.3    36.1  4041.3    35.9  4111.9      37  4601.9    38.7  4631.9    36.4
  4681.9    34.8  4711.9    34.8    4768    30.8    4798    29.8    4828    25.5
    4838    23.4  4928.2   21.31    4944   22.53  4969.3   14.01  4987.4    4.44
  5014.4    4.77    5031    14.3  5083.9    23.3    5224    26.1    5234    28.8
  5247.2    31.3  5287.2    34.5  5341.5   36.13  5427.2    36.9  5477.2      36
#Mann= 4 , 1 , 0
  3771.3     .14       0    4944    .045       0  5083.9     .14       0
  5341.5      .1       0
Bank Sta=4944,5083.9
XS Rating Curve= 0
Exp/Cntr=.3,.1

Type RM Length L Ch R = 1 ,5748.4  ,1399.8,1256.4,1065.2
BEGIN DESCRIPTION:
Cross Section 5748.4
END DESCRIPTION:
XS GIS Cut Line= 3
      3158332.33       13874044.      3158385.02     13873727.88
      3158494.22     13873343.06
#Sta/Elev= 19
  4749.6    37.5  4779.6    36.1  4809.6    33.8  4879.6    21.9  4942.9   19.75
  4961.5   20.17  4984.6    8.39  4986.2    5.21  4988.9    4.27  5013.7     6.4
  5015.4    8.37  5018.4   11.23    5046   20.92  5073.5   21.01  5100.1    21.4
  5110.1    22.8  5260.1    31.2  5320.1    32.4  5470.1    39.9
#Mann= 3 , 1 , 0
  4749.6     .14       0  4961.5    .045       0    5046     .14       0
Bank Sta=4961.5,5046
XS Rating Curve= 0
Exp/Cntr=.3,.1

Type RM Length L Ch R = 1 ,4492.0  ,714.9,894.1,935.9
BEGIN DESCRIPTION:
Cross Section 4492.0
END DESCRIPTION:
XS GIS Cut Line= 5
      3159598.73     13873815.22      3159598.66     13873815.04
      3159271.18     13873757.92       3159184.6     13873681.19
      3159097.83     13873534.65
#Sta/Elev= 19
    4787    36.3    4807    29.9  4931.9   22.43  4984.7    3.48  4987.8    2.43
  5002.8    2.06  5012.1    1.92  5015.3    3.48  5026.8   12.08  5064.4   17.54
  5069.1   21.38  5098.5   19.73  5170.4    24.8  5190.4    26.9  5210.4    30.1
  5215.6    31.2  5225.6    33.1  5235.6    34.5  5405.6    34.8
#Mann= 3 , 1 , 0
    4787     .14       0  4931.9    .045       0  5069.1     .14       0
Bank Sta=4931.9,5069.1
XS Rating Curve= 0
Exp/Cntr=.3,.1

Type RM Length L Ch R = 1 ,3597.9  ,1026.9,888.5,801.2
BEGIN DESCRIPTION:
Cross Section 3597.9
END DESCRIPTION:
XS GIS Cut Line= 5
      3160094.42     13873770.38      3160083.39     13873599.48
       3160100.9     13873383.54      3160007.52     13873208.45
      3159950.81     13873167.31
#Sta/Elev= 29
  4614.7    33.6  4624.7    33.3  4644.7    30.9  4664.7    29.4  4704.7    27.5
  4724.7    29.5  4734.7    29.2  4744.7    28.1  4784.7      20    4786    19.8
    4816    16.5  4946.2   16.64  4953.5   15.77  4989.2    3.91  4993.8    3.46
  5001.2    2.46  5006.7    2.88  5010.8    4.06  5028.8   12.56  5067.9   22.23
  5078.4   21.94  5132.6    23.5  5142.6      24  5182.6    27.3  5201.1    26.6
  5211.1    27.5  5241.1    29.1  5261.1    30.4  5271.1    32.3
#Mann= 3 , 1 , 0
  4614.7     .14       0  4953.5    .045       0  5067.9     .14       0
Bank Sta=4953.5,5067.9
XS Rating Curve= 0
Exp/Cntr=.3,.1

Type RM Length L Ch R = 1 ,2709.4  ,975.3,1013.5,1031.7
BEGIN DESCRIPTION:
Cross Section 2709.4
END DESCRIPTION:
XS GIS Cut Line= 5
      3160368.94     13872696.13      3160328.52     13872659.83
      3160170.94     13872583.96      3159978.34     13872513.92
      3159848.32      13872511.4
#Sta/Elev= 30
  4730.7    33.7  4760.7    33.1  4780.7    31.1    4825    22.5    4855      20
    4875    16.3    4885    15.1    4915    15.7    4925    14.7  4943.5   13.91
    4952   14.08  4972.7     8.7    4987    3.56  5003.3    1.59  5010.7    2.46
  5022.2    8.96  5044.6   17.65  5084.1   15.38  5099.9    17.2  5109.9    15.8
  5139.9    15.1  5164.9    17.2  5174.9      19  5184.9    22.4  5194.9      25
  5204.9    26.7  5224.9    26.8  5234.9    25.7  5274.9    27.9  5294.9      31
#Mann= 3 , 1 , 0
  4730.7     .14       0    4952    .045       0  5044.6     .14       0
Bank Sta=4952,5044.6
XS Rating Curve= 0
Exp/Cntr=.3,.1

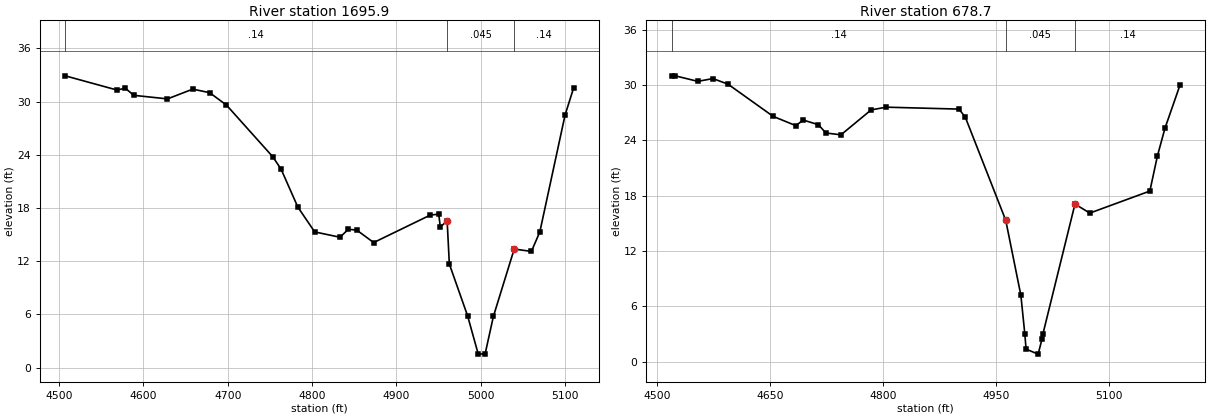
Type RM Length L Ch R = 1 ,1695.9  ,922.6,1017.2,1096.3
BEGIN DESCRIPTION:
Cross Section 1695.9
END DESCRIPTION:
XS GIS Cut Line= 5
      3161361.19     13872423.05       3161320.7     13872391.36
      3161168.95     13872327.16      3160982.19     13872216.27
      3160862.04     13872096.12
#Sta/Elev= 30
  4507.1    32.9  4568.5    31.3  4578.5    31.5  4588.5    30.7  4628.5    30.3
  4658.5    31.4  4678.5      31  4698.5    29.6  4753.2    23.8  4763.2    22.4
  4783.2    18.1  4803.2    15.3  4833.2    14.7  4843.2    15.6  4853.2    15.5
  4873.2    14.1  4940.4    17.2  4950.4    17.3  4952.3   15.86  4960.4   16.54
    4963   11.68  4984.7    5.83  4997.3    1.52  5005.5    1.56  5015.3    5.78
    5040   13.37  5060.4    13.1  5070.4    15.3  5100.4    28.5  5110.4    31.5
#Mann= 3 , 1 , 0
  4507.1     .14       0  4960.4    .045       0    5040     .14       0
Bank Sta=4960.4,5040
XS Rating Curve= 0
Exp/Cntr=.3,.1

Type RM Length L Ch R = 1 ,678.7   ,0,0,0
BEGIN DESCRIPTION:
Cross Section 678.7
END DESCRIPTION:
XS GIS Cut Line= 3
      3161514.25     13871975.78       3161513.3     13871971.14
      3161579.96     13871304.51
#Sta/Elev= 28
  4519.4      31  4524.1      31  4554.1    30.4  4574.1    30.7  4594.1    30.1
  4654.1    26.6  4684.1    25.6  4694.1    26.2  4714.1    25.7  4724.1    24.8
  4744.1    24.6  4784.1    27.3  4804.1    27.6  4900.7   27.39  4909.1   26.52
  4962.8   15.33  4982.9    7.19  4988.1    3.02  4989.8    1.35  5005.8     .81
    5011    2.46    5012    2.95  5054.7   17.09  5074.4   16.11  5154.1    18.5
  5164.1    22.3  5174.1    25.3  5194.1      30
#Mann= 3 , 1 , 0
  4519.4     .14       0  4962.8    .045       0  5054.7     .14       0
Bank Sta=4962.8,5054.7
XS Rating Curve= 0
Exp/Cntr=.3,.1

Chan Stop Cuts=-1